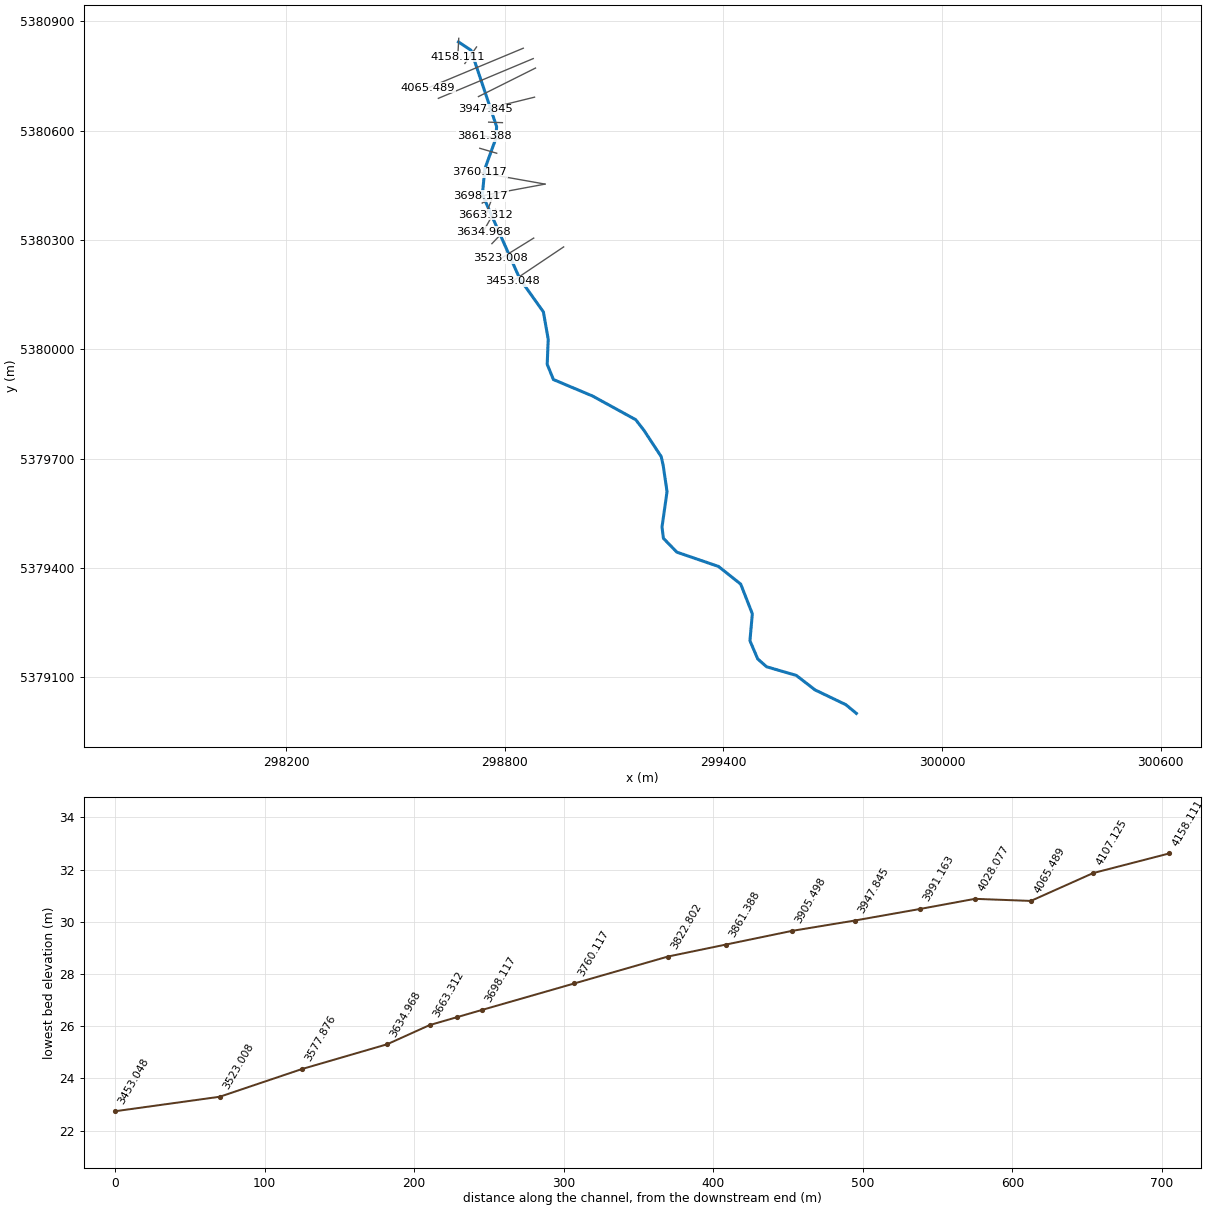
--- Blanche_Brook.prj (project) ---

Proj Title=Stephenville Model
Current Plan=p02
Default Exp/Contr=0.3,0.1
SI Units
Geom File=g01
Geom File=g07
Geom File=g11
Geom File=g03
Geom File=g05
Flow File=f03
Flow File=f05
Flow File=f04
Flow File=f01
Flow File=f02
Flow File=f06
Flow File=f07
Flow File=f08
Flow File=f10
Plan File=p02
Plan File=p05
Plan File=p06
Plan File=p01
Plan File=p04
Plan File=p03
Plan File=p07
Plan File=p08
Plan File=p11
Plan File=p09
Plan File=p13
Plan File=p14
Plan File=p16
Y Axis Title=Elevation
X Axis Title(PF)=Main Channel Distance
X Axis Title(XS)=Station
BEGIN DESCRIPTION:
END DESCRIPTION:
DSS Export Rating Curves= 0
DSS Export Rating Curve Sorted= 0
DSS Export Volume Flow Curves= 0
DXF Filename=..\..\..\Hydr\Hydraulic Model\StephenvilleModel.
DXF OffsetX= 0
DXF OffsetY= 0
DXF ScaleX= 1
DXF ScaleY= 10

--- Blanche_Brook.p02 (plan) ---

Plan Title=20 Year Flood
Program Version=4.00
Short Identifier=20 Yr Flood
Geom File=g01
Flow File=f03
Mixed Flow
K Sum by GR= 0
Std Step Tol= 0.01
Critical Tol= 0.01
Num of Std Step Trials= 20
Max Error Tol= 0.3
Flow Tol Ratio= 0.001
Split Flow NTrial= 30
Split Flow Tol= 0.02
Split Flow Ratio= 0.02
Log Output Level= 0
Friction Slope Method= 1
Unsteady Friction Slope Method= 2
Unsteady Bridges Friction Slope Method= 1
Parabolic Critical Depth
Global Vel Dist= 0 , 0 , 0
Global Log Level= 0
CheckData=True
Encroach Param=-1 ,0,0, 0
Computation Interval=1HOUR
Output Interval=1HOUR
Run HTab= 0
Run UNet= 0
Run PostProcess= 0
Run WQNet= 0
UNET Theta= 1
UNET Theta Warmup= 1
UNET ZTol= 0.02
UNET ZSATol= 0.05
UNET MxIter= 20
UNET MaxInSteps= 0
UNET DtIC= 0
UNET DtMin= 0
UNET MaxCRTS= 20
UNET WFStab= 2
UNET SFStab= 1
UNET WFX= 1
UNET SFX= 1
UNET DSS MLevel= 4
UNET DZMax Abort= 100
UNET Convert EG Bridges= 0
UNET Use Existing IB Tables=-1
UNET Froude Reduction=False
UNET Froude Limit= 1
UNET Froude Power= 10
UNET Time Slicing=0,0, 5
Instantaneous Interval=1HOUR
Write IC File= 0
Echo Input=False
Echo Output=False
Write Detailed= 0
Detailed Automatic Start=False, 10
WQ ULTIMATE=-1
WQ Max Comp Step=1HOUR
WQ Output Interval=15MIN
WQ Output Selected Increments= 0
WQ Output face flow=0
WQ Output face velocity=0
WQ Output face area=0
WQ Output face dispersion=0
WQ Output cell volume=0
WQ Output cell surface area=0
WQ Output cell continuity=0
WQ Output face conc=0
WQ Output face dconc_dx=0
WQ Output face courant=0
WQ Output face peclet=0
WQ Output face adv mass=0
WQ Output face disp mass=0
WQ Output cell mass=0
WQ Output cell source sink temp=0
WQ Output cell source sink nsm=0
WQ Output MaxMinRange=-1
WQ Daily Max Min Mean=-1
WQ Daily Range=0
WQ Daily Time=0
WQ Create Restart=0
WQ Fixed Restart=0
WQ System Summary=False
Sorting and Armoring Iterations= 10
XS Update Threshold= 0.02
Hydraulics Update Threshold= 0.02
Energy Slope Method= 1
Volume Change Method= 0
XS Weighting Method= 0
Number of US Weighted Cross Sections= 1
Number of DS Weighted Cross Sections= 1
Upstream XS Weight=0.25
Main XS Weight=0.5
Downstream XS Weight=0.25
Number of DS XS's Weighted with US Boundary= 1
Upstream Boundary Weight= 1
Weight of XSs Associated with US Boundary= 0
Number of US XS's Weighted with DS Boundary= 1
Downstream Boundary Weight= 0.5
Weight of XSs Associated with DS Boundary= 0.5
Sediment Output Level= 4
Mass or Volume Output= 0
Output Increment Type= 1
Profile and TS Output Increment= 10
XS Output Flag= 0
XS Output Increment= 10
Disregard all LS=0
Disregard all Conn=0
Disregard all Breaches=0
Disregard all Pumps=0

--- Blanche_Brook.p01 (plan) ---

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Plan Title=NP Rating Curve
Short Identifier=NP Rating
Geom File=g01
Flow File=f01

--- Blanche_Brook.p03 (plan) ---

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Plan Title=Sensitivity 1_ + 20% n
Short Identifier=Sens1
Geom File=g11
Flow File=f05

--- Blanche_Brook.p04 (plan) ---

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Plan Title=2005 Event
Short Identifier=2005
Geom File=g01
Flow File=f02

--- Blanche_Brook.p05 (plan) ---

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Plan Title=100 Year Flood
Short Identifier=100 Yr Flood
Geom File=g01
Flow File=f05

--- Blanche_Brook.p06 (plan) ---

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Plan Title=Calibration (SA) CHECK
Short Identifier=Cal CHECK
Geom File=g01
Flow File=f04
Std Step Tol= 0.003
Critical Tol= 0.003
Max Error Tol= 0.1
Split Flow Tol= 0.006
UNET ZTol= 0.006
UNET ZSATol= 0.015
UNET DZMax Abort= 30
DSS File=dss

--- Blanche_Brook.p07 (plan) ---

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Plan Title=Sensitivity 2_ - 20% n
Short Identifier=Sens2
Geom File=g07
Flow File=f05

--- Blanche_Brook.p08 (plan) ---

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Plan Title=Sensitivity 3_ Tidal Sens
Short Identifier=Sens3
Geom File=g01
Flow File=f06

--- Blanche_Brook.p09 (plan) ---

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Plan Title=Sensitivity 5_ - 10% Q
Short Identifier=Q-10%
Geom File=g01
Flow File=f08

--- Blanche_Brook.p11 (plan) ---

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Plan Title=Sensitivity 4_ + 10% Q
Short Identifier=Q+10%
Geom File=g01
Flow File=f07

--- Blanche_Brook.p13 (plan) ---

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Plan Title=Structure_Blockage_Ice_20yr
Short Identifier=Block_Ice_20yr
Geom File=g05
Flow File=f03

--- Blanche_Brook.p14 (plan) ---

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Plan Title=Structure_Blockage_100yr
Short Identifier=Block_100yr
Geom File=g03
Flow File=f05

--- Blanche_Brook.f03 (steady flow) ---

Flow Title=1/20 Year Flood
Program Version=4.00
Number of Profiles= 1
Profile Names=PF1
River Rch & RM=Blanche Brook,US of Confluence,4158.111
   139.7
River Rch & RM=Blanche Brook,US of Confluence,3523.008
   142.2
River Rch & RM=Blanche Brook,DS of Confluence,1727.041
   169.8
River Rch & RM=Warm Creek,DS of Noels Pond,2889.005
    36.5
River Rch & RM=Warm Creek,DS of Noels Pond,2436.619
    37.6
River Rch & RM=Warm Creek,US of Noels Pond,7941.430
   137.1
River Rch & RM=Warm Creek,US of Noels Pond,6943.722
   149.2
Boundary for River Rch & Prof#=Blanche Brook,US of Confluence, 1
Up Type= 3
Up Slope=0.015
Dn Type= 0
Boundary for River Rch & Prof#=Blanche Brook,DS of Confluence, 1
Up Type= 0
Dn Type= 1
Dn Known WS=0.78
Boundary for River Rch & Prof#=Warm Creek,DS of Noels Pond, 1
Up Type= 0
Dn Type= 0
Boundary for River Rch & Prof#=Warm Creek,US of Noels Pond, 1
Up Type= 3
Up Slope=0.008
Dn Type= 0
DSS Import GetInterval= 0
DSS Import GetPeak= 0
DSS Import FillOption= 0
Storage Area Elev=Noel's Pond     , 1
   22.91

--- Blanche_Brook.f01 (steady flow) ---

Flow Title=NP Rating Curve
Program Version=4.00
Number of Profiles= 18
Profile Names=PF 1,PF 2,PF 3,PF 4,PF 5,PF 6,PF 7,PF 8,PF 9,PF 10,PF 11,PF 12,PF 13,PF 14,PF 15,PF 16,PF 17,PF 18
River Rch & RM=Blanche Brook,US of Confluence,4158.111
      10      10      10      10      10      10      10      10      10      10
      10      10      10      10      10      10      10      10
River Rch & RM=Blanche Brook,DS of Confluence,1727.041
      15      15      15      15      15      15      15      15      15      15
      15      15      15      15      15      15      15      15
River Rch & RM=Warm Creek,DS of Noels Pond,2889.005
       2       3       4       5      10      20      30      40      45      50
      55      60      65      70      80      90     100     120
River Rch & RM=Warm Creek,US of Noels Pond,7941.430
       2       3       4       5      10      20      30      40      45      50
      55      60      65      70      80      90     100     120
Boundary for River Rch & Prof#=Blanche Brook,US of Confluence, 1
Up Type= 3
Up Slope=0.015
Dn Type= 0
Boundary for River Rch & Prof#=Blanche Brook,US of Confluence, 2
Up Type= 3
Up Slope=0.015
Dn Type= 0
Boundary for River Rch & Prof#=Blanche Brook,US of Confluence, 3
Up Type= 3
Up Slope=0.015
Dn Type= 0
Boundary for River Rch & Prof#=Blanche Brook,US of Confluence, 4
Up Type= 3
Up Slope=0.015
Dn Type= 0
Boundary for River Rch & Prof#=Blanche Brook,US of Confluence, 5
Up Type= 3
Up Slope=0.015
Dn Type= 0
Boundary for River Rch & Prof#=Blanche Brook,US of Confluence, 6
Up Type= 3
Up Slope=0.015
Dn Type= 0
Boundary for River Rch & Prof#=Blanche Brook,US of Confluence, 7
Up Type= 3
Up Slope=0.015
Dn Type= 0
Boundary for River Rch & Prof#=Blanche Brook,US of Confluence, 8
Up Type= 3
Up Slope=0.015
Dn Type= 0
Boundary for River Rch & Prof#=Blanche Brook,US of Confluence, 9
Up Type= 3
Up Slope=0.015
Dn Type= 0
Boundary for River Rch & Prof#=Blanche Brook,US of Confluence, 10
Up Type= 3
Up Slope=0.015
Dn Type= 0
Boundary for River Rch & Prof#=Blanche Brook,US of Confluence, 11
Up Type= 3
Up Slope=0.015
Dn Type= 0
Boundary for River Rch & Prof#=Blanche Brook,US of Confluence, 12
Up Type= 3
Up Slope=0.015
Dn Type= 0
Boundary for River Rch & Prof#=Blanche Brook,US of Confluence, 13
Up Type= 3
Up Slope=0.015
Dn Type= 0
Boundary for River Rch & Prof#=Blanche Brook,US of Confluence, 14
Up Type= 3
Up Slope=0.015
Dn Type= 0
Boundary for River Rch & Prof#=Blanche Brook,US of Confluence, 15
Up Type= 3
Up Slope=0.015
Dn Type= 0
Boundary for River Rch & Prof#=Blanche Brook,US of Confluence, 16
Up Type= 3
Up Slope=0.015
Dn Type= 0
Boundary for River Rch & Prof#=Blanche Brook,US of Confluence, 17
Up Type= 3
Up Slope=0.015
Dn Type= 0
Boundary for River Rch & Prof#=Blanche Brook,US of Confluence, 18
Up Type= 3
Up Slope=0.015
Dn Type= 0
Boundary for River Rch & Prof#=Blanche Brook,DS of Confluence, 1
Up Type= 0
Dn Type= 1
Dn Known WS=0.78
Boundary for River Rch & Prof#=Blanche Brook,DS of Confluence, 2
Up Type= 0
Dn Type= 1
Dn Known WS=0.78
Boundary for River Rch & Prof#=Blanche Brook,DS of Confluence, 3
Up Type= 0
Dn Type= 1
Dn Known WS=0.78
Boundary for River Rch & Prof#=Blanche Brook,DS of Confluence, 4
Up Type= 0
Dn Type= 1
Dn Known WS=0.78
Boundary for River Rch & Prof#=Blanche Brook,DS of Confluence, 5
Up Type= 0
Dn Type= 1
Dn Known WS=0.78
Boundary for River Rch & Prof#=Blanche Brook,DS of Confluence, 6
Up Type= 0
Dn Type= 1
Dn Known WS=0.78
Boundary for River Rch & Prof#=Blanche Brook,DS of Confluence, 7
Up Type= 0
Dn Type= 1
Dn Known WS=0.78
Boundary for River Rch & Prof#=Blanche Brook,DS of Confluence, 8
Up Type= 0
Dn Type= 1
Dn Known WS=0.78
Boundary for River Rch & Prof#=Blanche Brook,DS of Confluence, 9
Up Type= 0
Dn Type= 1
Dn Known WS=0.78
Boundary for River Rch & Prof#=Blanche Brook,DS of Confluence, 10
Up Type= 0
Dn Type= 1
Dn Known WS=0.78
Boundary for River Rch & Prof#=Blanche Brook,DS of Confluence, 11
Up Type= 0
Dn Type= 1
Dn Known WS=0.78
Boundary for River Rch & Prof#=Blanche Brook,DS of Confluence, 12
Up Type= 0
Dn Type= 1
Dn Known WS=0.78
Boundary for River Rch & Prof#=Blanche Brook,DS of Confluence, 13
Up Type= 0
Dn Type= 1
Dn Known WS=0.78
Boundary for River Rch & Prof#=Blanche Brook,DS of Confluence, 14
Up Type= 0
Dn Type= 1
Dn Known WS=0.78
Boundary for River Rch & Prof#=Blanche Brook,DS of Confluence, 15
Up Type= 0
Dn Type= 1
Dn Known WS=0.78
Boundary for River Rch & Prof#=Blanche Brook,DS of Confluence, 16
Up Type= 0
Dn Type= 1
Dn Known WS=0.78
Boundary for River Rch & Prof#=Blanche Brook,DS of Confluence, 17
Up Type= 0
Dn Type= 1
Dn Known WS=0.78
Boundary for River Rch & Prof#=Blanche Brook,DS of Confluence, 18
Up Type= 0
Dn Type= 1
Dn Known WS=0.78
Boundary for River Rch & Prof#=Warm Creek,DS of Noels Pond, 1
Up Type= 0
Dn Type= 0
Boundary for River Rch & Prof#=Warm Creek,DS of Noels Pond, 2
Up Type= 0
Dn Type= 0
Boundary for River Rch & Prof#=Warm Creek,DS of Noels Pond, 3
Up Type= 0
Dn Type= 0
Boundary for River Rch & Prof#=Warm Creek,DS of Noels Pond, 4
Up Type= 0
Dn Type= 0
Boundary for River Rch & Prof#=Warm Creek,DS of Noels Pond, 5
Up Type= 0
Dn Type= 0
Boundary for River Rch & Prof#=Warm Creek,DS of Noels Pond, 6
Up Type= 0
Dn Type= 0
Boundary for River Rch & Prof#=Warm Creek,DS of Noels Pond, 7
Up Type= 0
Dn Type= 0
Boundary for River Rch & Prof#=Warm Creek,DS of Noels Pond, 8
Up Type= 0
Dn Type= 0
Boundary for River Rch & Prof#=Warm Creek,DS of Noels Pond, 9
Up Type= 0
Dn Type= 0
Boundary for River Rch & Prof#=Warm Creek,DS of Noels Pond, 10
Up Type= 0
Dn Type= 0
Boundary for River Rch & Prof#=Warm Creek,DS of Noels Pond, 11
Up Type= 0
Dn Type= 0
Boundary for River Rch & Prof#=Warm Creek,DS of Noels Pond, 12
Up Type= 0
Dn Type= 0
Boundary for River Rch & Prof#=Warm Creek,DS of Noels Pond, 13
Up Type= 0
Dn Type= 0
Boundary for River Rch & Prof#=Warm Creek,DS of Noels Pond, 14
Up Type= 0
Dn Type= 0
Boundary for River Rch & Prof#=Warm Creek,DS of Noels Pond, 15
Up Type= 0
Dn Type= 0
Boundary for River Rch & Prof#=Warm Creek,DS of Noels Pond, 16
Up Type= 0
Dn Type= 0
Boundary for River Rch & Prof#=Warm Creek,DS of Noels Pond, 17
Up Type= 0
Dn Type= 0
Boundary for River Rch & Prof#=Warm Creek,DS of Noels Pond, 18
Up Type= 0
Dn Type= 0
Boundary for River Rch & Prof#=Warm Creek,US of Noels Pond, 1
Up Type= 3
Up Slope=0.008
Dn Type= 0
Boundary for River Rch & Prof#=Warm Creek,US of Noels Pond, 2
Up Type= 3
Up Slope=0.008
Dn Type= 0
Boundary for River Rch & Prof#=Warm Creek,US of Noels Pond, 3
Up Type= 3
Up Slope=0.008
Dn Type= 0
Boundary for River Rch & Prof#=Warm Creek,US of Noels Pond, 4
Up Type= 3
Up Slope=0.008
Dn Type= 0
Boundary for River Rch & Prof#=Warm Creek,US of Noels Pond, 5
Up Type= 3
Up Slope=0.008
Dn Type= 0
Boundary for River Rch & Prof#=Warm Creek,US of Noels Pond, 6
Up Type= 3
Up Slope=0.008
Dn Type= 0
Boundary for River Rch & Prof#=Warm Creek,US of Noels Pond, 7
Up Type= 3
Up Slope=0.008
Dn Type= 0
Boundary for River Rch & Prof#=Warm Creek,US of Noels Pond, 8
Up Type= 3
Up Slope=0.008
Dn Type= 0
Boundary for River Rch & Prof#=Warm Creek,US of Noels Pond, 9
Up Type= 3
Up Slope=0.008
Dn Type= 0
Boundary for River Rch & Prof#=Warm Creek,US of Noels Pond, 10
Up Type= 3
Up Slope=0.008
Dn Type= 0
Boundary for River Rch & Prof#=Warm Creek,US of Noels Pond, 11
Up Type= 3
Up Slope=0.008
Dn Type= 0
Boundary for River Rch & Prof#=Warm Creek,US of Noels Pond, 12
Up Type= 3
Up Slope=0.008
Dn Type= 0
Boundary for River Rch & Prof#=Warm Creek,US of Noels Pond, 13
Up Type= 3
Up Slope=0.008
Dn Type= 0
Boundary for River Rch & Prof#=Warm Creek,US of Noels Pond, 14
Up Type= 3
Up Slope=0.008
Dn Type= 0
Boundary for River Rch & Prof#=Warm Creek,US of Noels Pond, 15
Up Type= 3
Up Slope=0.008
Dn Type= 0
Boundary for River Rch & Prof#=Warm Creek,US of Noels Pond, 16
Up Type= 3
Up Slope=0.008
Dn Type= 0
Boundary for River Rch & Prof#=Warm Creek,US of Noels Pond, 17
Up Type= 3
Up Slope=0.008
Dn Type= 0
Boundary for River Rch & Prof#=Warm Creek,US of Noels Pond, 18
Up Type= 3
Up Slope=0.008
Dn Type= 0
DSS Import GetInterval= 0
DSS Import GetPeak= 0
DSS Import FillOption= 0
Storage Area Elev=Noel's Pond     , 18
    21.6    21.6    21.6    21.6    21.6    21.6    21.6    21.6    21.6    21.6
    21.6    21.6    21.6    21.6    21.6    21.6    21.6    21.6

--- Blanche_Brook.f02 (steady flow) ---

Flow Title=2005 Event
Program Version=4.00
Number of Profiles= 1
Profile Names=PF1
River Rch & RM=Blanche Brook,US of Confluence,4158.111
   107.5
River Rch & RM=Blanche Brook,US of Confluence,3523.008
   113.3
River Rch & RM=Blanche Brook,DS of Confluence,1727.041
   183.6
River Rch & RM=Warm Creek,DS of Noels Pond,2889.005
    71.1
River Rch & RM=Warm Creek,DS of Noels Pond,2436.619
    72.5
River Rch & RM=Warm Creek,US of Noels Pond,7941.430
    90.8
River Rch & RM=Warm Creek,US of Noels Pond,6943.722
   107.4
Boundary for River Rch & Prof#=Blanche Brook,US of Confluence, 1
Up Type= 3
Up Slope=0.015
Dn Type= 0
Boundary for River Rch & Prof#=Blanche Brook,DS of Confluence, 1
Up Type= 0
Dn Type= 1
Dn Known WS=0.78
Boundary for River Rch & Prof#=Warm Creek,DS of Noels Pond, 1
Up Type= 0
Dn Type= 0
Boundary for River Rch & Prof#=Warm Creek,US of Noels Pond, 1
Up Type= 3
Up Slope=0.008
Dn Type= 0
DSS Import GetInterval= 0
DSS Import GetPeak= 0
DSS Import FillOption= 0
Storage Area Elev=Noel's Pond     , 1
   23.75

--- Blanche_Brook.f04 (steady flow) ---

Flow Title=WS Profile #1 storage area CHECK
Program Version=4.00
Number of Profiles= 1
Profile Names=PF1
River Rch & RM=Blanche Brook,US of Confluence,4158.111
    2.74
River Rch & RM=Blanche Brook,US of Confluence,1767.620
    2.74
River Rch & RM=Blanche Brook,DS of Confluence,1727.041
    6.98
River Rch & RM=Warm Creek,DS of Noels Pond,2889.005
    4.24
River Rch & RM=Warm Creek,DS of Noels Pond,30.11789
    4.24
River Rch & RM=Warm Creek,US of Noels Pond,7941.430
    3.48
River Rch & RM=Warm Creek,US of Noels Pond,4880.005
    3.48
Boundary for River Rch & Prof#=Blanche Brook,US of Confluence, 1
Up Type= 3
Up Slope=0.015
Dn Type= 0
Boundary for River Rch & Prof#=Blanche Brook,DS of Confluence, 1
Up Type= 0
Dn Type= 1
Dn Known WS=0.78
Boundary for River Rch & Prof#=Warm Creek,DS of Noels Pond, 1
Up Type= 0
Dn Type= 0
Boundary for River Rch & Prof#=Warm Creek,US of Noels Pond, 1
Up Type= 3
Up Slope=0.008
Dn Type= 0
DSS Import GetInterval= 0
DSS Import GetPeak= 0
DSS Import FillOption= 0
Storage Area Elev=Noel's Pond     , 1
   21.64

--- Blanche_Brook.f05 (steady flow) ---

Flow Title=1/100 Year Flood
Program Version=4.00
Number of Profiles= 1
Profile Names=PF1
River Rch & RM=Blanche Brook,US of Confluence,4158.111
   207.2
River Rch & RM=Blanche Brook,US of Confluence,3523.008
   211.9
River Rch & RM=Blanche Brook,DS of Confluence,1727.041
     253
River Rch & RM=Warm Creek,DS of Noels Pond,2889.005
    58.2
River Rch & RM=Warm Creek,DS of Noels Pond,2436.619
    59.8
River Rch & RM=Warm Creek,US of Noels Pond,7941.430
     203
River Rch & RM=Warm Creek,US of Noels Pond,6943.722
   215.8
Boundary for River Rch & Prof#=Blanche Brook,US of Confluence, 1
Up Type= 3
Up Slope=0.015
Dn Type= 0
Boundary for River Rch & Prof#=Blanche Brook,DS of Confluence, 1
Up Type= 0
Dn Type= 1
Dn Known WS=0.78
Boundary for River Rch & Prof#=Warm Creek,DS of Noels Pond, 1
Up Type= 0
Dn Type= 0
Boundary for River Rch & Prof#=Warm Creek,US of Noels Pond, 1
Up Type= 3
Up Slope=0.008
Dn Type= 0
DSS Import GetInterval= 0
DSS Import GetPeak= 0
DSS Import FillOption= 0
Storage Area Elev=Noel's Pond     , 1
   23.52

--- Blanche_Brook.f06 (steady flow) ---

Flow Title=Tidal Sensitivity 1/100
Program Version=4.00
Number of Profiles= 1
Profile Names=PF1
River Rch & RM=Blanche Brook,US of Confluence,4158.111
   207.2
River Rch & RM=Blanche Brook,US of Confluence,3523.008
   211.9
River Rch & RM=Blanche Brook,DS of Confluence,1727.041
     253
River Rch & RM=Warm Creek,DS of Noels Pond,2889.005
    58.2
River Rch & RM=Warm Creek,DS of Noels Pond,2436.619
    59.8
River Rch & RM=Warm Creek,US of Noels Pond,7941.430
     203
River Rch & RM=Warm Creek,US of Noels Pond,6943.722
   215.8
Boundary for River Rch & Prof#=Blanche Brook,US of Confluence, 1
Up Type= 3
Up Slope=0.015
Dn Type= 0
Boundary for River Rch & Prof#=Blanche Brook,DS of Confluence, 1
Up Type= 0
Dn Type= 1
Dn Known WS=1.48
Boundary for River Rch & Prof#=Warm Creek,DS of Noels Pond, 1
Up Type= 0
Dn Type= 0
Boundary for River Rch & Prof#=Warm Creek,US of Noels Pond, 1
Up Type= 3
Up Slope=0.008
Dn Type= 0
DSS Import GetInterval= 0
DSS Import GetPeak= 0
DSS Import FillOption= 0
Storage Area Elev=Noel's Pond     , 1
   23.52

--- Blanche_Brook.f07 (steady flow) ---

Flow Title=1/100 Year Flood Q+10%
Program Version=4.00
Number of Profiles= 1
Profile Names=PF1
River Rch & RM=Blanche Brook,US of Confluence,4158.111
  227.92
River Rch & RM=Blanche Brook,US of Confluence,3523.008
  233.09
River Rch & RM=Blanche Brook,DS of Confluence,1727.041
   278.3
River Rch & RM=Warm Creek,DS of Noels Pond,2889.005
   64.02
River Rch & RM=Warm Creek,DS of Noels Pond,2436.619
   65.78
River Rch & RM=Warm Creek,US of Noels Pond,7941.430
   223.3
River Rch & RM=Warm Creek,US of Noels Pond,6943.722
  237.38
Boundary for River Rch & Prof#=Blanche Brook,US of Confluence, 1
Up Type= 3
Up Slope=0.015
Dn Type= 0
Boundary for River Rch & Prof#=Blanche Brook,DS of Confluence, 1
Up Type= 0
Dn Type= 1
Dn Known WS=0.78
Boundary for River Rch & Prof#=Warm Creek,DS of Noels Pond, 1
Up Type= 0
Dn Type= 0
Boundary for River Rch & Prof#=Warm Creek,US of Noels Pond, 1
Up Type= 3
Up Slope=0.008
Dn Type= 0
DSS Import GetInterval= 0
DSS Import GetPeak= 0
DSS Import FillOption= 0
Storage Area Elev=Noel's Pond     , 1
   23.52

--- Blanche_Brook.f08 (steady flow) ---

Flow Title=1/100 Year Flood Q-10%
Program Version=4.00
Number of Profiles= 1
Profile Names=PF1
River Rch & RM=Blanche Brook,US of Confluence,4158.111
  186.48
River Rch & RM=Blanche Brook,US of Confluence,3523.008
  190.71
River Rch & RM=Blanche Brook,DS of Confluence,1727.041
   227.7
River Rch & RM=Warm Creek,DS of Noels Pond,2889.005
   52.38
River Rch & RM=Warm Creek,DS of Noels Pond,2436.619
   53.82
River Rch & RM=Warm Creek,US of Noels Pond,7941.430
   182.7
River Rch & RM=Warm Creek,US of Noels Pond,6943.722
  194.22
Boundary for River Rch & Prof#=Blanche Brook,US of Confluence, 1
Up Type= 3
Up Slope=0.015
Dn Type= 0
Boundary for River Rch & Prof#=Blanche Brook,DS of Confluence, 1
Up Type= 0
Dn Type= 1
Dn Known WS=0.78
Boundary for River Rch & Prof#=Warm Creek,DS of Noels Pond, 1
Up Type= 0
Dn Type= 0
Boundary for River Rch & Prof#=Warm Creek,US of Noels Pond, 1
Up Type= 3
Up Slope=0.008
Dn Type= 0
DSS Import GetInterval= 0
DSS Import GetPeak= 0
DSS Import FillOption= 0
Storage Area Elev=Noel's Pond     , 1
   23.52

--- Blanche_Brook.f10 (steady flow) ---

Flow Title=Climate Change1
Program Version=4.00
Number of Profiles= 1
Profile Names=PF1
River Rch & RM=Blanche Brook,US of Confluence,4158.111
   322.9
River Rch & RM=Blanche Brook,US of Confluence,3523.008
   330.2
River Rch & RM=Blanche Brook,DS of Confluence,1727.041
     380
River Rch & RM=Warm Creek,DS of Noels Pond,2889.005
    90.7
River Rch & RM=Warm Creek,DS of Noels Pond,2436.619
    93.2
River Rch & RM=Warm Creek,US of Noels Pond,7941.430
   316.3
River Rch & RM=Warm Creek,US of Noels Pond,6943.722
   336.3
Boundary for River Rch & Prof#=Blanche Brook,US of Confluence, 1
Up Type= 3
Up Slope=0.015
Dn Type= 0
Boundary for River Rch & Prof#=Blanche Brook,DS of Confluence, 1
Up Type= 0
Dn Type= 1
Dn Known WS=0.78
Boundary for River Rch & Prof#=Warm Creek,DS of Noels Pond, 1
Up Type= 0
Dn Type= 0
Boundary for River Rch & Prof#=Warm Creek,US of Noels Pond, 1
Up Type= 3
Up Slope=0.008
Dn Type= 0
DSS Import GetInterval= 0
DSS Import GetPeak= 0
DSS Import FillOption= 0
Storage Area Elev=Noel's Pond     , 1
   24.37

--- Blanche_Brook.g01 (geometry) ---

Geom Title=GEOMETRY - FINAL
Program Version=4.00

Junct Name=J-1
Junct Desc=, 0 , 0 ,-1
Up River,Reach=Blanche Brook   ,US of Confluence
Up River,Reach=Warm Creek      ,DS of Noels Pond
Dn River,Reach=Blanche Brook   ,DS of Confluence
Junc L&A=0,0
Junc L&A=0,0

River Reach=Blanche Brook   ,US of Confluence
Reach XY= 30
298673.0128432875380843.39064783298707.1611273665380820.80871804
298777.6608106295380610.96200458298775.4576955275380578.46605683
298745.1648628775380494.74768295298738.5555175685380424.24799969
298841.5511485845380192.92091399298905.9922653175380102.59319481
298919.2109559275380027.68728134298916.4570620515379958.83993441
 298933.531204095379916.98074747299040.9330653095379871.81688788
 299159.350502045379806.82499237299181.9324318335379777.63371727
299229.2994065265379705.48169768 299234.807194285379680.69665279
299245.2719910145379609.64619075299231.5025216285379512.15834749
299235.3579730565379481.31473606299272.2601510125379443.31100056
299386.2713575395379404.20570749299447.4078016185379355.73717525
299479.3529705955379274.22191648 299472.743625295379200.41756057
299494.223997533  5379150.296692299518.4582636535379128.81631975
299599.9735224255379105.13283241299651.1959485475379065.47676057
 299736.015879975379024.71913119299764.8049859475379000.93201073

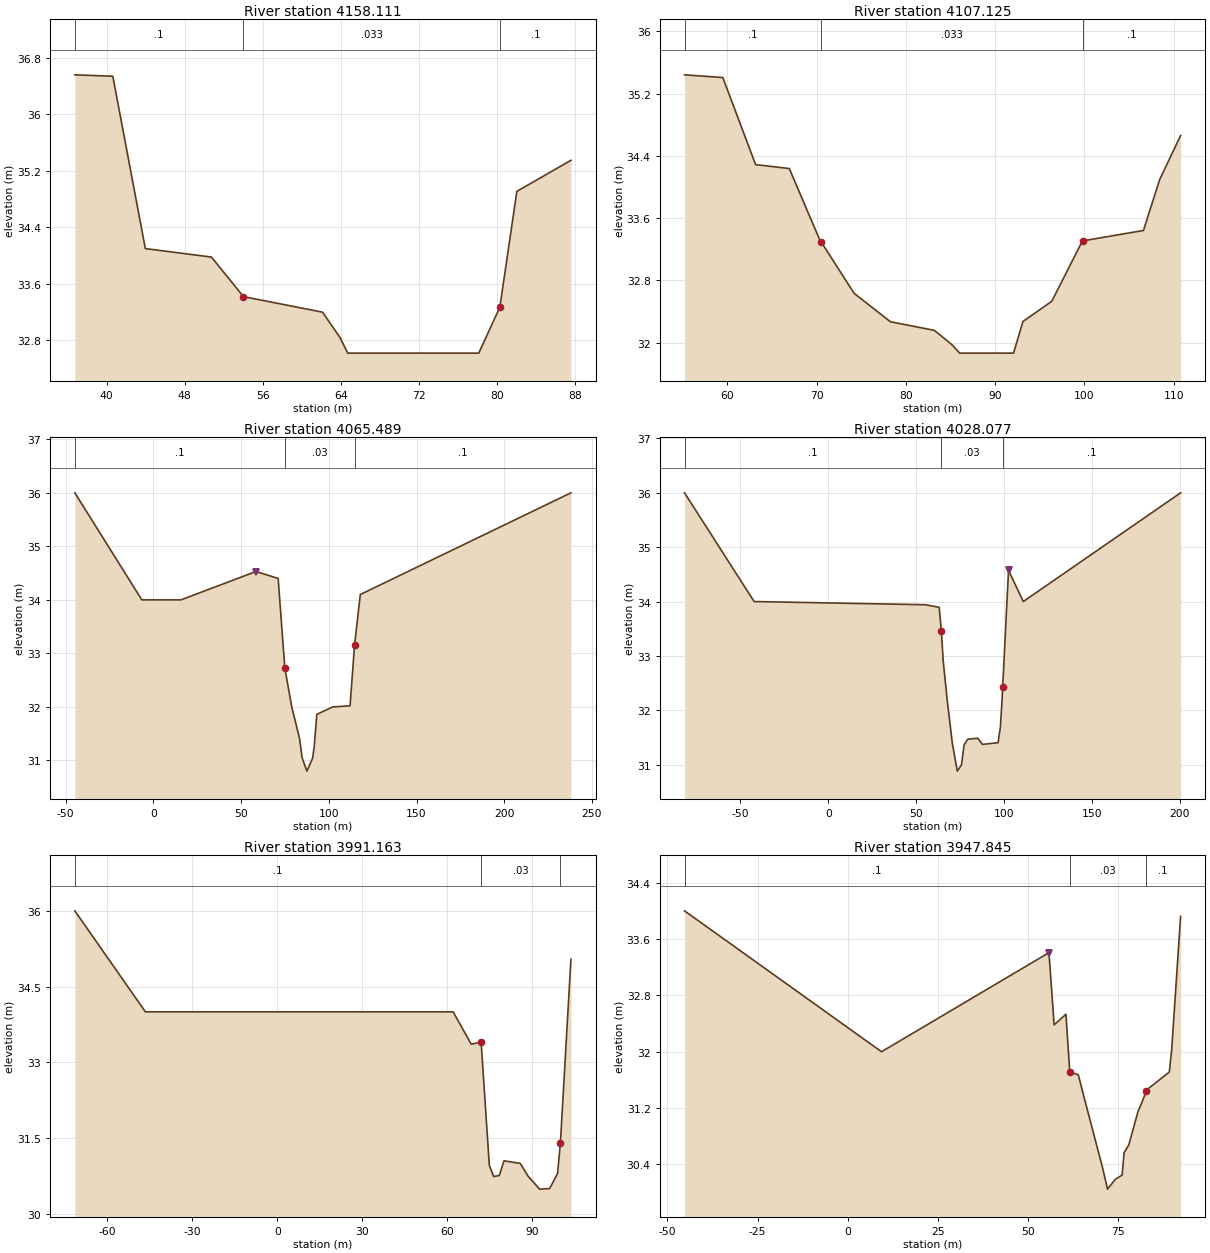
Type RM Length L Ch R = 1 ,4158.111,56.608,50.986,38.986
Node Photo=\HecRas Photos\BB39.JPG
BEGIN DESCRIPTION:
2008 Survey Section
END DESCRIPTION:
Node Name=BB39
XS GIS Cut Line= 2
298673.7152083715380853.34084345 298671.076662985380802.59958592
#Sta/Elev= 12
  36.751   36.56  40.641   36.54  43.971    34.1  50.741   33.98  54.021   33.42
  62.121    33.2  63.911   32.84  64.701   32.62  78.121   32.62  80.281   33.27
  82.021   34.91  87.561   35.35
#Mann= 3 , 0 , 0
  36.751      .1       0  54.021    .033       0  80.281      .1       0
Bank Sta=54.021,80.281
XS Rating Curve= 0 ,0
Exp/Cntr=0.3,0.1

Type RM Length L Ch R = 1 ,4107.125,48.237,41.636,33.727
BEGIN DESCRIPTION:
Interpolated Section
END DESCRIPTION:
Node Name=BB38a
XS GIS Cut Line= 2
298722.5515181345380829.68306117298690.4697829215380784.29914307
#Sta/Elev= 20
  55.202  35.442  59.493  35.407  63.166  34.288  66.938  34.238  70.459  33.293
  70.634  33.273  74.083  32.656  74.251   32.63  78.273  32.269  83.186  32.159
   85.16  31.975  86.032  31.866  92.064  31.866  93.117  32.273  96.346  32.532
   99.56  33.258  99.796  33.308 106.615  33.442 108.438  34.097  110.78  34.662
#Mann= 3 , 0 , 0
  55.202      .1       0  70.459    .033       0  99.796      .1       0
Bank Sta=70.459,99.796
XS Rating Curve= 0 ,0
Exp/Cntr=0.3,0.1

Type RM Length L Ch R = 1 ,4065.489,38.598,37.412,37.41
Node Photo=\HecRas Photos\BB38.JPG
BEGIN DESCRIPTION:
2008 Survey Section
END DESCRIPTION:
Node Name=BB38
XS GIS Cut Line= 4
298850.8290523585380826.26483342298755.4837313625380786.51361197
 298700.593541525380763.62888025298589.7419082375380717.41279144
#Sta/Elev= 18
 -44.826      36  -6.626      34  15.674      34  58.474   34.53  71.104    34.4
  74.894   32.73  78.794   32.01  83.304   31.41   84.75   31.05    87.5    30.8
   90.71   31.04  91.654   31.25  93.134   31.86 102.184      32 112.094   32.02
 114.654   33.15 117.944    34.1 238.044      36
#Mann= 3 , 0 , 0
 -44.826      .1       0  74.894     .03       0 114.654      .1       0
Levee=-1,58.474,34.53,0,,,,
Bank Sta=74.894,114.654
XS Rating Curve= 0 ,0
Exp/Cntr=0.3,0.1

Type RM Length L Ch R = 1 ,4028.077,36.768,36.914,37.219
BEGIN DESCRIPTION:
Interpolated Section
END DESCRIPTION:
Node Name=BB37a
XS GIS Cut Line= 4
298878.1226657375380797.74804548298751.6701636045380744.77469999
298708.0944586265380726.52001277298617.7975954235380688.69294846
#Sta/Elev= 23
 -81.786      36 -42.186      34  55.314  33.941  63.101  33.894  64.351  33.453
  65.438  32.889  67.842  32.137  70.622  31.382  71.835  31.165   73.42   30.88
   75.77  30.993  77.278  31.362  79.355  31.468  84.991  31.485    86.5  31.426
  87.672  31.372  96.598  31.403  97.924  31.691  98.906  32.204  99.206   32.42
 102.559  34.573 110.959      34 200.459      36
#Mann= 3 , 0 , 0
 -81.786      .1       0  64.351     .03       0  99.206      .1       0
Levee=0,,,-1,102.559,34.573,,
Bank Sta=64.351,99.206
XS Rating Curve= 0 ,0
Exp/Cntr=0.3,0.1

Type RM Length L Ch R = 1 ,3991.163,44.678,43.318,41.969
Node Photo=\HecRas Photos\BB37.JPG
BEGIN DESCRIPTION:
2008 Survey Section
END DESCRIPTION:
Node Name=BB37
XS GIS Cut Line= 4
298884.3314470575380771.79930821298764.9254170855380712.09629316
298759.2073460725380709.23725765298727.7416325775380693.50440091
#Sta/Elev= 16
   -71.5      36   -46.6      34      62      34  68.393   33.36  71.883    33.4
  74.773   30.96  76.293   30.74    78.3   30.76  79.943   31.05  85.683      31
  88.413   30.75    92.5   30.49   96.05    30.5  98.853    30.8  99.853    31.4
 103.573   35.04
#Mann= 3 , 0 , 0
   -71.5      .1       0  71.883     .03       0  99.853      .1       0
Bank Sta=71.883,99.853
XS Rating Curve= 0 ,0
Exp/Cntr=0.3,0.1

Type RM Length L Ch R = 1 ,3947.845,45.414,42.347,39.914
BEGIN DESCRIPTION:
Interpolated Section
END DESCRIPTION:
Node Name=BB36a
XS GIS Cut Line= 3
298881.6754758635380691.88643841298783.5906972145380667.79544014
298748.1588359315380659.09287772
#Sta/Elev= 20
 -45.238      34   9.362      32  55.762  33.406  57.194  32.382  60.474  32.532
  61.521  31.715  63.888  31.673  65.264  31.399  70.616  30.354   71.99   30.05
  74.155  30.189   76.05   30.25  76.576  30.565  77.889  30.677  80.383  31.141
  82.193  31.367  82.615  31.449  89.117  31.712   89.78  32.032  92.247  33.922
#Mann= 3 , 0 , 0
 -45.238      .1       0  61.521     .03       0  82.615      .1       0
Levee=-1,55.762,33.406,0,,,Levee 1,
Bank Sta=61.521,82.615
XS Rating Curve= 0 ,0
Exp/Cntr=0.3,0.1

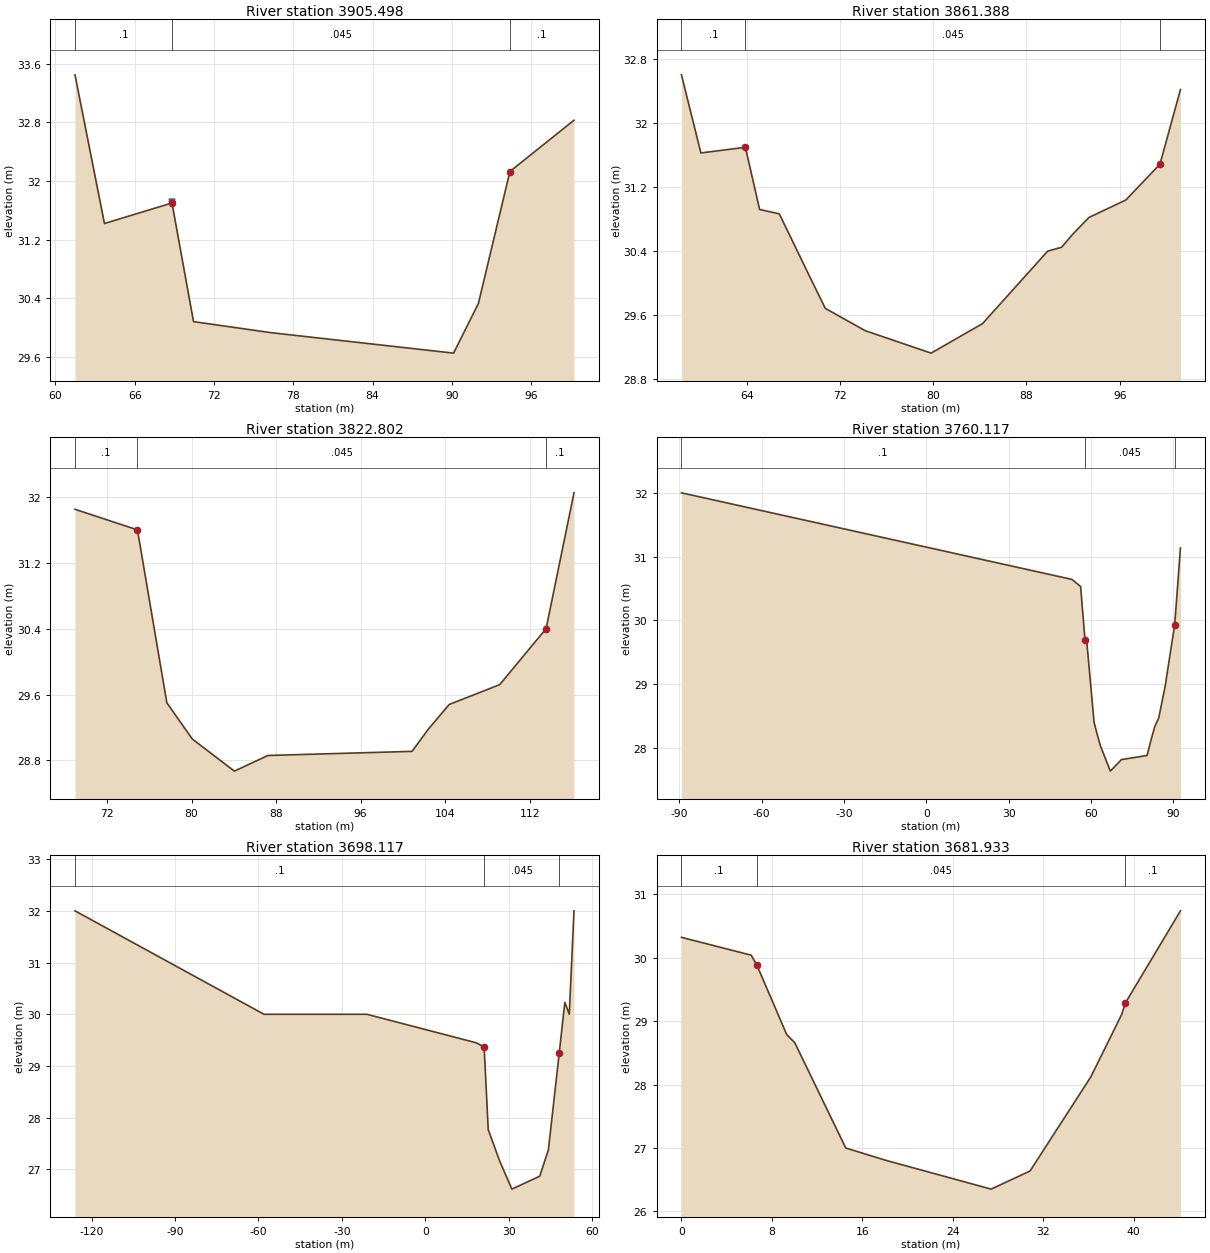
Type RM Length L Ch R = 1 ,3905.498,44.577,44.11,42.837
Node Photo=\HecRas Photos\BB36.JPG
BEGIN DESCRIPTION:
2008 Survey Section
END DESCRIPTION:
Node Name=BB36
XS GIS Cut Line= 2
298793.5339148415380621.95262812298755.8004084925380623.36763461
#Sta/Elev= 9
  61.485   33.45  63.715   31.42  68.825    31.7  70.455   30.08  76.285   29.93
  90.135   29.65  92.015   30.33  94.395   32.13  99.245   32.83
#Mann= 3 , 0 , 0
  61.485      .1       0  68.825    .045       0  94.395      .1       0
Levee=-1,68.84,31.71,0,,,Levee 1,
Bank Sta=68.825,94.395
XS Rating Curve= 0 ,0
Exp/Cntr=0.3,0.1

Type RM Length L Ch R = 1 ,3861.388,38.751,38.586,37.773
BEGIN DESCRIPTION:
Interpolated Section
END DESCRIPTION:
Node Name=BB35a
XS GIS Cut Line= 2
 298785.138542525380576.82051854298743.221058966 5380585.4732101
#Sta/Elev= 17
  58.408  32.597  60.075  31.623  63.894  31.693  65.112  30.918    66.8  30.864
  69.469  30.063  70.747  29.685  74.169  29.407   79.82  29.127  84.234  29.495
  89.822  30.399   91.01  30.447  92.035   30.62  93.354  30.818  96.529  31.037
  99.451  31.483 101.209  32.414
#Mann= 3 , 0 , 0
  58.408      .1       0  63.894    .045       0  99.451      .1       0
Bank Sta=63.894,99.451
XS Rating Curve= 0 ,0
Exp/Cntr=0.3,0.1

Type RM Length L Ch R = 1 ,3822.802,61.91,62.684,63.038
Node Photo=\HecRas Photos\BB35.JPG
BEGIN DESCRIPTION:
2008 Survey Section
END DESCRIPTION:
Node Name=BB35
XS GIS Cut Line= 2
298777.8696352115380538.01749845298731.3351375525380551.67608821
#Sta/Elev= 12
  68.973   31.85  74.883    31.6  77.663    29.5  80.073   29.06  84.053   28.67
   87.23   28.86 100.863   28.91 102.403   29.18 104.383   29.48 109.153   29.72
 113.543    30.4 116.183   32.05
#Mann= 3 , 0 , 0
  68.973      .1       0  74.883    .045       0 113.543      .1       0
Bank Sta=74.883,113.543
XS Rating Curve= 0 ,0
Exp/Cntr=0.3,0.1

Type RM Length L Ch R = 1 ,3760.117,58.614,62,62.497
BEGIN DESCRIPTION:
Interpolated Section
END DESCRIPTION:
Node Name=BB34a
XS GIS Cut Line= 3
 298910.061911855380453.42783499298769.9586677435380478.33507839
298731.0398285855380485.25398313
#Sta/Elev= 18
 -89.212      32  53.088  30.643  56.235  30.532   57.84  29.691  58.565  29.625
  61.141  28.405  62.332  28.207  63.374  28.045  67.062  27.639   71.11   27.82
  80.432  27.884  80.517  27.894  81.657  28.089  83.232  28.335  84.689   28.47
  87.026  28.966  90.517  29.935  92.617  31.135
#Mann= 3 , 0 , 0
 -89.212      .1       0   57.84    .045       0  90.517      .1       0
Bank Sta=57.84,90.517
XS Rating Curve= 0 ,0
Exp/Cntr=0.3,0.1

Type RM Length L Ch R = 1 ,3698.117,12.698,16.184,17.773
Node Photo=\HecRas Photos\BB34.JPG
BEGIN DESCRIPTION:
2008 Survey Section
END DESCRIPTION:
Node Name=BB34
XS GIS Cut Line= 4
298910.5745372965380453.29789571298768.7181217225380426.94205896
298737.3256638325380421.10958045298734.0811872315380420.50678152
#Sta/Elev= 14
    -126      32     -58      30     -21      30  18.284   29.45  21.184   29.37
  22.664   27.77  26.804   27.16  31.164   26.62  41.194   26.87  44.304   27.38
    48.2   29.25  50.214   30.23  51.814      30  53.514      32
#Mann= 3 , 0 , 0
    -126      .1       0  21.184    .045       0    48.2      .1       0
Bank Sta=21.184,48.2
XS Rating Curve= 0 ,0
Exp/Cntr=0.3,0.1

Type RM Length L Ch R = 1 ,3681.933,13.96,18.62,26.435
BEGIN DESCRIPTION:
Interpolated Section
END DESCRIPTION:
Node Name=BB33a
XS GIS Cut Line= 2
298775.5585656015380424.65428451298738.1059505735380401.29156003
#Sta/Elev= 13
       0  30.321   6.168   30.04   6.665  29.886   9.315  28.787  10.025   28.66
  14.535      27   18.12  26.804  27.393  26.352  30.838  26.638  36.212  28.121
  38.946  29.107  39.272  29.287  44.142  30.739
#Mann= 3 , 0 , 0
       0      .1       0   6.665    .045       0  39.272      .1       0
Bank Sta=6.665,39.272
XS Rating Curve= 0 ,0
Exp/Cntr=0.3,0.1

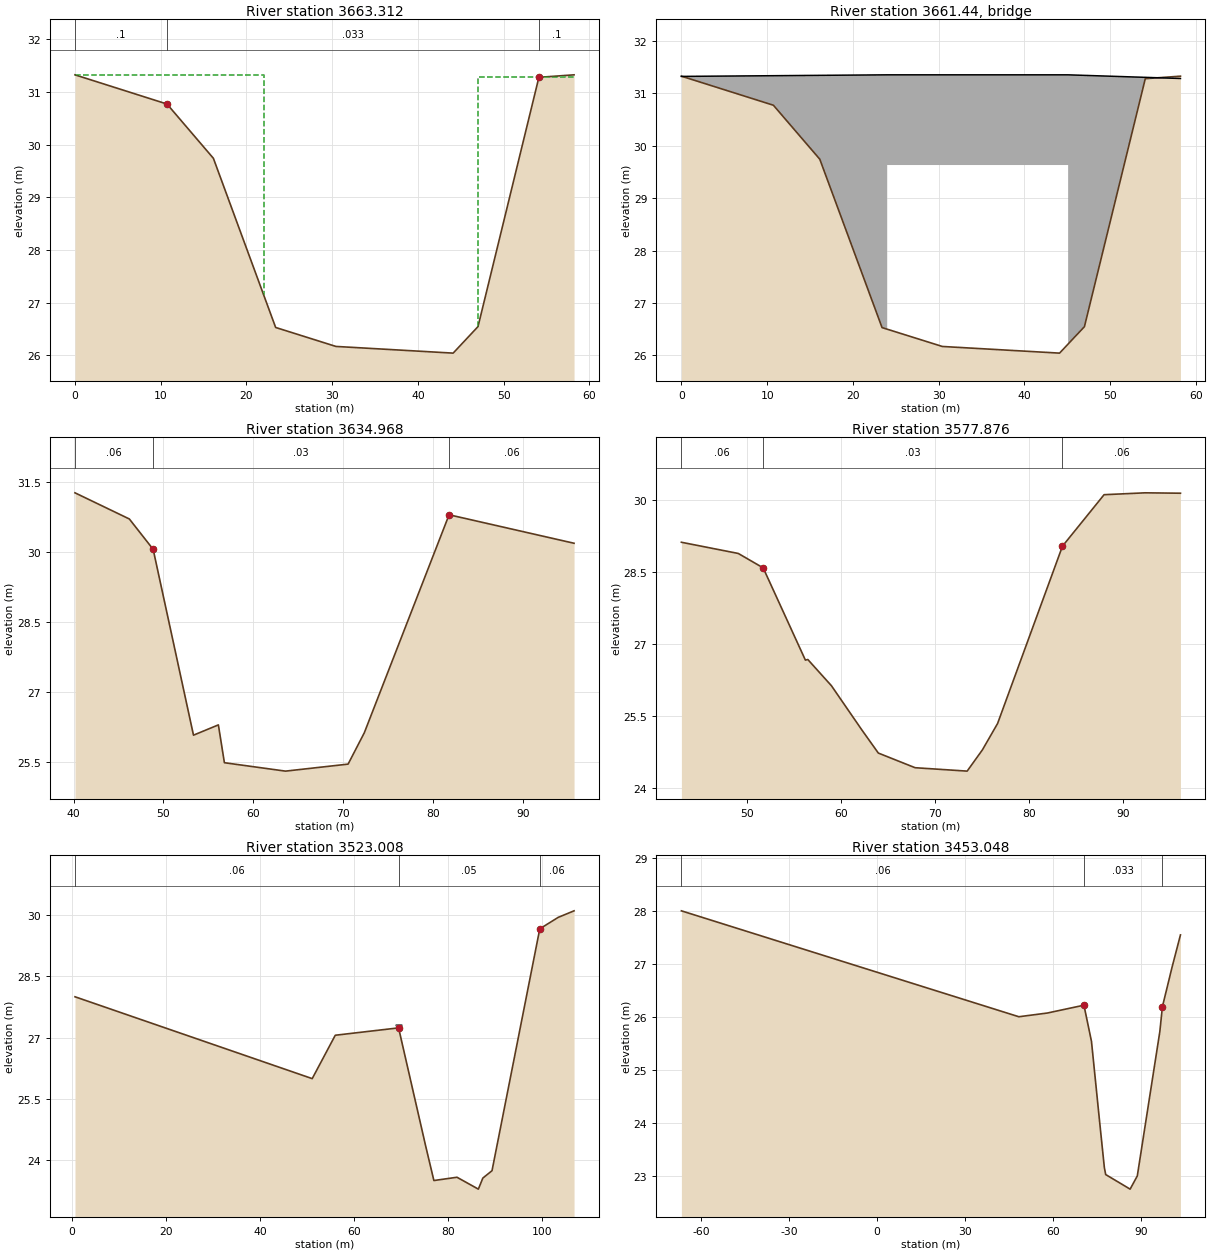
Type RM Length L Ch R = 1 ,3663.312,28.407,28.345,23.772
Node Photo=\HecRas Photos\BB33.JPG
BEGIN DESCRIPTION:
2008 Survey Section
END DESCRIPTION:
Node Name=BB33
XS GIS Cut Line= 3
298773.493453953 5380419.3569334298765.3284293535380414.64798742
298747.8633755695380369.10757782
#Sta/Elev= 9
       0 31.3243   10.73   30.77   16.14   29.74    23.4   26.53   30.43   26.17
    44.1  26.043      47 26.5466    54.131.27667    58.2 31.3243
#Mann= 3 , 0 , 0
       0      .1       0   10.73    .033       0    54.1      .1       0
#XS Ineff= 2 , 0
       0      22   31.32      47       0   31.29
Permanent Ineff=
       F       F
Bank Sta=10.73,54.1
XS Rating Curve= 0 ,0
Exp/Cntr=0.5,0.3

Type RM Length L Ch R = 3 ,3661.44 ,,,
Node Photo=\HecRas Photos\Hansen HW Bridge.JPG
BEGIN DESCRIPTION:
Hansen Highway Bridge
END DESCRIPTION:
Bridge Culvert--1,0,-1,-1, 0
Deck Dist Width WeirC Skew NumUp NumDn MinLoCord MaxHiCord MaxSubmerge Is_Ogee
1.88,19.66,1.6,0, 6, 6, , , 0.98, 0, 1,1,,
       0      24      24    45.1    45.1    58.2
   31.32   31.35   31.35   31.35   31.35   31.28
       0       0   29.63   29.63       0       0
   40.16      53      53    74.1    74.1    81.8
   31.27   31.35   31.35   31.35   31.35    30.8
       0       0   29.63    29.6       0       0
BR Coef=-1 , 0 , 0 ,, 0 ,,,0.8,-1,,0,
WSPro=,,,, 1 ,,,, 0 ,,,, 0 ,,,,-1 ,-1 ,-1 , 0 , 0 , 0 , 0 , 0
BC Design=,, 0 ,, 0 ,,,,,,
BC Use User HTab Curves=0
BC User HTab FreeFlow(D)= 0

Type RM Length L Ch R = 1 ,3634.968,58.975,57.091,54.669
Node Photo=\HecRas Photos\BB32.JPG
BEGIN DESCRIPTION:
2008 Survey Section
END DESCRIPTION:
Node Name=BB32
XS GIS Cut Line= 2
298775.0955149675380383.50380243298740.4601418835380322.35740304
#Sta/Elev= 11
  40.159   31.27  46.209   30.71  48.859   30.06  53.349   26.08  56.119    26.3
   56.79   25.49   63.59   25.31  70.559   25.46  72.359   26.13  81.799    30.8
  95.709   30.19
#Mann= 3 , 0 , 0
  40.159     .06       0  48.859     .03       0  81.799     .06       0
Bank Sta=48.859,81.799
XS Rating Curve= 0 ,0
Exp/Cntr=0.5,0.3

Type RM Length L Ch R = 1 ,3577.876,56.883,54.869,53.218
BEGIN DESCRIPTION:
Interpolated Section
END DESCRIPTION:
Node Name=BB31a
XS GIS Cut Line= 2
298803.4774883255380330.49852003298764.6843539725380289.85809356
#Sta/Elev= 16
  42.968  29.123  49.018   28.89  51.668   28.59  56.158   26.67  56.418  26.682
  58.928  26.137  62.178  25.213  63.918  24.735   67.83   24.43  73.368  24.359
  74.992  24.802  76.605   25.35  83.509  29.042  87.934  30.113  92.298  30.152
   96.06  30.144
#Mann= 3 , 0 , 0
  42.968     .06       0  51.668     .03       0  83.509     .06       0
Bank Sta=51.668,83.509
XS Rating Curve= 0 ,0
Exp/Cntr=0.3,0.1

Type RM Length L Ch R = 1 ,3523.008,69.291,69.959,70.085
Node Photo=\HecRas Photos\BB31.JPG
BEGIN DESCRIPTION:
2008 Survey Section
END DESCRIPTION:
Node Name=BB31
XS GIS Cut Line= 4
298879.427036222 5380305.1930059298832.3941906645380276.10690404
298832.3941906645380276.10690404298789.2477190425380249.42421764
#Sta/Elev= 13
    .688      28  51.088      26  55.988   27.06  69.438   27.24  75.198   24.35
  76.938   23.51   81.85   23.59  86.388    23.3   87.34   23.57  89.288   23.75
  99.438   29.66 103.348   29.94 106.718    30.1
#Mann= 3 , 0 , 0
    .688     .06       0  69.438     .05       0  99.438     .06       0
Levee=-1,69.438,27.24,0,,,,
Bank Sta=69.438,99.438
XS Rating Curve= 0 ,0
Exp/Cntr=0.3,0.1

Type RM Length L Ch R = 1 ,3453.048,69.452,69.952,70.023
BEGIN DESCRIPTION:
Interpolated Section
END DESCRIPTION:
Node Name=BB30a
XS GIS Cut Line= 3
298961.5736087425380280.98865938298857.952628618 5380211.4348508
298820.2367358365380186.11870359
#Sta/Elev= 14
 -66.777      28  48.323      26  58.023   26.07  70.524  26.218  73.097  25.535
  75.877  24.017  77.495   23.15  77.945   23.02  86.278  22.745  88.727  22.994
  96.401  25.715  97.299  26.191 100.602   26.94 103.448  27.545
#Mann= 3 , 0 , 0
 -66.777     .06       0  70.524    .033       0  97.299     .06       0
Bank Sta=70.524,97.299
XS Rating Curve= 0 ,0
Exp/Cntr=0.3,0.1