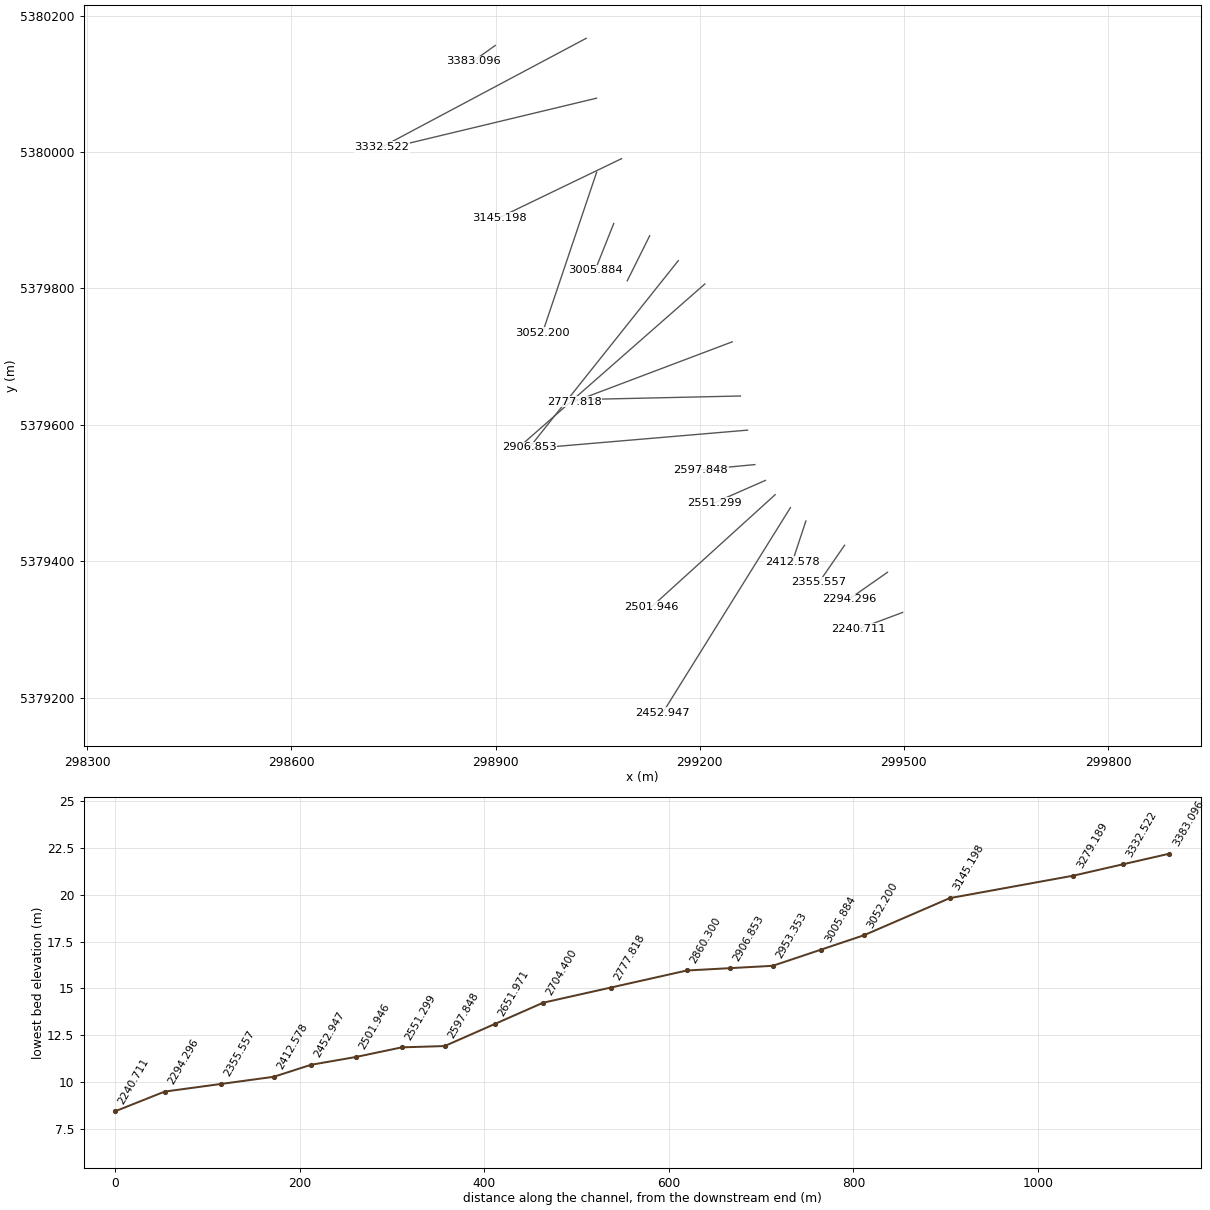
HEC-RAS study Blanche_Brook.prj: Stephenville Model

--- Blanche_Brook.g01 (geometry) --- (continued)

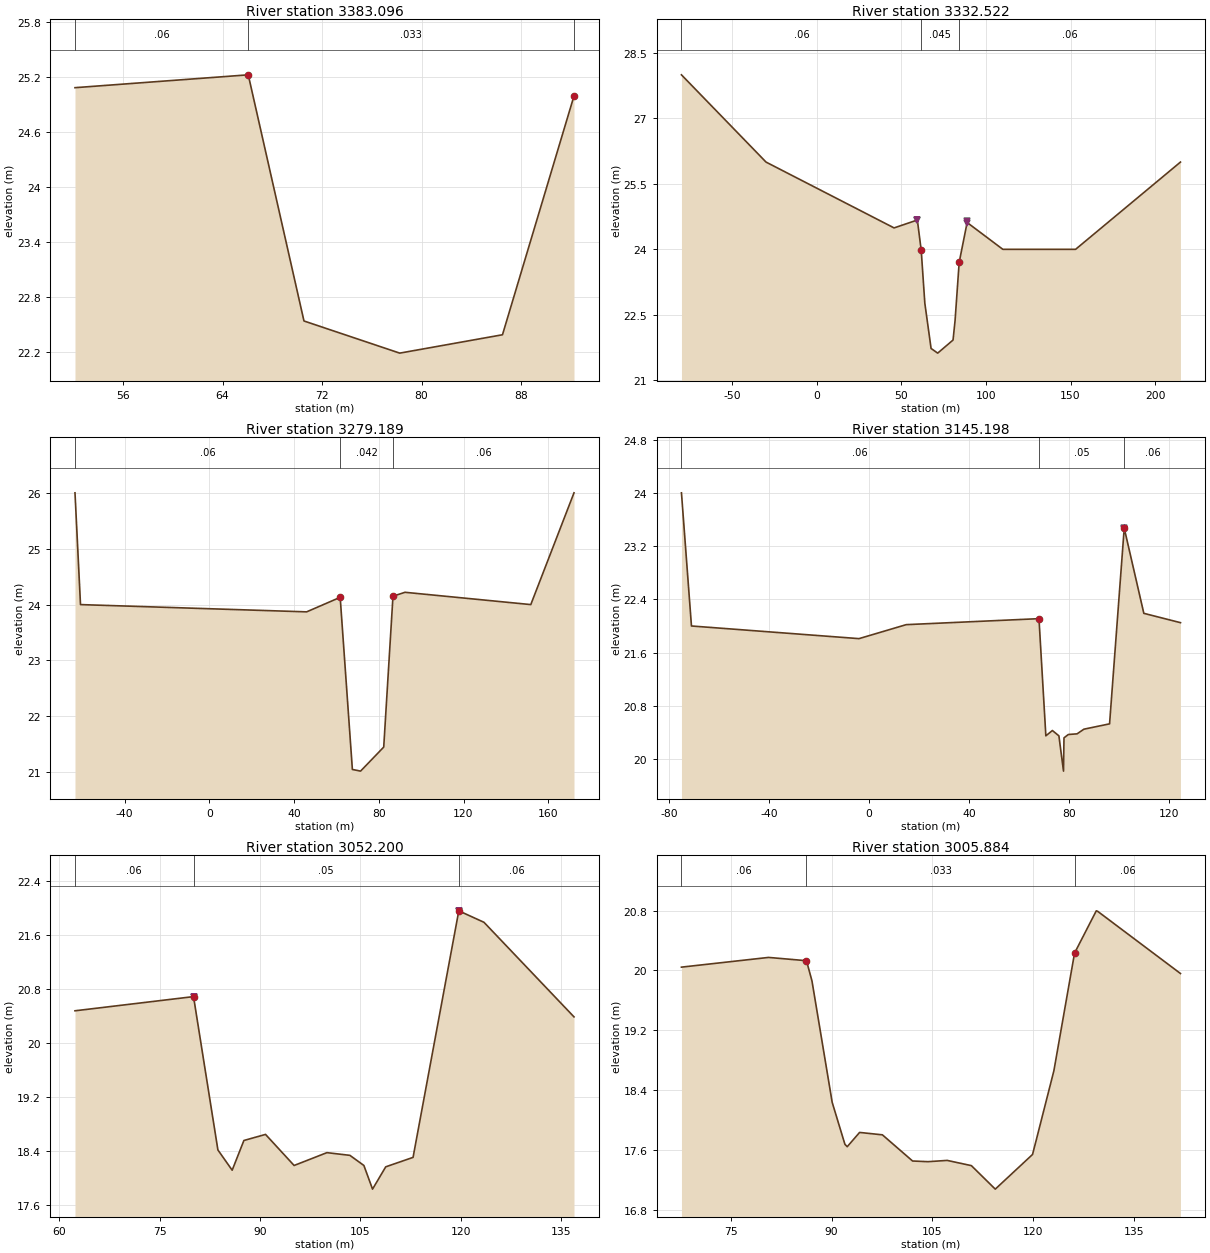
Type RM Length L Ch R = 1 ,3383.096,51.839,50.574,49.975
Node Photo=\HecRas Photos\BB30.JPG
BEGIN DESCRIPTION:
2008 Survey Section
END DESCRIPTION:
Node Name=BB30
XS GIS Cut Line= 3
298899.4708048295380156.47007593 298874.948404555380138.98051497
298866.806920213 5380133.1739469
#Sta/Elev= 6
   52.14   25.08   66.07   25.22   70.55   22.54   78.25   22.19   86.51   22.39
   92.26   24.99
#Mann= 3 , 0 , 0
   52.14     .06       0   66.07    .033       0   92.26     .06       0
Bank Sta=66.07,92.26
XS Rating Curve= 0 ,0
Exp/Cntr=0.3,0.1

Type RM Length L Ch R = 1 ,3332.522,55.876,53.334,52.416
BEGIN DESCRIPTION:
Interpolated Section
END DESCRIPTION:
Node Name=BB29a
XS GIS Cut Line= 5
299033.1001833255380166.93724838 298922.090959655380107.98019658
298857.4339517015380073.64082873 298844.186395325380066.60504519
298732.8097724545380007.45286744
#Sta/Elev= 15
     -80      28     -30      26  45.694  24.491  59.453  24.672  61.735   23.98
  63.878  22.764  67.572  21.728  71.483  21.621  80.556  21.921  81.746  22.364
   84.18  23.701   88.89  24.615     110      24     153      24     215      26
#Mann= 3 , 0 , 0
     -80     .06       0  61.735    .045       0   84.18     .06       0
Levee=-1,59.47,24.67,-1,88.95,24.64,Levee 2,Levee 3
Bank Sta=61.735,84.18
XS Rating Curve= 0 ,0
Exp/Cntr=0.3,0.1

Type RM Length L Ch R = 1 ,3279.189,132.549,133.991,134.931
Node Photo=\HecRas Photos\BB29.JPG
BEGIN DESCRIPTION:
2008 Survey Section
END DESCRIPTION:
Node Name=BB29
XS GIS Cut Line= 4
299048.2487726575380079.07483352298941.8571116835380053.59592442
298846.664155566 5380030.7989058298769.058536261 5380012.2137413
#Sta/Elev= 11
 -63.463      26 -60.863      24  45.937   23.87  61.767   24.13  67.527   21.05
  71.387   21.02  82.327   21.45  86.697   24.15  92.377   24.22 151.777      24
 172.177      26
#Mann= 3 , 0 , 0
 -63.463     .06       0  61.767    .042       0  86.697     .06       0
Bank Sta=61.767,86.697
XS Rating Curve= 0 ,0
Exp/Cntr=0.3,0.1

Type RM Length L Ch R = 1 ,3145.198,86.734,92.999,98.011
Node Photo=\HecRas Photos\BB28.JPG
BEGIN DESCRIPTION:
Interpolated Section
END DESCRIPTION:
Node Name=BB28
XS GIS Cut Line= 6
299084.9688441235379990.36292937298950.048134001  5379925.460582
298943.706669001  5379922.365416298938.788753001  5379920.047918
   298927.120776  5379914.339685298905.1691484545379903.80580976
#Sta/Elev= 17
     -75      24     -71      22      -4   21.81   14.88   22.02   67.97   22.11
   70.72   20.35   73.33   20.43   75.94   20.35   77.78   19.82   77.97   20.32
   79.71   20.37   83.21   20.38   85.94   20.45    96.2   20.53  102.06   23.47
   109.9   22.19  124.55   22.05
#Mann= 3 , 0 , 0
     -75     .06       0   67.97     .05       0  102.06     .06       0
Levee=0,,,-1,102.08,23.46,,Levee 4
Bank Sta=67.97,102.06
XS Rating Curve= 0 ,0
Exp/Cntr=0.3,0.1

Type RM Length L Ch R = 1 ,3052.200,46.777,46.316,45.575
Node Photo=\HecRas Photos\BB27.JPG
BEGIN DESCRIPTION:
2008 Survey Section
END DESCRIPTION:
Node Name=BB27
XS GIS Cut Line= 2
299048.4392323935379970.52160635298968.7777899655379734.72373676
#Sta/Elev= 16
  62.372   20.48  80.072   20.69  83.712   18.42  85.842   18.12  87.592   18.56
  90.822   18.65  95.092   18.19  99.992   18.38 103.422   18.34  105.51   18.19
 106.802   17.84  108.77   18.17 112.852   18.31 119.682   21.96 123.442   21.79
 136.882   20.39
#Mann= 3 , 0 , 0
  62.372     .06       0  80.072     .05       0 119.682     .06       0
Levee=-1,80.072,20.69,-1,119.682,21.96,,
Bank Sta=80.072,119.682
XS Rating Curve= 0 ,0
Exp/Cntr=0.3,0.1

Type RM Length L Ch R = 1 ,3005.884,53.665,52.531,51.414
BEGIN DESCRIPTION:
Interpolated Section
END DESCRIPTION:
Node Name=BB26a
XS GIS Cut Line= 2
299073.5626212485379895.29695044299046.0737119635379826.39617782
#Sta/Elev= 21
  67.683  20.044  80.634  20.174  86.268   20.13  87.085   19.86   90.09  18.236
  91.981  17.676  92.326  17.643  94.164  17.834  97.555  17.802 102.039  17.452
 104.334  17.443 107.184   17.46 110.785   17.39 114.334  17.076 119.871  17.539
 120.435  17.735 123.049  18.659 126.122  20.232 129.351  20.797 129.564   20.79
 141.865  19.959
#Mann= 3 , 0 , 0
  67.683     .06       0  86.268    .033       0 126.122     .06       0
Bank Sta=86.268,126.122
XS Rating Curve= 0 ,0
Exp/Cntr=0.3,0.1

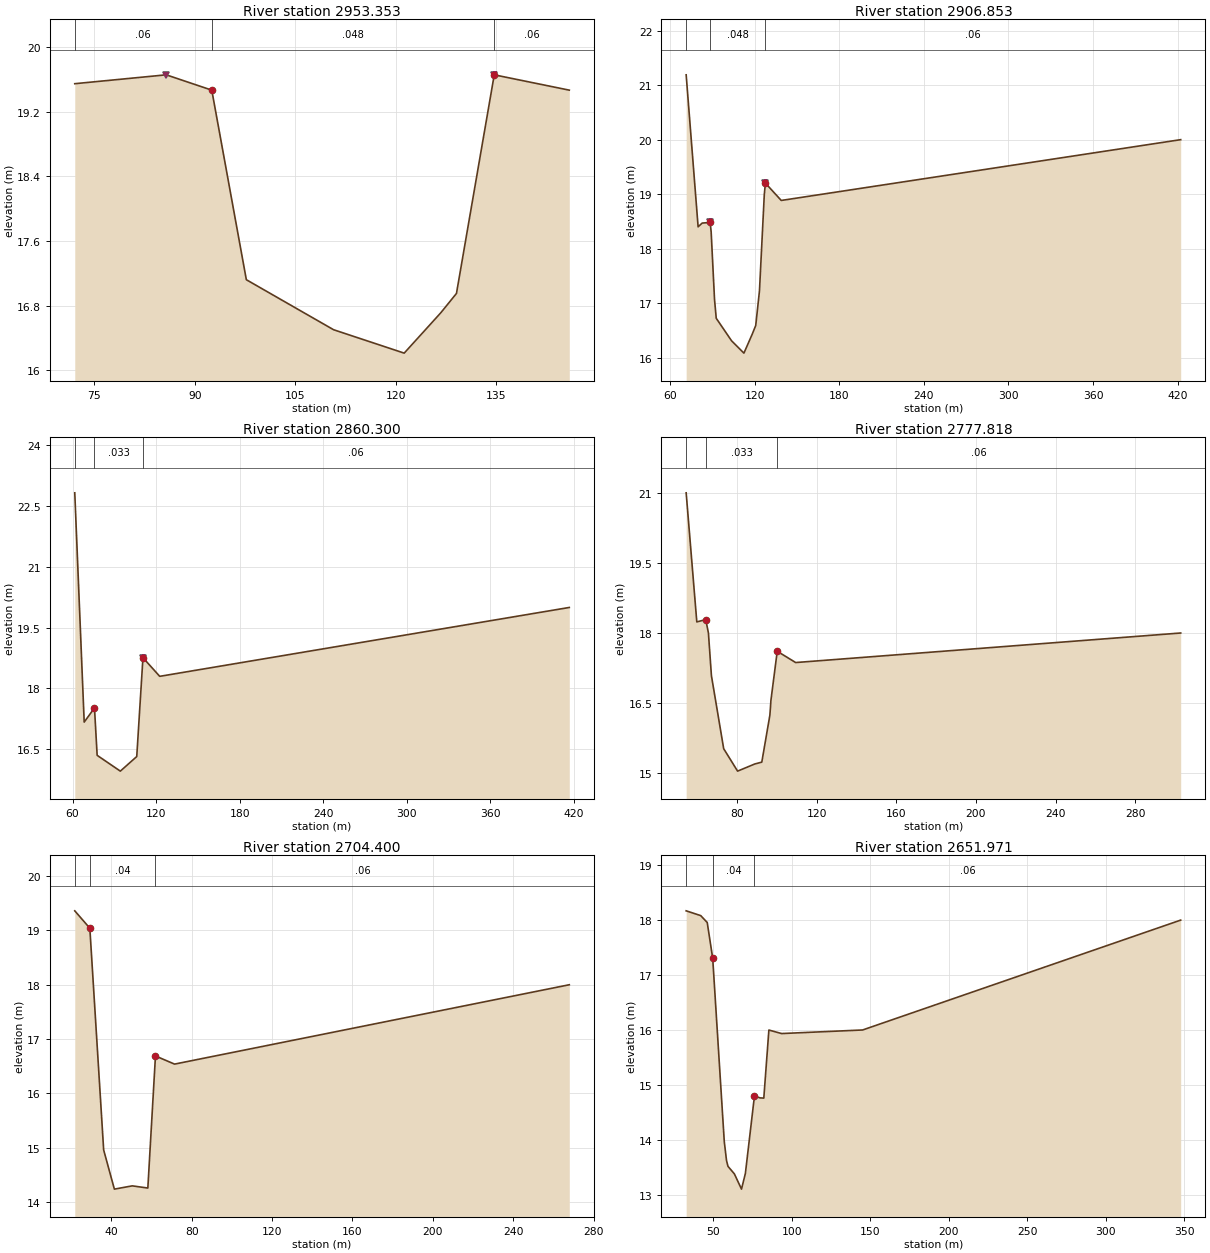
Type RM Length L Ch R = 1 ,2953.353,50.421,46.5,44.883
Node Photo=\HecRas Photos\BB26.JPG
BEGIN DESCRIPTION:
2008 Survey Section
END DESCRIPTION:
Node Name=BB26
XS GIS Cut Line= 2
299126.4199556795379877.36670024 299093.459059855379811.32461335
#Sta/Elev= 10
  72.061   19.55  85.711   19.66  92.511   19.47  97.671   17.12 110.691    16.5
 121.231   16.21 126.691   16.71 129.031   16.95 134.671   19.66 145.871   19.47
#Mann= 3 , 0 , 0
  72.061     .06       0  92.511    .048       0 134.671     .06       0
Levee=-1,85.711,19.66,-1,134.671,19.66,,
Bank Sta=92.511,134.671
XS Rating Curve= 0 ,0
Exp/Cntr=0.3,0.1

Type RM Length L Ch R = 1 ,2906.853,48.345,46.553,44.606
BEGIN DESCRIPTION:
Interpolated Section
END DESCRIPTION:
Node Name=BB25a
XS GIS Cut Line= 4
299168.4107590725379840.79985326299136.5495561975379800.87889946
299126.358653183 5379788.1100605298949.7005941955379566.76379677
#Sta/Elev= 16
  71.485  21.189  79.958  18.402  82.853   18.47  88.516  18.482  89.207  18.307
  91.597  17.068  92.814  16.724 103.657  16.312 112.435  16.085 118.299  16.431
 120.812  16.592 123.464  17.229  126.87  18.986 127.636  19.204 138.899  18.885
 422.099      20
#Mann= 3 , 0 , 0
  71.485     .06       0  88.516    .048       0 127.636     .06       0
Levee=-1,88.44,18.49,-1,127.636,19.204,Levee 5,
Bank Sta=88.516,127.636
XS Rating Curve= 0 ,0
Exp/Cntr=0.3,0.1

Type RM Length L Ch R = 1 ,2860.300,84.652,82.482,80.116
Node Photo=\HecRas Photos\BB25.JPG
BEGIN DESCRIPTION:
2008 Survey Section
END DESCRIPTION:
Node Name=BB25
XS GIS Cut Line= 3
299207.4483746195379806.59041551299161.5662235355379766.37791238
298940.3902609495379572.53261791
#Sta/Elev= 9
  61.552   22.83  68.322   17.17  75.712   17.52  77.622   16.35  94.272   15.96
 106.062   16.32 110.522   18.76 122.562    18.3 416.662      20
#Mann= 3 , 0 , 0
  61.552     .06       0  75.712    .033       0 110.522     .06       0
Levee=0,,,-1,110.522,18.76,,
Bank Sta=75.712,110.522
XS Rating Curve= 0 ,0
Exp/Cntr=0.3,0.1

Type RM Length L Ch R = 1 ,2777.818,74.613,73.418,70.108
BEGIN DESCRIPTION:
Interpolated Section
END DESCRIPTION:
Node Name=BB24a
XS GIS Cut Line= 3
299247.6661660225379721.71371389299196.204875676 5379702.3028763
299015.2496107375379634.04782022
#Sta/Elev= 14
  54.467  20.994  59.813  18.237  64.298  18.286  65.648  18.001  67.156  17.089
  73.317  15.529  80.304   15.05  88.963  15.203  92.458  15.242  96.522  16.246
  97.055  16.565 100.213   17.61 109.467  17.369 302.867      18
#Mann= 3 , 0 , 0
  54.467     .06       0  64.298    .033       0 100.213     .06       0
Bank Sta=64.298,100.213
XS Rating Curve= 0 ,0
Exp/Cntr=0.3,0.1

Type RM Length L Ch R = 1 ,2704.400,52.02,52.429,52.896
Node Photo=\HecRas Photos\BB24.JPG
BEGIN DESCRIPTION:
2008 Survey Section
END DESCRIPTION:
Node Name=BB24
XS GIS Cut Line= 3
299259.6692445625379642.28641383299210.0312172815379641.18334655
 299013.679691635379636.81997929
#Sta/Elev= 9
  21.842   19.36  29.342   19.04  36.222   14.96  41.552   14.24  50.442    14.3
  58.202   14.26  61.992   16.69  71.492   16.54 267.892      18
#Mann= 3 , 0 , 0
  21.842     .06       0  29.342     .04       0  61.992     .06       0
Bank Sta=29.342,61.992
XS Rating Curve= 0 ,0
Exp/Cntr=0.3,0.1

Type RM Length L Ch R = 1 ,2651.971,52.676,54.123,52.466
BEGIN DESCRIPTION:
Interpolated Section
END DESCRIPTION:
Node Name=BB23a
XS GIS Cut Line= 4
299270.1266359735379592.20213984299209.549906461 5379587.0466735
299158.1357784115379582.67100303 298956.265536075379565.49055688
#Sta/Elev= 18
  32.642  18.169  41.906  18.082  46.057  17.957  49.555  17.304  56.922  13.968
  58.363  13.621    59.3  13.517  63.347  13.381  67.897  13.103  70.366  13.389
   75.48  14.637  76.167    14.8   79.67  14.764    82.1   14.76  85.333  15.999
  93.438  15.935 145.038      16 347.638      18
#Mann= 3 , 0 , 0
  32.642     .06       0  49.555     .04       0  76.167     .06       0
Bank Sta=49.555,76.167
XS Rating Curve= 0 ,0
Exp/Cntr=0.3,0.1

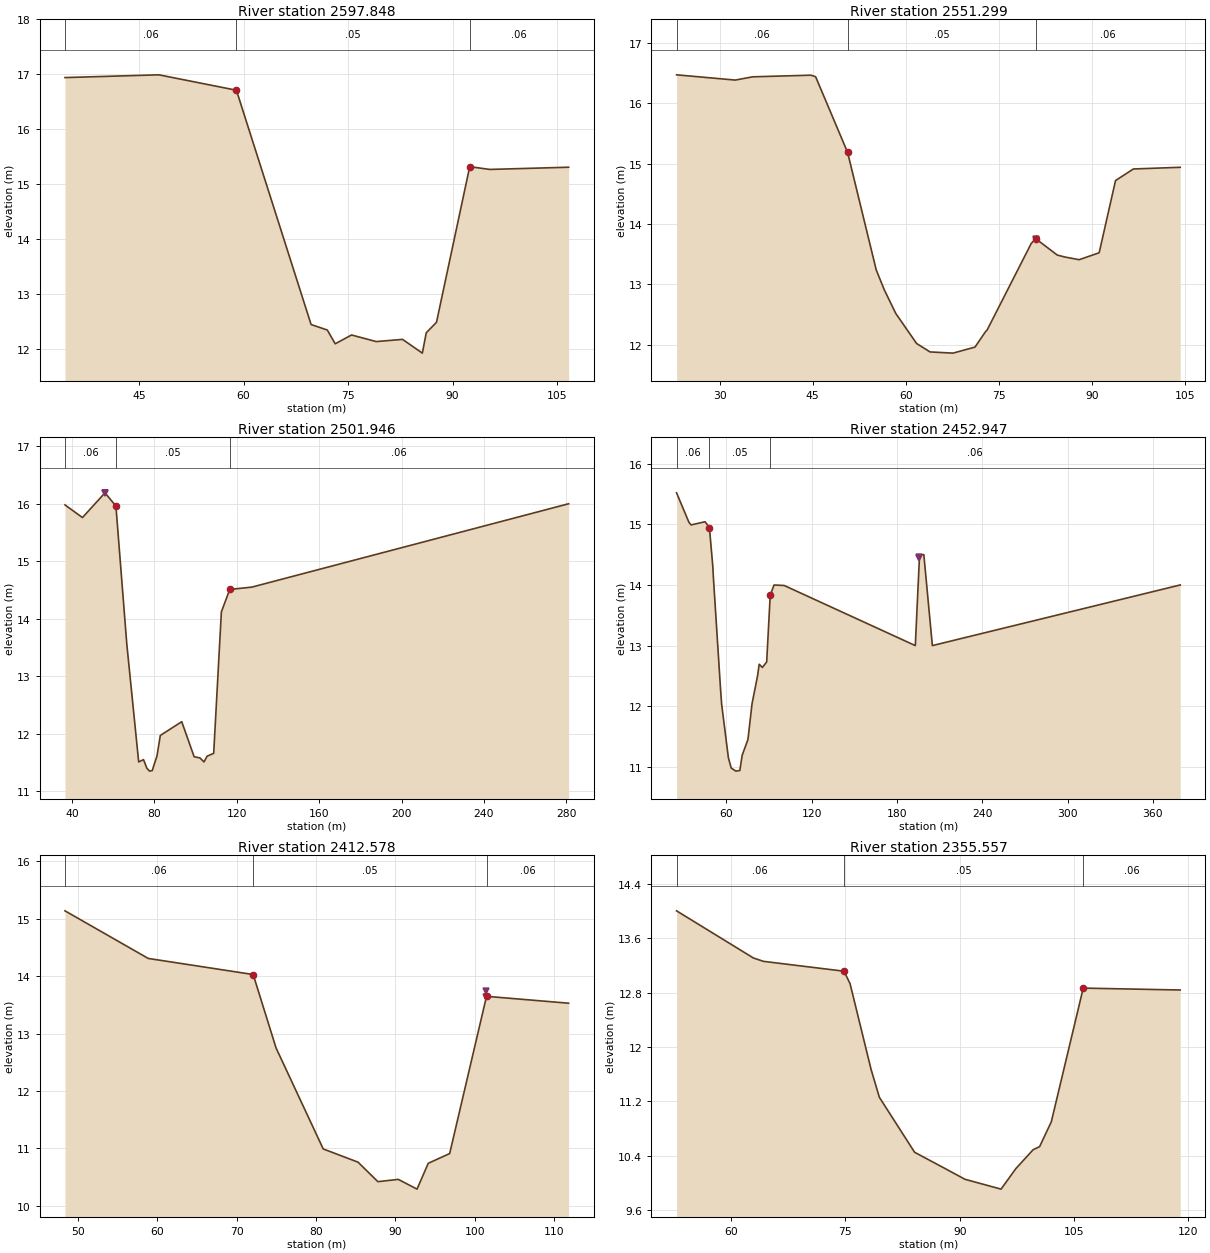
Type RM Length L Ch R = 1 ,2597.848,44.068,46.55,47.373
Node Photo=\HecRas Photos\BB23 .JPG
BEGIN DESCRIPTION:
2008 Survey Section
END DESCRIPTION:
Node Name=BB23
XS GIS Cut Line= 2
299280.9740230735379541.65443018299201.2944488485379534.09224837
#Sta/Elev= 15
  34.371   16.94  47.851   16.99  58.981   16.71  69.701   12.45   72.03   12.35
  73.161    12.1   75.51   12.26  79.051   12.14   82.83   12.18  85.671   11.93
   86.23    12.3  87.701   12.49  92.471   15.32  95.351   15.27 106.671   15.31
#Mann= 3 , 0 , 0
  34.371     .06       0  58.981     .05       0  92.471     .06       0
Bank Sta=58.981,92.471
XS Rating Curve= 0 ,0
Exp/Cntr=0.3,0.1

Type RM Length L Ch R = 1 ,2551.299,47.165,49.353,50.132
BEGIN DESCRIPTION:
Interpolated Section
END DESCRIPTION:
Node Name=BB22a
XS GIS Cut Line= 2
299296.470358839 5379518.4881891299222.0654506495379485.91949263
#Sta/Elev= 24
  23.057  16.474  32.526  16.387  35.339  16.441  44.727  16.468  45.481  16.443
  50.638  15.188  55.248  13.242  56.527  12.916  58.401  12.519   61.76   12.02
   63.93   11.88   67.64   11.86   71.18   11.96  72.882  12.216  73.132  12.242
  80.241  13.676  80.964  13.758  84.448  13.486  85.693  13.453  87.983  13.409
  91.206  13.524  93.844  14.721  96.721  14.913 104.278  14.941
#Mann= 3 , 0 , 0
  23.057     .06       0  50.638     .05       0  80.964     .06       0
Levee=0,,,-1,81.06,13.74,,Levee 6
Bank Sta=50.638,80.964
XS Rating Curve= 0 ,0
Exp/Cntr=0.3,0.1

Type RM Length L Ch R = 1 ,2501.946,48.982,48.999,49.706
Node Photo=\HecRas Photos\BB22.JPG
BEGIN DESCRIPTION:
2008 Survey Section
END DESCRIPTION:
Node Name=BB22
XS GIS Cut Line= 3
299310.7872617965379497.53829081299243.5765624745379436.66460028
 299129.582385215379333.41844544
#Sta/Elev= 23
   36.65   15.98   45.14   15.76   56.08   16.19   61.38   15.96   66.66   13.56
   72.43   11.51   74.78   11.55   76.41    11.4   77.72   11.35   79.02   11.36
   79.89   11.46    81.3   11.61   82.92   11.97   93.33   12.21   99.35    11.6
  102.17   11.58  104.13   11.51  105.65   11.61  108.84   11.66  112.57   14.12
  116.64   14.51  127.33   14.55  281.13      16
#Mann= 3 , 0 , 0
   36.65     .06       0   61.38     .05       0  116.64     .06       0
Levee=-1,56.26,16.18,0,,,Levee 7,
Bank Sta=61.38,116.64
XS Rating Curve= 0 ,0
Exp/Cntr=0.3,0.1

Type RM Length L Ch R = 1 ,2452.947,38.657,40.37,41.644
BEGIN DESCRIPTION:
Interpolated Section
END DESCRIPTION:
Node Name=BB21a
XS GIS Cut Line= 4
299333.1367144015379478.42671757299293.0598857775379414.16559581
299237.8935478975379325.70922645 299145.60479903 5379177.7289912
#Sta/Elev= 29
  24.924  15.519  33.683   15.03  35.156   14.99   44.97  15.042   48.04  14.947
  50.437  14.303  50.849  14.118  55.885  12.277  56.643  12.033   61.39   11.15
   63.39   10.98   66.65   10.93   69.46   10.94  71.067   11.19  75.158  11.453
  78.003  12.038  81.968  12.508  83.056  12.693  85.299  12.639  88.338  12.731
  90.823  13.833  93.535  13.999 100.658  13.991 192.907      13 195.907    14.5
 197.407    14.5 198.907    14.5 204.907      13 379.307      14
#Mann= 3 , 0 , 0
  24.924     .06       0   48.04     .05       0  90.823     .06       0
Levee=0,,,-1,195.8,14.46,,Levee 8
Bank Sta=48.04,90.823
XS Rating Curve= 0 ,0
Exp/Cntr=0.3,0.1

Type RM Length L Ch R = 1 ,2412.578,58.965,57.021,55.229
Node Photo=\HecRas Photos\BB21.JPG
BEGIN DESCRIPTION:
2008 Survey Section
END DESCRIPTION:
Node Name=BB21
XS GIS Cut Line= 2
299355.9413159975379458.91732217299335.9667231285379398.72542823
#Sta/Elev= 13
  48.389   15.14  58.879   14.31  72.089   14.03  74.969   12.75  80.909   10.99
   85.29   10.76  87.789   10.42   90.36   10.46  92.719   10.29   94.13   10.74
  96.829   10.91 101.469   13.65 111.809   13.53
#Mann= 3 , 0 , 0
  48.389     .06       0  72.089     .05       0 101.469     .06       0
Levee=0,,,-1,101.45,13.74,,Levee 8
Bank Sta=72.089,101.469
XS Rating Curve= 0 ,0
Exp/Cntr=0.3,0.1

Type RM Length L Ch R = 1 ,2355.557,64.066,61.26,58.537
BEGIN DESCRIPTION:
Interpolated Section
END DESCRIPTION:
Node Name=BB20a
XS GIS Cut Line= 2
299412.8087155925379423.35995447299375.2075090475379369.00168849
#Sta/Elev= 18
  52.843  14.007  62.919  13.313  64.247  13.263  74.813  13.118  75.608  12.936
  78.374   11.67  79.458  11.261   84.08  10.452  88.016  10.216  90.688  10.054
  95.423   9.909   97.36   10.21  99.632  10.489 100.486  10.535  102.02    10.9
 106.202  12.865  106.22  12.869 118.939  12.841
#Mann= 3 , 0 , 0
  52.843     .06       0  74.813     .05       0  106.22     .06       0
Bank Sta=74.813,106.22
XS Rating Curve= 0 ,0
Exp/Cntr=0.3,0.1

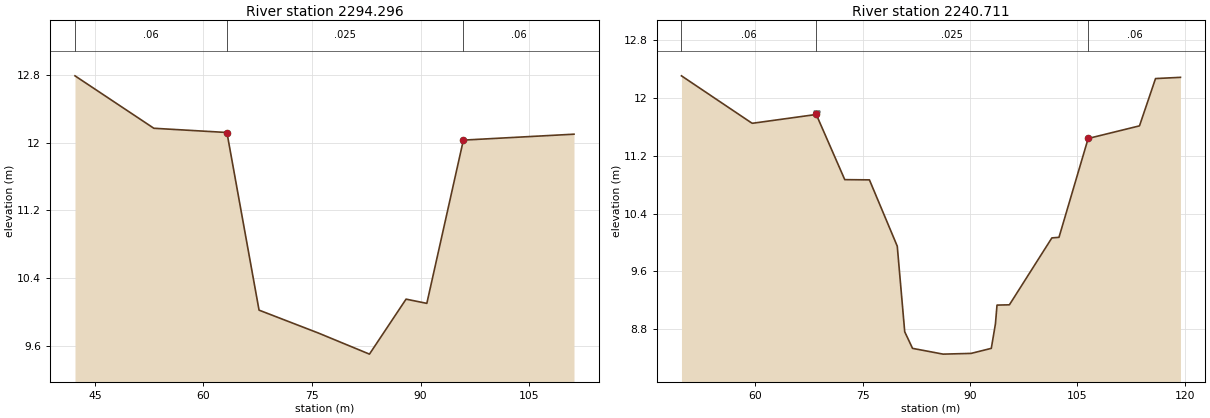
Type RM Length L Ch R = 1 ,2294.296,55.328,53.585,51.797
Node Photo=\HecRas Photos\BB20.JPG
BEGIN DESCRIPTION:
2008 Survey Section
END DESCRIPTION:
Node Name=BB20
XS GIS Cut Line= 2
299475.8415631235379383.70187447299419.2919906735379344.21755761
#Sta/Elev= 10
  42.241   12.79  53.141   12.17  63.241   12.12  67.681   10.02  75.861    9.75
  82.941     9.5  88.001   10.15  90.871    10.1  95.921   12.03 111.211    12.1
#Mann= 3 , 0 , 0
  42.241     .06       0  63.241    .025       0  95.921     .06       0
Bank Sta=63.241,95.921
XS Rating Curve= 0 ,0
Exp/Cntr=0.3,0.1

Type RM Length L Ch R = 1 ,2240.711,47.275,45.868,43.163
BEGIN DESCRIPTION:
Interpolated Section
END DESCRIPTION:
Node Name=BB19a
XS GIS Cut Line= 2
299498.0517355245379324.77532383299432.6901053495379300.42003958
#Sta/Elev= 21
  49.661   12.31  59.442  11.658  59.595  11.652  68.504  11.774  72.488   10.87
  75.936  10.867  79.827   9.947   80.87    8.76   81.96    8.53   86.23    8.45
   90.14    8.46   92.97    8.53   93.55    8.87   93.77    9.13  95.502   9.134
 101.439  10.062 102.433   10.07 106.511  11.441 113.685  11.616 115.928  12.272
 119.413  12.289
#Mann= 3 , 0 , 0
  49.661     .06       0  68.504    .025       0 106.511     .06       0
Levee=-1,68.55,11.78,0,,,Levee 9,
Bank Sta=68.504,106.511
XS Rating Curve= 0 ,0
Exp/Cntr=0.3,0.1