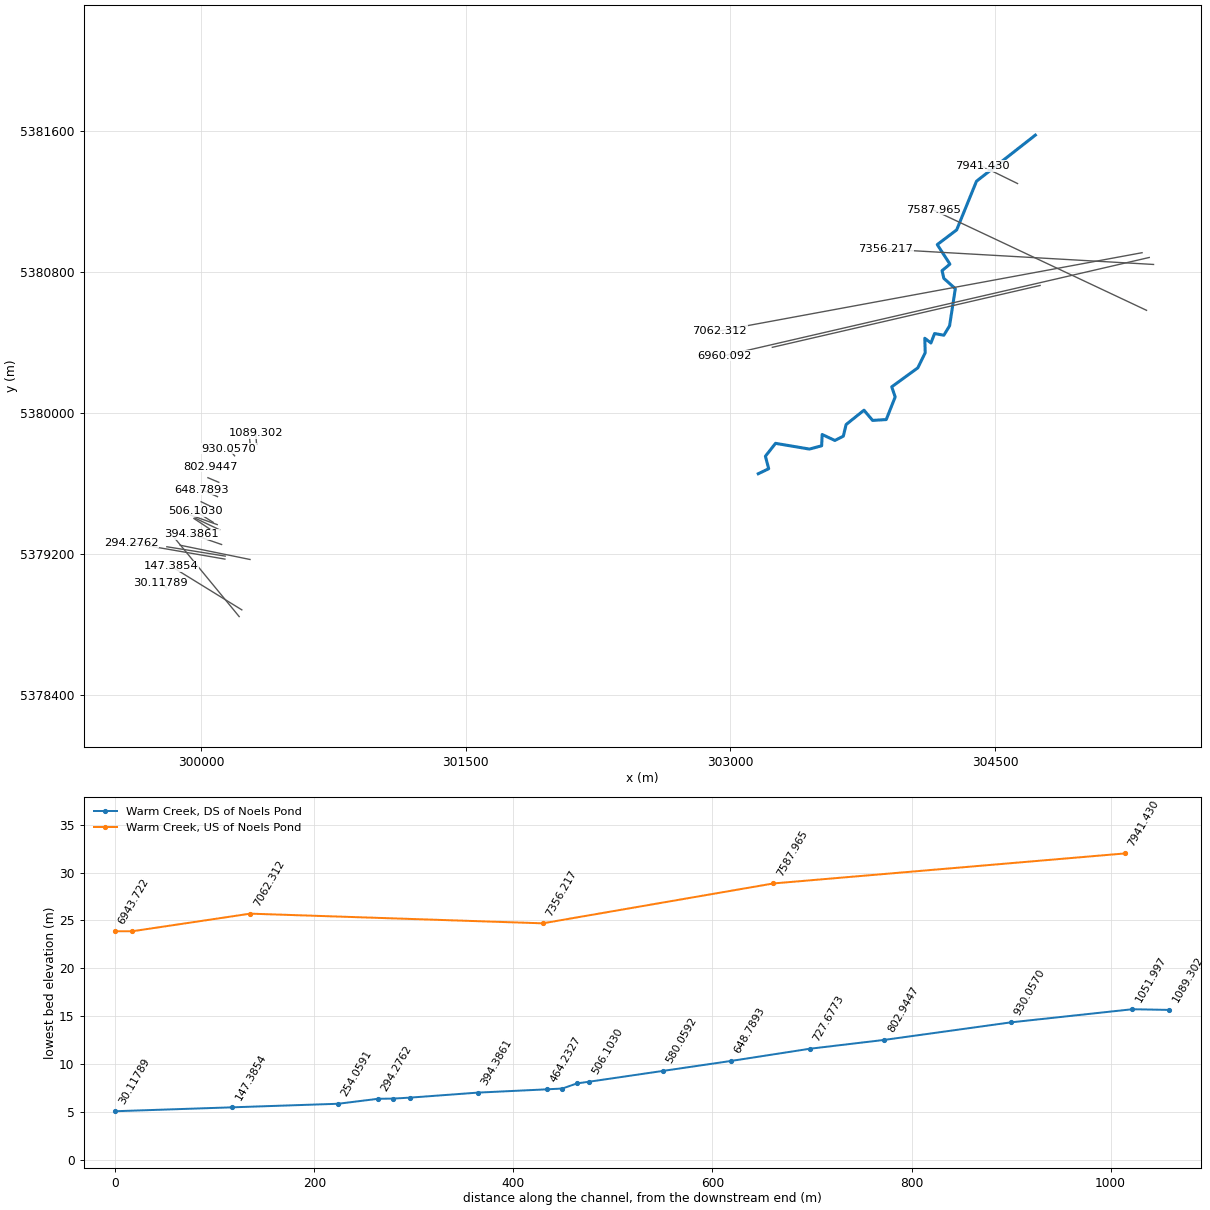
HEC-RAS study Blanche_Brook.prj: Stephenville Model

--- Blanche_Brook.g01 (geometry) --- (continued)

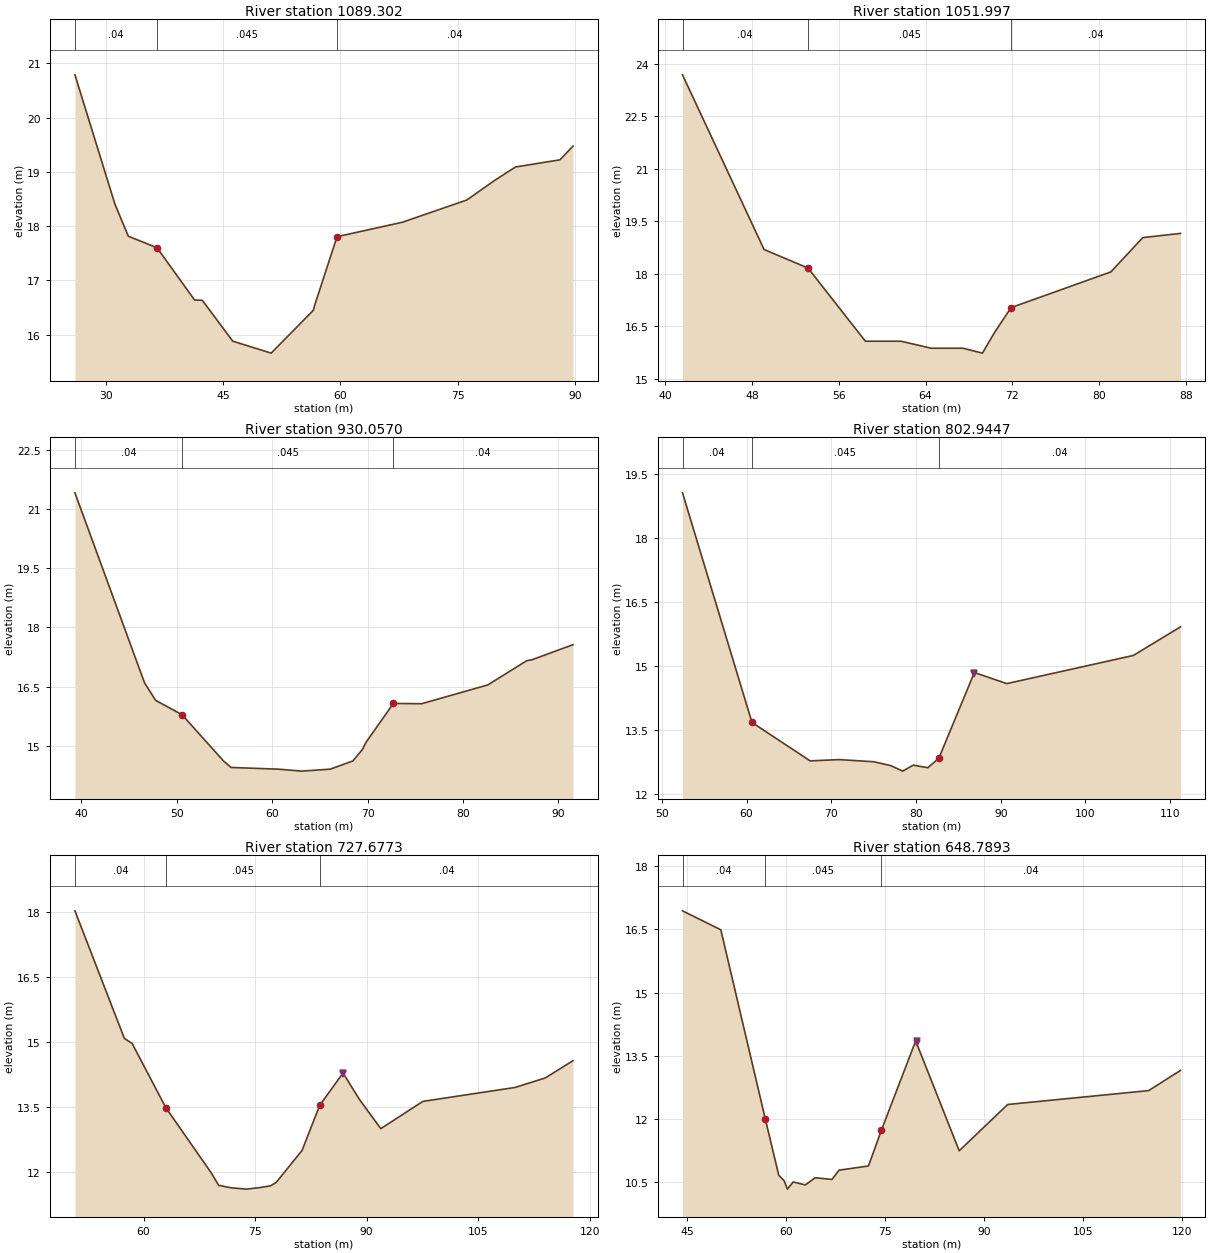
Type RM Length L Ch R = 1 ,1089.302,36.577,37.305,37.535
BEGIN DESCRIPTION:
Interpolated Section
END DESCRIPTION:
Node Name=W12a
XS GIS Cut Line= 2
300314.0330639555379822.61789455300309.247893518 5379886.1923018
#Sta/Elev= 18
  26.012  20.791  31.138  18.404  32.844  17.815  36.524  17.602   41.33  16.638
  42.321  16.633  46.207  15.881  46.837  15.852  51.134  15.659  56.527  16.448
   56.72   16.55  59.565  17.806  67.943  18.073  76.183  18.483  79.783  18.848
  82.403  19.091  88.088  19.223  89.766  19.476
#Mann= 3 , 0 , 0
  26.012     .04       0  36.524    .045       0  59.565     .04       0
Bank Sta=36.524,59.565
XS Rating Curve= 0 ,0
Exp/Cntr=0.3,0.1

Type RM Length L Ch R = 1 ,1051.997,119.597,121.94,125.44
Node Photo=\HecRas Photos\W12.JPG
BEGIN DESCRIPTION:
2008 Survey Section
END DESCRIPTION:
Node Name=W12
XS GIS Cut Line= 2
300278.1797119045379817.14976326300273.9853621615379862.86817545
#Sta/Elev= 13
  41.591   23.68  49.111   18.69  53.161   18.16  58.451   16.07   61.74   16.07
  64.511   15.87   67.45   15.87  69.241   15.73   70.34   16.31  71.881   17.03
  81.081   18.05  84.021   19.03  87.501   19.15
#Mann= 3 , 0 , 0
  41.591     .04       0  53.161    .045       0  71.881     .04       0
Bank Sta=53.161,71.881
XS Rating Curve= 0 ,0
Exp/Cntr=0.3,0.1

Type RM Length L Ch R = 1 ,930.0570,121.399,127.112,129.974
BEGIN DESCRIPTION:
Interpolated Section
END DESCRIPTION:
Node Name=W11a
XS GIS Cut Line= 2
300189.3136271425379758.25458379300156.4270450765379798.80645942
#Sta/Elev= 18
  39.315  21.413  46.614  16.596  47.782  16.152  50.545   15.79  54.876  14.621
  55.679  14.453   60.62   14.41    63.1   14.36   66.08   14.41  68.443  14.617
  69.449  14.906  69.821  15.086  72.699  16.075  75.663  16.068  82.605  16.545
  86.691   17.16  87.216  17.181  91.526  17.564
#Mann= 3 , 0 , 0
  39.315     .04       0  50.545    .045       0  72.699     .04       0
Bank Sta=50.545,72.699
XS Rating Curve= 0 ,0
Exp/Cntr=0.3,0.1

Type RM Length L Ch R = 1 ,802.9447,71.609,75.267,71.522
Node Photo=\HecRas Photos\W11.JPG
BEGIN DESCRIPTION:
2008 Survey Section
END DESCRIPTION:
Node Name=W11
XS GIS Cut Line= 2
 300109.024391465379677.44797171300053.624571032 5379697.0932981
#Sta/Elev= 14
  52.439   19.05  60.639   13.67  67.509   12.77   70.92    12.8  74.999   12.75
   77.01   12.66  78.429   12.53   79.67   12.67  81.389   12.61  82.689   12.83
  86.889   14.84  90.719   14.58 105.649   15.24 111.219   15.91
#Mann= 3 , 0 , 0
  52.439     .04       0  60.639    .045       0  82.689     .04       0
Levee=0,,,-1,86.82,14.83,,Levee 23
Bank Sta=60.639,82.689
XS Rating Curve= 0 ,0
Exp/Cntr=0.3,0.1

Type RM Length L Ch R = 1 ,727.6773,79.11,78.888,80.462
BEGIN DESCRIPTION:
Interpolated Section
END DESCRIPTION:
Node Name=W10a
XS GIS Cut Line= 2
300099.889136565 5379608.0488858300038.2185467355379634.14028919
#Sta/Elev= 20
  50.773   18.02   57.42  15.077  58.467   14.96  62.989   13.48  69.061  11.985
  70.106  11.687   71.81   11.63   73.84    11.6   75.81   11.64  77.044  11.675
  77.804  11.749  81.308  12.491  83.682  13.531  86.819  14.279  89.043  13.666
  91.899  12.995  97.556  13.624  109.94  13.945 114.019  14.165 117.736  14.562
#Mann= 3 , 0 , 0
  50.773     .04       0  62.989    .045       0  83.682     .04       0
Levee=0,,,-1,86.88,14.29,,Levee 23
Bank Sta=62.989,83.682
XS Rating Curve= 0 ,0
Exp/Cntr=0.3,0.1

Type RM Length L Ch R = 1 ,648.7893,69.05,68.73,68.507
Node Photo=\HecRas Photos\W10.JPG
BEGIN DESCRIPTION:
2008 Survey Section
END DESCRIPTION:
Node Name=W10
XS GIS Cut Line= 2
300092.3868587025379526.86943979300002.014689702   5379565.73747
#Sta/Elev= 18
  44.297   16.94  50.107   16.49   56.85      12  58.897   10.66   59.71   10.53
  60.207   10.33   61.09    10.5  62.927   10.43   64.42    10.6  66.967   10.56
   68.04   10.78  72.507   10.88   74.47   11.73  79.667   13.85  86.267   11.24
  93.617   12.34 115.007   12.67 119.837   13.15
#Mann= 3 , 0 , 0
  44.297     .04       0   56.85    .045       0   74.47     .04       0
Levee=0,,,-1,79.82,13.84,,Levee 23
Bank Sta=56.85,74.47
XS Rating Curve= 0 ,0
Exp/Cntr=0.3,0.1

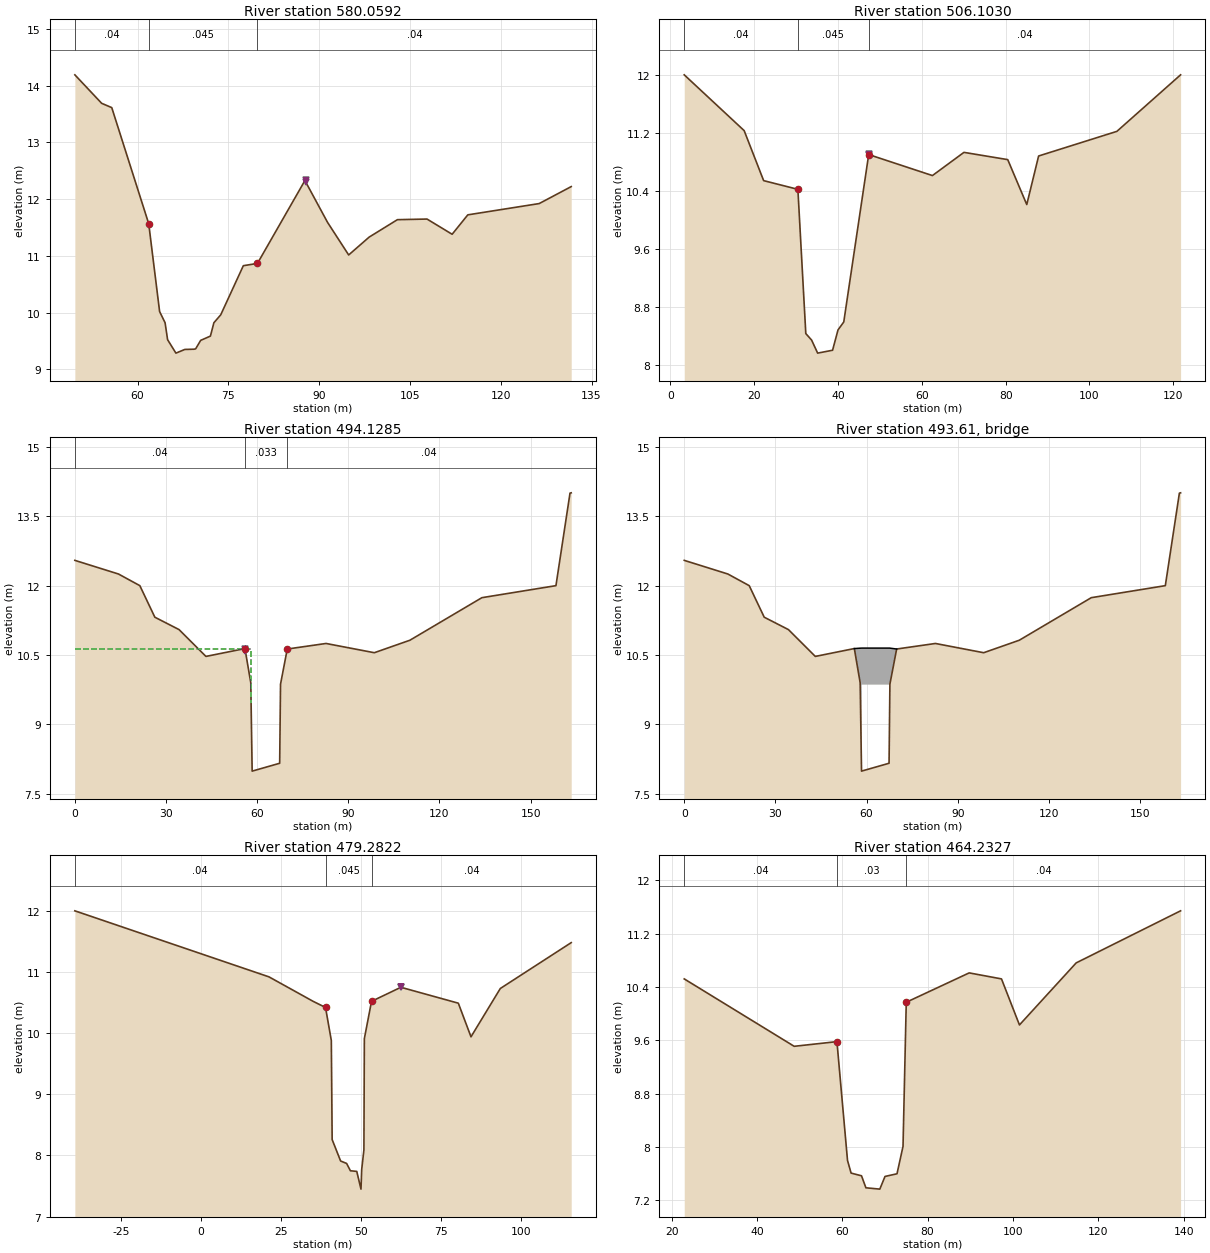
Type RM Length L Ch R = 1 ,580.0592,74.519,73.956,72.988
BEGIN DESCRIPTION:
Interpolated Section
END DESCRIPTION:
Node Name=W9a
XS GIS Cut Line= 2
300073.6423346195379462.06826613299999.8798686985379497.88561736
#Sta/Elev= 27
  49.643   14.19  54.069  13.688  55.739  13.612  61.845  11.566  63.644  10.018
   64.55    9.82  64.963   9.522  66.338   9.285   67.81    9.35  69.317   9.354
  69.594    9.36   70.43    9.51  72.035   9.585   72.61    9.82  73.741    9.96
  77.476  10.826  79.808  10.866   87.65  12.327  91.386   11.59  94.878  11.015
  98.263   11.33 102.927  11.637 107.819  11.648 111.971   11.38 114.559  11.722
 126.353  11.921 131.642   12.22
#Mann= 3 , 0 , 0
  49.643     .04       0  61.845    .045       0  79.808     .04       0
Levee=0,,,-1,87.75,12.34,,Levee 23
Bank Sta=61.845,79.808
XS Rating Curve= 0 ,0
Exp/Cntr=0.3,0.1

Type RM Length L Ch R = 1 ,506.1030,11.553,11.974,12.929
Node Photo=\HecRas Photos\W09.JPG
BEGIN DESCRIPTION:
2008 Survey Section
END DESCRIPTION:
Node Name=W9
XS GIS Cut Line= 4
300068.2414353455379380.97935433300056.1398469045379388.59785433
299980.8645969775379435.98704577299968.0013722145379444.08503045
#Sta/Elev= 18
   3.305      12  17.605   11.23  22.255   10.54  30.425   10.42  32.315    8.43
    33.7    8.34  35.145    8.16  38.705     8.2      40    8.48  41.375    8.59
  47.325    10.9  62.535   10.61  70.055   10.93  80.505   10.83  85.045   10.21
  87.875   10.88 106.555   11.22 121.755      12
#Mann= 3 , 0 , 0
   3.305     .04       0  30.425    .045       0  47.325     .04       0
Levee=0,,,-1,47.37,10.91,,Levee 23
Bank Sta=30.425,47.325
XS Rating Curve= 0 ,0
Exp/Cntr=0.3,0.1

Type RM Length L Ch R = 1 ,494.1285,15.27,14.846,14.427
Node Photo=\HecRas Photos\W08.JPG
BEGIN DESCRIPTION:
2008 Survey Section
END DESCRIPTION:
Node Name=W8
XS GIS Cut Line= 4
300090.8916212315379368.46471498300058.5959418035379379.98234975
299964.7175778395379413.46226807299937.0287000835379423.33697537
#Sta/Elev= 19
       0  12.547  14.348  12.252  21.386      12  26.323  11.318  34.288   11.05
  43.138   10.47  55.978   10.64  57.898     9.9  58.348    7.99  67.408    8.16
  67.688    9.87  69.908   10.63  82.668   10.75  98.548   10.55 110.268   10.82
 133.958   11.74  158.33      12 162.957      14 163.355  14.007
#Mann= 3 , 0 , 0
       0     .04       0  55.978    .033       0  69.908     .04       0
Levee=-1,56.09,10.64,0,,,Levee 24,
#XS Ineff= 2 , 0
       0      58   10.64               0
Permanent Ineff=
       F       F
Bank Sta=55.978,69.908
XS Rating Curve= 0 ,0
Exp/Cntr=0.5,0.3

Type RM Length L Ch R = 3 ,493.61  ,,,
Node Photo=\HecRas Photos\Miss Bridge.JPG
BEGIN DESCRIPTION:
Miss Drive Bridge
END DESCRIPTION:
Bridge Culvert--1,0,-1,-1, 0
Deck Dist Width WeirC Skew NumUp NumDn MinLoCord MaxHiCord MaxSubmerge Is_Ogee
0.52,12.87,1.6,0, 6, 6, , , 0.98, 0, 1,1,,
   55.98    58.4    58.4    67.6    67.6   69.91
   10.64   10.65   10.65   10.65   10.65   10.63
       0       0    9.86    9.86       0       0
   31.34    41.1    41.1    50.3    50.3   57.72
   10.63   10.65   10.65   10.65   10.65   10.63
       0       0    9.86    9.86       0       0
BR Coef=-1 , 0 , 0 ,, 0 ,,,0.8,-1,,0,
WSPro=,,,, 1 ,,,, 0 ,,,, 0 ,,,,-1 ,-1 ,-1 , 0 , 0 , 0 , 0 , 0
BC Design=,, 0 ,, 0 ,,,,,,
BC Use User HTab Curves=0
BC User HTab FreeFlow(D)= 0

Type RM Length L Ch R = 1 ,479.2822,18.024,15.05,14.12
Node Photo=\HecRas Photos\W07.JPG
BEGIN DESCRIPTION:
2008 Survey Section
END DESCRIPTION:
Node Name=W7
XS GIS Cut Line= 3
300104.6511135465379338.87418198 300049.926581165379364.90465646
299964.7605915165379405.41502764
#Sta/Elev= 20
 -39.359      12  21.241   10.92  35.011   10.52  38.871   10.42  40.681    9.88
  40.941    8.26  43.581    7.91   45.45    7.87  46.641    7.75   48.62    7.74
  49.941    7.45   50.16    7.77  50.851    8.09  50.991    9.91  53.231   10.52
  62.391   10.75  80.321   10.49  84.271    9.94  93.421   10.73 115.551   11.48
#Mann= 3 , 0 , 0
 -39.359     .04       0  38.871    .045       0  53.231     .04       0
Levee=0,,,-1,62.47,10.76,,Levee 25
Bank Sta=38.871,53.231
XS Rating Curve= 0 ,0
Exp/Cntr=0.5,0.3

Type RM Length L Ch R = 1 ,464.2327,69.028,69.847,71.832
Node Photo=\HecRas Photos\W06.JPG
BEGIN DESCRIPTION:
2008 Survey Section
END DESCRIPTION:
Node Name=W6
XS GIS Cut Line= 2
300055.7657332375379338.69292146299958.817893427 5379403.0048548
#Sta/Elev= 17
   22.96   10.52   48.73    9.51   58.75    9.58   61.23     7.8   62.07    7.61
   64.51    7.57   65.54    7.39    68.8    7.37   70.02    7.56   72.83     7.6
   74.24    8.01      75   10.17   89.75   10.61   97.32   10.52  101.53    9.83
  114.83   10.76   139.3   11.54
#Mann= 3 , 0 , 0
   22.96     .04       0   58.75     .03       0      75     .04       0
Bank Sta=58.75,75
XS Rating Curve= 0 ,0
Exp/Cntr=0.3,0.1

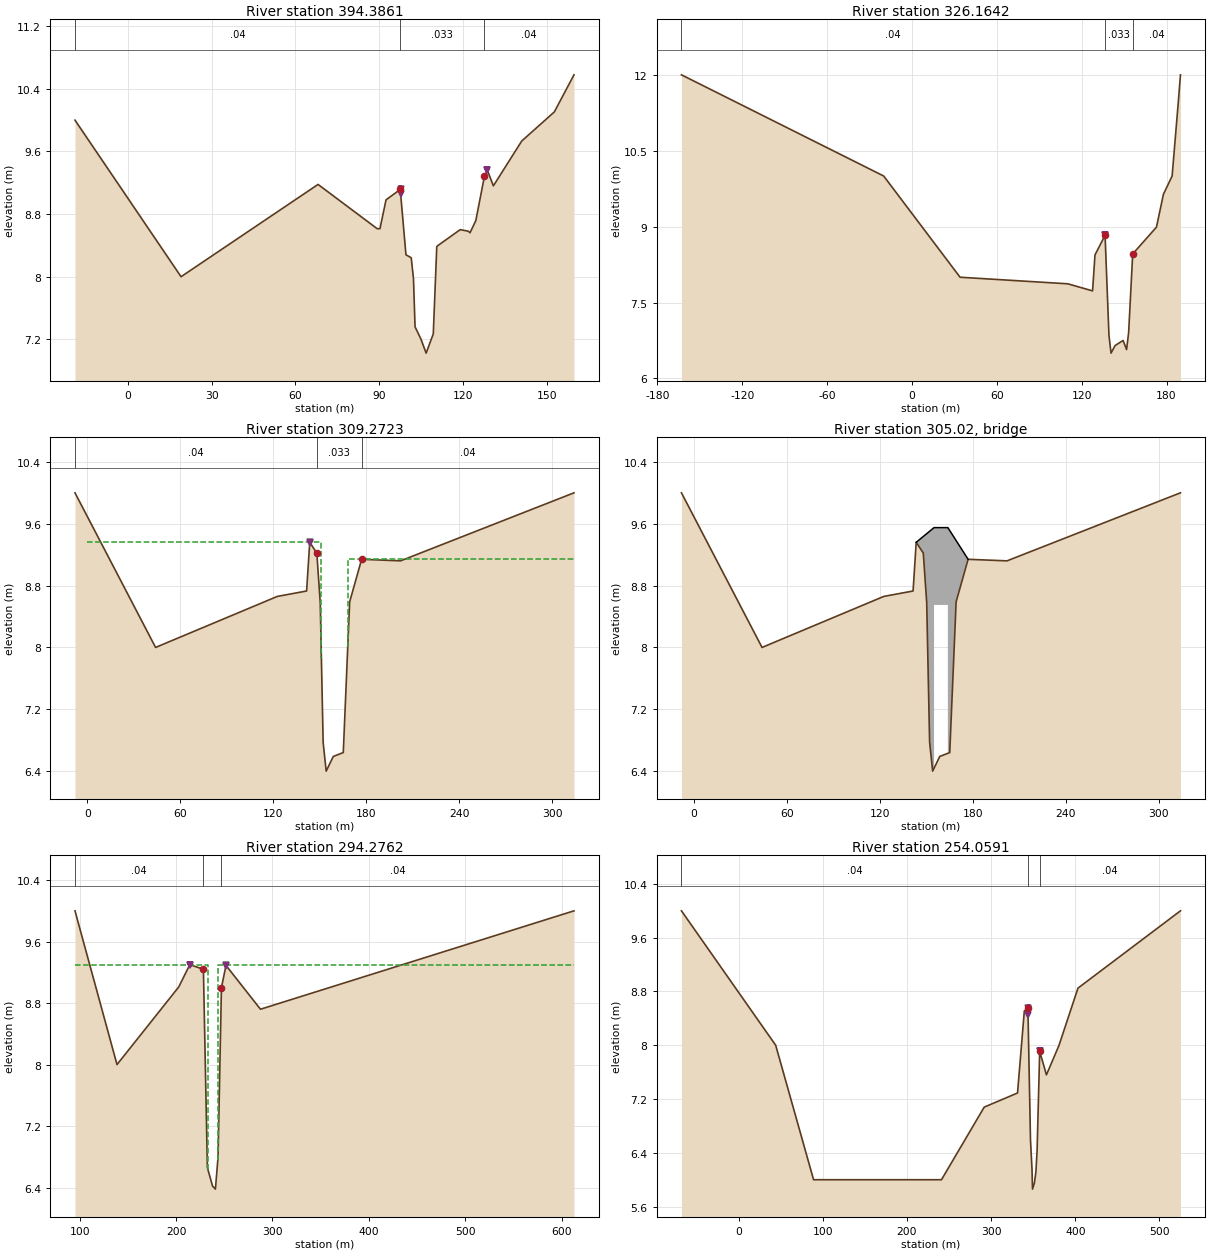
Type RM Length L Ch R = 1 ,394.3861,63.972,68.222,69.71
BEGIN DESCRIPTION:
Interpolated Section
END DESCRIPTION:
Node Name=W5a
XS GIS Cut Line= 3
300115.5698633285379255.65033573300033.2517324575379284.08258489
299946.5794008885379314.01875205
#Sta/Elev= 26
     -19      10      19       8   68.09   9.179  89.294   8.613  90.275   8.614
   92.44   8.982  97.539   9.115   99.58    8.28 101.469   8.242 102.279   7.974
  102.84    7.36 104.951   7.203 106.812   7.024  109.37    7.27  110.62   8.384
 110.902   8.395 118.994   8.601 121.899   8.582 122.526   8.561 124.614   8.717
 127.687   9.281  128.75    9.36 130.906   9.161 141.076   9.734 152.738  10.105
 159.787  10.579
#Mann= 3 , 0 , 0
     -19     .04       0  97.539    .033       0 127.687     .04       0
Levee=-1,97.68,9.12,-1,128.75,9.36,Levee 26,Levee 27
Bank Sta=97.539,127.687
XS Rating Curve= 0 ,0
Exp/Cntr=0.3,0.1

Type RM Length L Ch R = 1 ,326.1642,14.443,16.892,18.313
Node Photo=\HecRas Photos\W05.JPG
BEGIN DESCRIPTION:
2008 Survey Section
END DESCRIPTION:
Node Name=W5
XS GIS Cut Line= 5
300276.8093800145379170.68468354300136.6980384355379199.28209533
300009.1614444545379225.31293948299892.9600124975379249.03022148
299881.1651905175379251.43760248
#Sta/Elev= 19
    -163      12     -20      10      34       8 110.166    7.87 127.686    7.73
 129.396    8.44 136.526    8.83 139.276    6.85 140.746     6.5 143.606    6.65
 149.266    6.75 151.736    6.57 153.196    6.91 156.066    8.46 172.866    8.99
 177.796    9.64  183.93      10 188.262  11.446 189.834      12
#Mann= 3 , 0 , 0
    -163     .04       0 136.526    .033       0 156.066     .04       0
Levee=-1,136.5,8.84,0,,,Levee 26,
Bank Sta=136.526,156.066
XS Rating Curve= 0 ,0
Exp/Cntr=0.3,0.1

Type RM Length L Ch R = 1 ,309.2723,15.642,14.996,14.953
Node Photo=\HecRas Photos\W04.JPG
BEGIN DESCRIPTION:
2008 Survey Section
END DESCRIPTION:
Node Name=W4
XS GIS Cut Line= 4
300136.303502507 5379189.7286179300007.384630526  5379210.427634
 299915.888196465379225.11816094299805.3834867285379242.86062743
#Sta/Elev= 15
      -8      10      44       8  122.57    8.66  141.46    8.73  143.48    9.36
  148.05    9.22  150.25    8.58  152.14    6.77  154.09     6.4  158.69    6.59
  165.12    6.64  169.24    8.59  176.97    9.14  202.08    9.12     314      10
#Mann= 3 , 0 , 0
      -8     .04       0  148.05    .033       0  176.97     .04       0
Levee=-1,143.55,9.35,0,,,Levee 26,
#XS Ineff= 2 , 0
       0     151    9.36     168       0    9.14
Permanent Ineff=
       F       F
Bank Sta=148.05,176.97
XS Rating Curve= 0 ,0
Exp/Cntr=0.5,0.3

Type RM Length L Ch R = 3 ,305.02  ,,,
Node Photo=\HecRas Photos\Carolina Bridge.JPG
BEGIN DESCRIPTION:
Carolina Ave Bridge
END DESCRIPTION:
Bridge Culvert--1,0,-1,-1, 0
Deck Dist Width WeirC Skew NumUp NumDn MinLoCord MaxHiCord MaxSubmerge Is_Ogee
4.25,8.94,1.6,0, 6, 6, , , 0.98, 0, 1,1,,
  143.48     155     155   163.9   163.9  176.97
    9.36    9.55    9.55    9.55    9.55    9.14
       0       0    8.55    8.55       0       0
  214.21     234     234   242.9   242.9  251.75
     9.3    9.55    9.55    9.55    9.55    9.29
       0       0    8.55    8.55       0       0
BR Coef=-1 , 0 , 0 ,, 0 ,,,0.8,-1,,0,
WSPro=,,,, 1 ,,,, 0 ,,,, 0 ,,,,-1 ,-1 ,-1 , 0 , 0 , 0 , 0 , 0
BC Design=,, 0 ,, 0 ,,,,,,
BC Use User HTab Curves=0
BC User HTab FreeFlow(D)= 0

Type RM Length L Ch R = 1 ,294.2762,85.792,40.217,25.479
Node Photo=\HecRas Photos\W03.JPG
BEGIN DESCRIPTION:
2008 Survey Section
END DESCRIPTION:
Node Name=W3
XS GIS Cut Line= 4
300134.5442039585379172.85225154300028.4277358875379191.25291856
299923.975984997 5379209.3649225299603.360395015 5379264.9598817
#Sta/Elev= 13
  95.028      10 138.628       8 202.728    9.01 214.208     9.3 228.308    9.24
 232.428    6.66 237.808    6.42 240.768    6.38 243.528     6.8 247.008       9
 251.748    9.29 287.538    8.72 612.938      10
#Mann= 3 , 0 , 0
  95.028     .04       0 228.308    .033       0 247.008     .04       0
Levee=-1,214.22,9.3,-1,251.63,9.29,Levee 26,Levee 28
#XS Ineff= 2 , 0
       0     233     9.3   243.3       0    9.29
Permanent Ineff=
       F       F
Bank Sta=228.308,247.008
XS Rating Curve= 0 ,0
Exp/Cntr=0.5,0.3

Type RM Length L Ch R = 1 ,254.0591,74.46,106.674,110.065
Node Photo=\HecRas Photos\W0.JPG
BEGIN DESCRIPTION:
2008 Survey Section
END DESCRIPTION:
Node Name=W2
XS GIS Cut Line= 6
300215.3837418395378846.99193121299986.9183204945379124.95448985
299918.8401838145379207.78178576299916.7070083875379210.37711461
299916.1888667195379211.00751191 299838.846335575379305.10633824
#Sta/Elev= 19
     -68      10      44       8      89       6     241       6 291.805    7.08
 331.375    7.29 339.445    8.51 343.725    8.55 346.775    6.59 348.565    6.16
 349.185    5.86 351.425    5.95 353.245    6.12 354.635    6.44 357.715    7.91
 365.735    7.56 380.705       8 403.195    8.85     525      10
#Mann= 3 , 0 , 0
     -68     .04       0 343.725    .033       0 357.715     .04       0
Levee=-1,343.89,8.55,-1,357.71,7.92,Levee 26,Levee 28
Bank Sta=343.725,357.715
XS Rating Curve= 0 ,0
Exp/Cntr=0.3,0.1

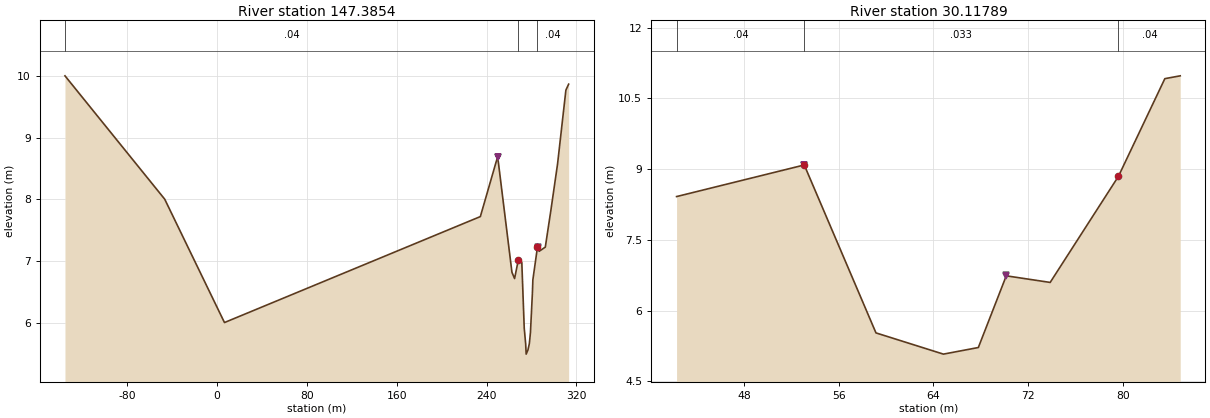
Type RM Length L Ch R = 1 ,147.3854,137.703,117.268,115.163
BEGIN DESCRIPTION:
Interpolated Section
END DESCRIPTION:
Node Name=W1a
XS GIS Cut Line= 3
300230.444808427 5378885.1405377299915.6107996985379079.12916934
299831.1880560285379131.14722352
#Sta/Elev= 25
-135.325      10 -46.525       8   6.675       6 234.475   7.718  249.89    8.69
 262.604   6.815 264.954   6.713  268.34    7.02  268.37    7.02 271.383   6.978
 273.551   5.906 274.823   5.655 275.264   5.488 276.833   5.554 278.107   5.659
  279.08   5.838 280.839   6.487 281.236   6.693 285.299    7.22 286.852   7.155
  292.31   7.223 297.333   7.827 303.214   8.571 310.622   9.767 313.079   9.865
#Mann= 3 , 0 , 0
-135.325     .04       0  268.34    .033       0 285.299     .04       0
Levee=-1,249.89,8.69,-1,285.46,7.23,Levee 26,Levee 28
Bank Sta=268.34,285.299
XS Rating Curve= 0 ,0
Exp/Cntr=0.3,0.1

Type RM Length L Ch R = 1 ,30.11789,11.075,30.118,12.748
Node Photo=\HecRas Photos\W01.JPG
BEGIN DESCRIPTION:
2008 Survey Section
END DESCRIPTION:
Node Name=W1
XS GIS Cut Line= 3
299804.6222780285379008.73655182299776.3362714195379031.30821366
299771.3556696555379035.28263325
#Sta/Elev= 10
  42.295    8.42  53.085    9.09  59.145    5.53  64.845    5.08  67.795    5.22
  70.155    6.74  73.865     6.6  79.635    8.85  83.555   10.92  84.855   10.98
#Mann= 3 , 0 , 0
  42.295     .04       0  53.085    .033       0  79.635     .04       0
Levee=-1,53.085,9.09,-1,70.16,6.76,,Levee 28
Bank Sta=53.085,79.635
XS Rating Curve= 0 ,0
Exp/Cntr=0.3,0.1

River Reach=Warm Creek      ,US of Noels Pond
Reach XY= 30
304728.0455160185381575.99489331304394.4146444975381314.53918168
304282.0890645445381038.74403431304172.1533905495380955.57530702
304243.8505692435380844.68367064304199.3983184535380807.87911891
 304209.435923475380763.90484932304274.4413654855380705.59114398
304241.9386444785380495.27941981 304209.435923475380441.74552638
304156.8579924285380451.30515021304136.3048012025380397.77125679
304101.412174239 5380424.5382035304103.802080194 5380342.3254386
 304061.739735365380256.76680535303914.0435472545380149.22103732
303933.6407760975380091.86329436 303882.97476982 5379963.7643351
 303805.541816835379958.98452318303756.7877353195380016.82024733
303655.4557227665379935.56344481303639.6823434545379869.60204041
303591.8842243245379845.22499966 303519.709064445379879.16166424
303516.8411772925379815.11218461303447.5339045565379796.47091815
303255.3854656575379828.97363915303198.0277227035379755.84251689
303216.6689891635379685.10130057303157.6236630715379656.71209144
Reach Downstream Storage Area=Noel's Pond

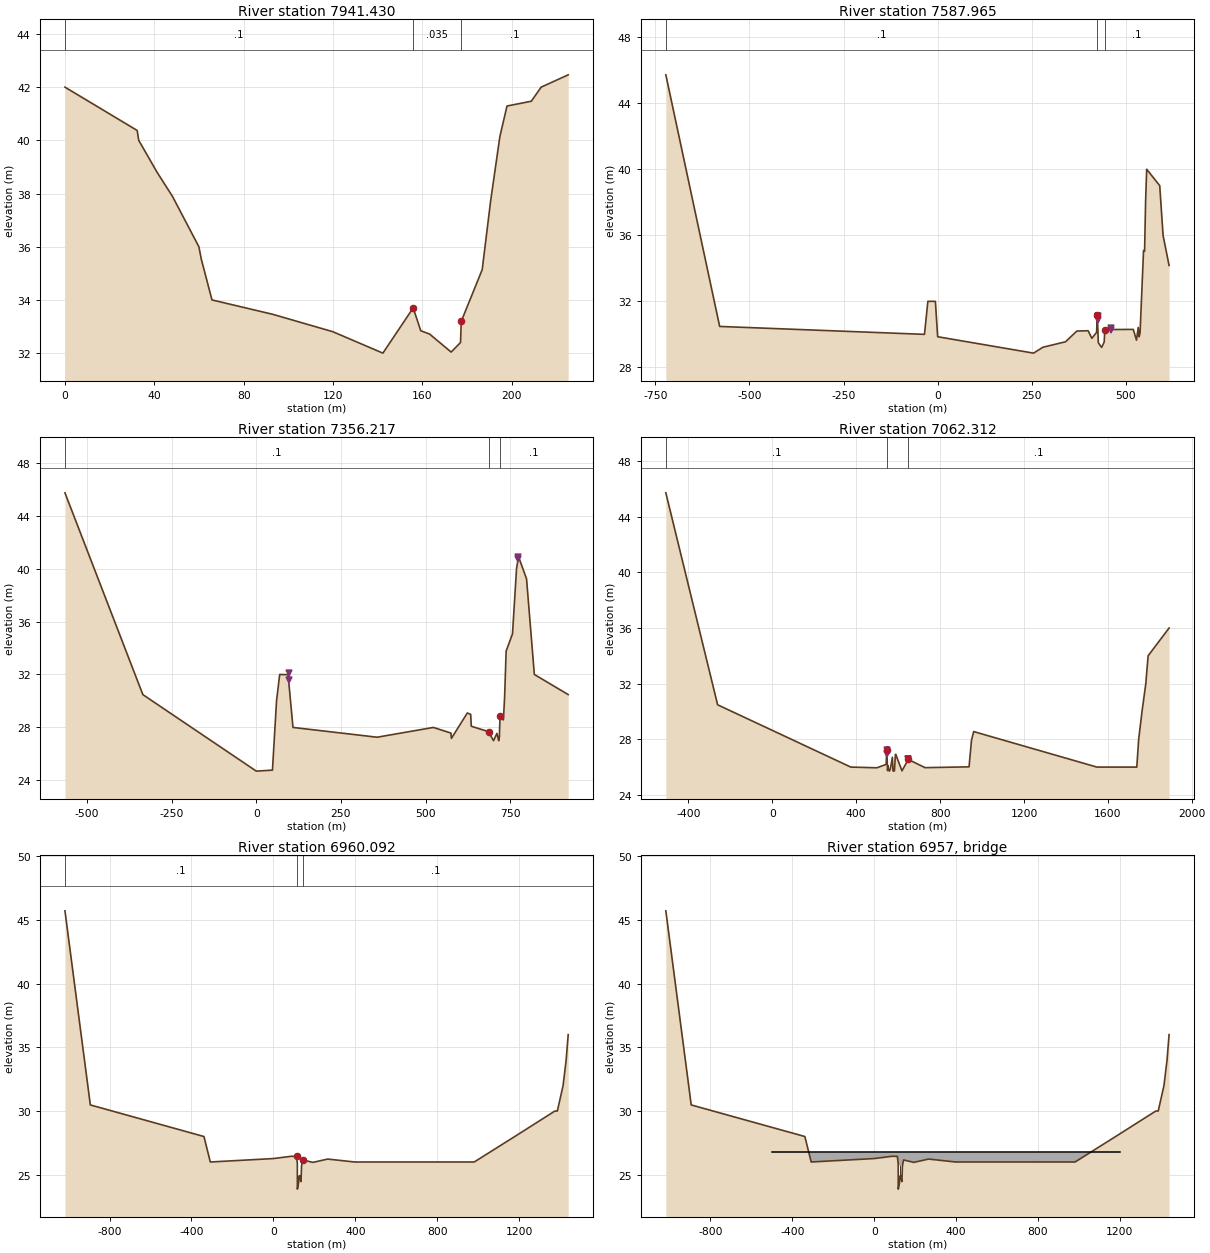
Type RM Length L Ch R = 1 ,7941.430,386.999,353.465,357.514
BEGIN DESCRIPTION:
1996 Survey Section (637.00)
END DESCRIPTION:
Node Name=W36
XS GIS Cut Line= 5
304627.1320575995381301.54642526304566.7204908375381331.13175373
304546.9628678035381340.80764526 304445.478595455381390.50749073
304424.8333826395381400.61806119
#Sta/Elev= 24
       0      42  32.322  40.372  33.028      40  41.235    38.8  48.176  37.886
  59.951      36  61.012   35.54   65.81      34  93.021  33.459 119.874  32.806
 142.308      32 155.867    33.7 159.267   32.84 163.167   32.72 172.867   32.04
 177.067    32.4 177.367   33.19 186.767   35.14 190.567   37.74 194.667   40.14
 197.867   41.29 208.738  41.471 213.159      42 225.255  42.463
#Mann= 3 , 0 , 0
       0      .1       0 155.867    .035       0 177.367      .1       0
Bank Sta=155.867,177.367
XS Rating Curve= 0 ,0
Exp/Cntr=0.3,0.1

Type RM Length L Ch R = 1 ,7587.965,139.047,231.748,232.266
Node Photo=\HecRas Photos\W35.JPG
BEGIN DESCRIPTION:
1996 Survey Section (636.00)
END DESCRIPTION:
Node Name=W35
XS GIS Cut Line= 6
305358.2821172365380582.91070243 304705.023525735380890.37974579
304533.4119525235380971.15211821304474.6228942855380998.82234824
304207.6876949385381124.46066585304148.8500944915381152.15374324
#Sta/Elev= 30
    -722   45.72    -579   30.48     -35      30     -26      32      -6      32
       0  29.856  254.6728.86302  279.67   29.22  339.67   29.55  369.67    30.2
  399.67   30.22  409.57   29.76  422.17   30.12  424.17   31.15  426.77   29.49
  435.57   29.21  442.27   29.53  444.07   30.29  519.67    30.3  528.07   29.65
  532.77   30.42  535.07   29.85  537.67   30.09  546.87   35.08  549.67   35.03
 552.282      38 555.226      40 589.872  39.008 598.738      36 614.699  34.171
#Mann= 3 , 0 , 0
    -722      .1       0  424.17    .035       0  444.07      .1       0
Levee=-1,424.64,31.14,-1,459.42,30.39,Levee 29,Levee 30
Bank Sta=424.17,444.07
XS Rating Curve= 0 ,0
Exp/Cntr=0.3,0.1

Type RM Length L Ch R = 1 ,7356.217,152.634,293.905,226.352
BEGIN DESCRIPTION:
1996 Survey Section (635.00)
END DESCRIPTION:
Node Name=W34
XS GIS Cut Line= 6
305398.0686642065380842.93253036304833.9876987025380875.14532837
304212.0330069615380910.66310345304158.571973963 5380913.7160862
304063.5318289745380919.14351449303880.6168932825380929.58918139
#Sta/Elev= 30
    -565   45.72    -335   30.48       0    24.7  47.689  24.776  59.693      30
  69.034      32  93.784  31.986 108.302      28 356.614  27.261 522.707      28
  574.66  27.575 576.039  27.172 622.968   29.09 632.968   28.99 634.768   28.09
 685.668   27.68 700.368      27 710.468   27.55 715.668      27 717.668   27.29
 719.568   28.84 729.568   28.57 733.168   30.32 737.668   33.77 756.423  35.066
 768.363      40 774.245  40.898 797.903  39.222 820.931      32 920.881  30.482
#Mann= 3 , 0 , 0
    -565      .1       0 685.668    .035       0 719.568      .1       0
Levee=-1,95.24,32.1,-1,773.18,40.87,Levee 29,Levee 30
Bank Sta=685.668,719.568
XS Rating Curve= 0 ,0
Exp/Cntr=0.3,0.1

Type RM Length L Ch R = 1 ,7062.312,98.8,118.591,118.374
BEGIN DESCRIPTION:
1996 Survey Section (634.00)
END DESCRIPTION:
Node Name=W33
XS GIS Cut Line= 6
305333.0438583175380909.52089663304696.3669127075380791.82047857
304662.8587991295380785.62594144303897.0440186815380644.05222747
303855.7319983815380636.41500722 302939.523546065380467.03849911
#Sta/Elev= 30
    -508   45.72    -261   30.48 374.176      26 498.255   25.95 540.255   26.18
 542.855   26.23 545.455   27.22 549.455   25.75 551.955    26.1 553.655   25.87
 558.255   25.71 562.755   25.87 572.555   26.71 575.455   25.72 582.155   25.72
 586.855    26.9 588.255   26.92 618.255   25.73 648.255   26.55 728.255   25.96
 938.044  26.018 949.793  27.934 960.267  28.553    1548      26    1738      26
    1747      28    1763      30    1781      32    1792      34    1892      36
#Mann= 3 , 0 , 0
    -508      .1       0 545.455    .035       0 648.255      .1       0
Levee=-1,546.2,27.22,-1,648.255,26.55,Levee 29,Levee 30
Bank Sta=545.455,648.255
XS Rating Curve= 0 ,0
Exp/Cntr=0.3,0.1

Type RM Length L Ch R = 1 ,6960.092,20,17,20
BEGIN DESCRIPTION:
Interpolated Section
END DESCRIPTION:
Node Name=W32a
XS GIS Cut Line= 6
305373.6559004795380882.48947054304712.074591214 5380729.6785703
304119.1947861295380592.73622402303220.1484616945380385.07606707
302975.5874770035380328.58779601302965.8440114775380326.33726728
#Sta/Elev= 27
   -1018   45.72    -894   30.48    -339      28    -308      26       0   26.27
   88.67   26.45  113.04   26.44  117.06   25.87  117.14   23.87  123.31   24.37
  125.17   24.85  128.11   24.93  135.03   24.46  137.54   25.69   143.1   26.16
  193.36   25.97  265.38   26.23     397      26     898      26     953      26
     981      26    1179      28    1375      30    1387      30    1415      32
    1430      34    1440      36
#Mann= 3 , 0 , 0
   -1018      .1       0  113.04    .035       0   143.1      .1       0
Bank Sta=113.04,143.1
XS Rating Curve= 0 ,0
Exp/Cntr=0.5,0.3

Type RM Length L Ch R = 3 ,6957    ,,,
Node Photo=\HecRas Photos\Rt 460 Bridge.JPG
BEGIN DESCRIPTION:
Route 460 Bridge
END DESCRIPTION:
Bridge Culvert--1,0,-1,-1, 0
Deck Dist Width WeirC Skew NumUp NumDn MinLoCord MaxHiCord MaxSubmerge Is_Ogee
3,8,1.6,0, 6, 6, , , 0.98, 0, 1,1,,
    -500  117.93  117.93  135.33  135.33    1200
   26.75   26.75   26.75   26.75   26.75   26.75
       0       0   25.74   25.74       0       0
       0     557     557   574.4   574.4    1500
   26.75   26.75   26.75   26.75   26.75   26.75
       0       0   25.74   25.74       0       0
Pier Skew, UpSta & Num, DnSta & Num=  ,126.63, 2 ,565.7, 2 , 0 , 0 , 0 ,,
       1       1
       0   25.74
       1       1
       0   25.74
BR Coef=-1 , 0 , 0 ,, 0 ,,,0.8,-1,,0,
WSPro=,,,, 1 ,,,, 0 ,,,, 0 ,,,,-1 ,-1 ,-1 , 0 , 0 , 0 , 0 , 0
BC Design=,, 0 ,, 0 ,,,,,,
BC Use User HTab Curves=0
BC User HTab FreeFlow(D)= 0

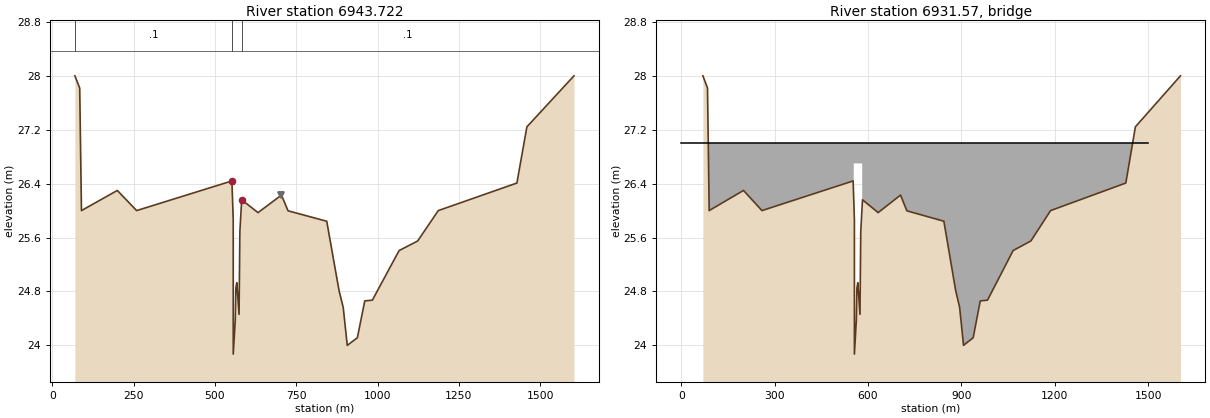
Type RM Length L Ch R = 1 ,6943.722,123.195,76.783,97.272
Node Photo=\HecRas Photos\W32.JPG
BEGIN DESCRIPTION:
2008 Survey Section
END DESCRIPTION:
Node Name=W32
XS GIS Cut Line= 5
304755.0624568345380723.86703864304394.7057797725380640.62571343
304113.6268121875380575.69730433303378.2603340355380405.82982565
303237.1540776855380373.23469832
#Sta/Elev= 30
  69.221      28  84.092  27.819  89.477      26 199.772  26.299 259.117      26
 552.107   26.44 556.127   25.87 556.207   23.87 562.377   24.37 564.237   24.85
 567.177   24.93 574.097   24.46 576.607   25.69 582.167   26.16 632.427   25.97
 704.447   26.23 724.712  25.997 843.703  25.842   881.5  24.815 894.381  24.563
 906.814      24 937.905  24.113 960.636   24.66 983.982  24.6711066.262  25.407
1123.327  25.5491186.665      261428.444  26.4091459.178  27.243    1604      28
#Mann= 3 , 0 , 0
  69.221      .1       0 552.107    .035       0 582.167      .1       0
Levee=0,,,-1,704.35,26.23,,Levee 31
Bank Sta=552.107,582.167
XS Rating Curve= 0 ,0
Exp/Cntr=0.5,0.3

Type RM Length L Ch R = 3 ,6931.57 ,,,
Node Photo=\HecRas Photos\Rt 460 Rail.JPG
BEGIN DESCRIPTION:
Route 460 Railway Trestle
END DESCRIPTION:
Bridge Culvert--1,0,-1,-1, 0
Deck Dist Width WeirC Skew NumUp NumDn MinLoCord MaxHiCord MaxSubmerge Is_Ogee
12.15,3.65,1.6,0, 6, 6, , , 0.98, 0, 1,1,,
       0     554     554  581.15  581.15    1500
      27      27      27      27      27      27
       0       0    26.7    26.7       0       0
  423.11     560     560  587.15  587.15    1300
      27      27      27      27      27      27
       0       0    26.7    26.7       0       0
BR Coef=-1 , 0 , 0 ,, 0 ,,,0.8,-1,,0,
WSPro=,,,, 1 ,,,, 0 ,,,, 0 ,,,,-1 ,-1 ,-1 , 0 , 0 , 0 , 0 , 0
BC Design=,, 0 ,, 0 ,,,,,,
BC Use User HTab Curves=0
BC User HTab FreeFlow(D)= 0