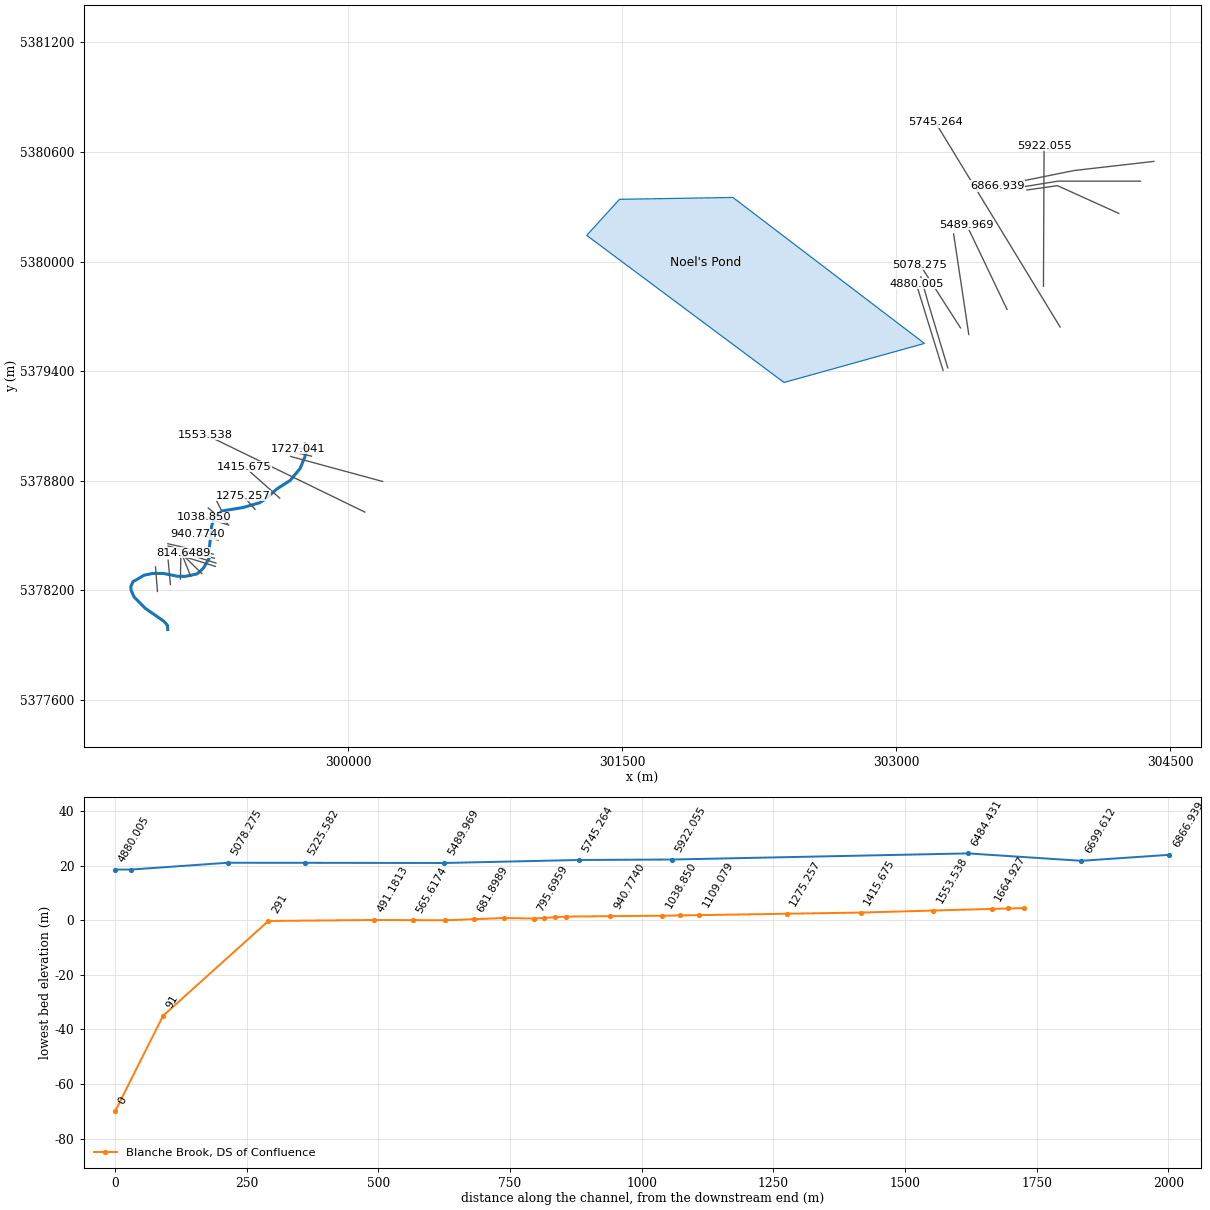
HEC-RAS study Blanche_Brook.prj: Stephenville Model

--- Blanche_Brook.g01 (geometry) --- (continued)

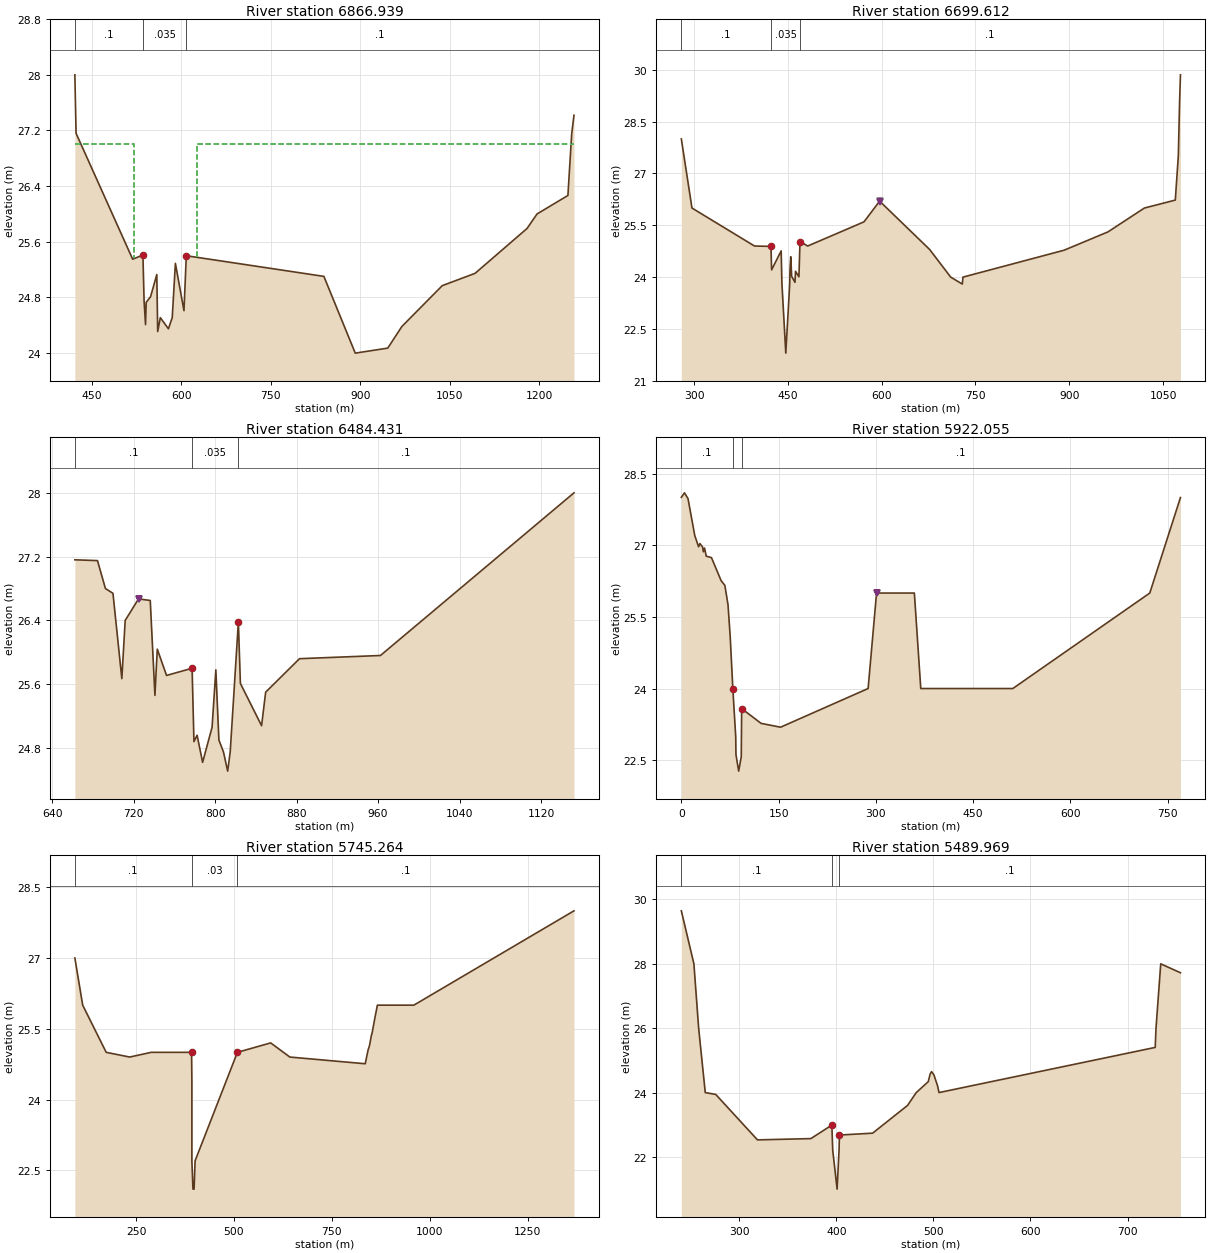
Type RM Length L Ch R = 1 ,6866.939,169.62,167.327,98.277
BEGIN DESCRIPTION:
1996 Survey Section (632.00)
END DESCRIPTION:
Node Name=W31
XS GIS Cut Line= 4
304410.662701668 5380548.3719592303974.9030593485380498.61142335
303829.4249853855380469.21053991303554.3394938215380413.61620701
#Sta/Elev= 27
 421.112      28 423.112   27.16 518.112   25.35 535.312   25.41 537.312   24.74
 539.712   24.41 540.812   24.73 548.112   24.81 558.612   25.13 560.112   24.31
 564.512   24.51 578.112   24.35 584.512   24.51 589.812   25.29 604.212   24.61
 608.112    25.4 839.022  25.103 891.672      24 946.234  24.072 969.907  24.383
1037.682   24.971092.819  25.1471180.002  25.7921196.746      26 1248.56  26.266
1254.896   27.151258.759  27.419
#Mann= 3 , 0 , 0
 421.112      .1       0 535.312    .035       0 608.112      .1       0
#XS Ineff= 2 , 0
       0     520      27     626       0      27
Permanent Ineff=
       F       F
Bank Sta=535.312,608.112
XS Rating Curve= 0 ,0
Exp/Cntr=0.5,0.3

Type RM Length L Ch R = 1 ,6699.612,174.266,215.182,71.29
BEGIN DESCRIPTION:
1996 Survey Section (631.00)
END DESCRIPTION:
Node Name=W30
XS GIS Cut Line= 4
  304337.34655055380440.25391269303885.2392684315380440.25533154
303835.9968712245380432.22324907303543.9179118895380384.58133028
#Sta/Elev= 30
  279.74      28  296.74      26  396.74    24.9  423.04   24.89  424.04   24.21
  439.34   24.76  440.54   23.82  446.74    21.8  453.04   23.82  453.44   24.21
  454.64   24.59  456.14   24.02  461.44   23.85  462.24   24.17  467.74   24.01
  469.44   25.03  481.74    24.9  571.74    25.6  596.74    26.2  676.74    24.8
 710.405      24 728.945  23.799 729.943      24 891.661  24.779 961.754  25.309
1020.043      261069.432   26.231074.301  27.5211076.224  29.0361077.679  29.856
#Mann= 3 , 0 , 0
  279.74      .1       0  423.04    .035       0  469.44      .1       0
Levee=0,,,-1,597.64,26.19,,Levee 32
Bank Sta=423.04,469.44
XS Rating Curve= 0 ,0
Exp/Cntr=0.3,0.1

Type RM Length L Ch R = 1 ,6484.431,616.58,562.375,435.815
BEGIN DESCRIPTION:
1996 Survey Section (633.00)
END DESCRIPTION:
Node Name=W29
XS GIS Cut Line= 6
304218.8051609775380263.84443487303882.7370809715380415.61423989
303815.8542459355380406.09868082303776.2530289295380400.46453389
303736.6518119225380394.83038696303716.851203419 5380392.0133135
#Sta/Elev= 28
 662.342   27.16 684.542   27.15 692.342    26.8 699.742   26.74 708.442   25.67
 711.742    26.4 724.842   26.67 736.342   26.65 740.942   25.46 743.242   26.04
 752.342   25.71 777.442    25.8 779.242   24.88 782.342   24.96 787.742   24.62
 797.042   25.06 800.742   25.78 803.742    24.9 808.242   24.75 812.342   24.51
 814.842   24.75 822.842   26.38 824.842   25.61 845.642   25.08 849.642    25.5
 882.842   25.92 962.342   25.961152.342      28
#Mann= 3 , 0 , 0
 662.342      .1       0 777.442    .035       0 822.842      .1       0
Levee=-1,725.54,26.67,0,,,Levee 33,
Bank Sta=777.442,822.842
XS Rating Curve= 0 ,0
Exp/Cntr=0.3,0.1

Type RM Length L Ch R = 1 ,5922.055,190,176.792,190
BEGIN DESCRIPTION:
1996 Survey Section (629.00)
END DESCRIPTION:
Node Name=W28
XS GIS Cut Line= 5
303806.3940636145379865.06548458303806.3940636145379865.06548459
303807.1977242375380045.09012081303807.7377673825380166.06291441
303809.8296566035380634.65822074
#Sta/Elev= 30
       0  28.005    4.84  28.099  10.284  27.979  20.749  27.202  26.643  26.969
  28.642  27.036  32.783  26.964  33.969  26.865  35.824  26.942  38.408  26.772
  46.464  26.742   61.26  26.262  67.129  26.159  71.974  25.755  75.361  25.085
  79.394      24    83.9   22.98    84.2   22.62    88.4   22.27    92.4   22.57
      93   23.58     123   23.27     153   23.19     288      24     301      26
   359.3      26   369.2      24   511.1      24   722.3      26   769.6      28
#Mann= 3 , 0 , 0
       0      .1       0  79.394    .035       0      93      .1       0
Levee=0,,,-1,301,26,,
Bank Sta=79.394,93
XS Rating Curve= 0 ,0
Exp/Cntr=0.3,0.1

Type RM Length L Ch R = 1 ,5745.264,259.064,255.295,179.874
Node Photo=\HecRas Photos\W27 Bridge.JPG
BEGIN DESCRIPTION:
1996 Survey Section (629.10)
END DESCRIPTION:
Node Name=W27
XS GIS Cut Line= 6
303897.5228163715379641.80152513303866.3019902455379693.03880746
 303855.895046885379710.11790374303587.1544735345380151.15481206
 303562.709615165380191.27188343 303214.336106165380762.99640356
#Sta/Elev= 27
  93.678      27 113.678      26 173.678      25 233.678    24.9 288.678      25
 391.678      25 392.438    24.4 392.448    22.7  395.22    22.1  398.07    22.1
 400.668    22.7 508.678      25 593.678    25.2 642.678    24.9 835.075  24.758
 842.339  25.047 843.953   25.09 846.085  25.144  850.64  25.351 851.731  25.385
 853.006  25.422 858.585  25.677 862.203  25.834 863.076  25.865  866.08      26
  959.28      26 1368.18      28
#Mann= 3 , 0 , 0
  93.678      .1       0 391.678     .03       0 508.678      .1       0
Bank Sta=391.678,508.678
XS Rating Curve= 0 ,0
Exp/Cntr=0.3,0.1

Type RM Length L Ch R = 1 ,5489.969,206.291,264.387,162.343
BEGIN DESCRIPTION:
1996 Survey Section (628.00)
END DESCRIPTION:
Node Name=W26
XS GIS Cut Line= 5
 303607.16580327 5379737.9517642 303581.974259415379790.68003419
303516.1120998545379928.53572699303506.5336260075379948.58437339
303385.5403483635380201.83468018
#Sta/Elev= 25
 240.427  29.647 253.378      28 258.267      26 265.073      24 275.864  23.942
 318.864   22.53 373.864   22.57 395.464   22.99 396.364   22.21 400.864      21
 402.864    22.2 403.264   22.68 437.476  22.739  473.44  23.601 482.386      24
  494.76  24.339 496.719  24.577  498.15  24.651 500.539  24.553 504.347   24.21
 505.833      24 728.519  25.403 729.346      26 734.223      28 754.533  27.723
#Mann= 3 , 0 , 0
 240.427      .1       0 395.464     .03       0 403.264      .1       0
Bank Sta=395.464,403.264
XS Rating Curve= 0 ,0
Exp/Cntr=0.3,0.1

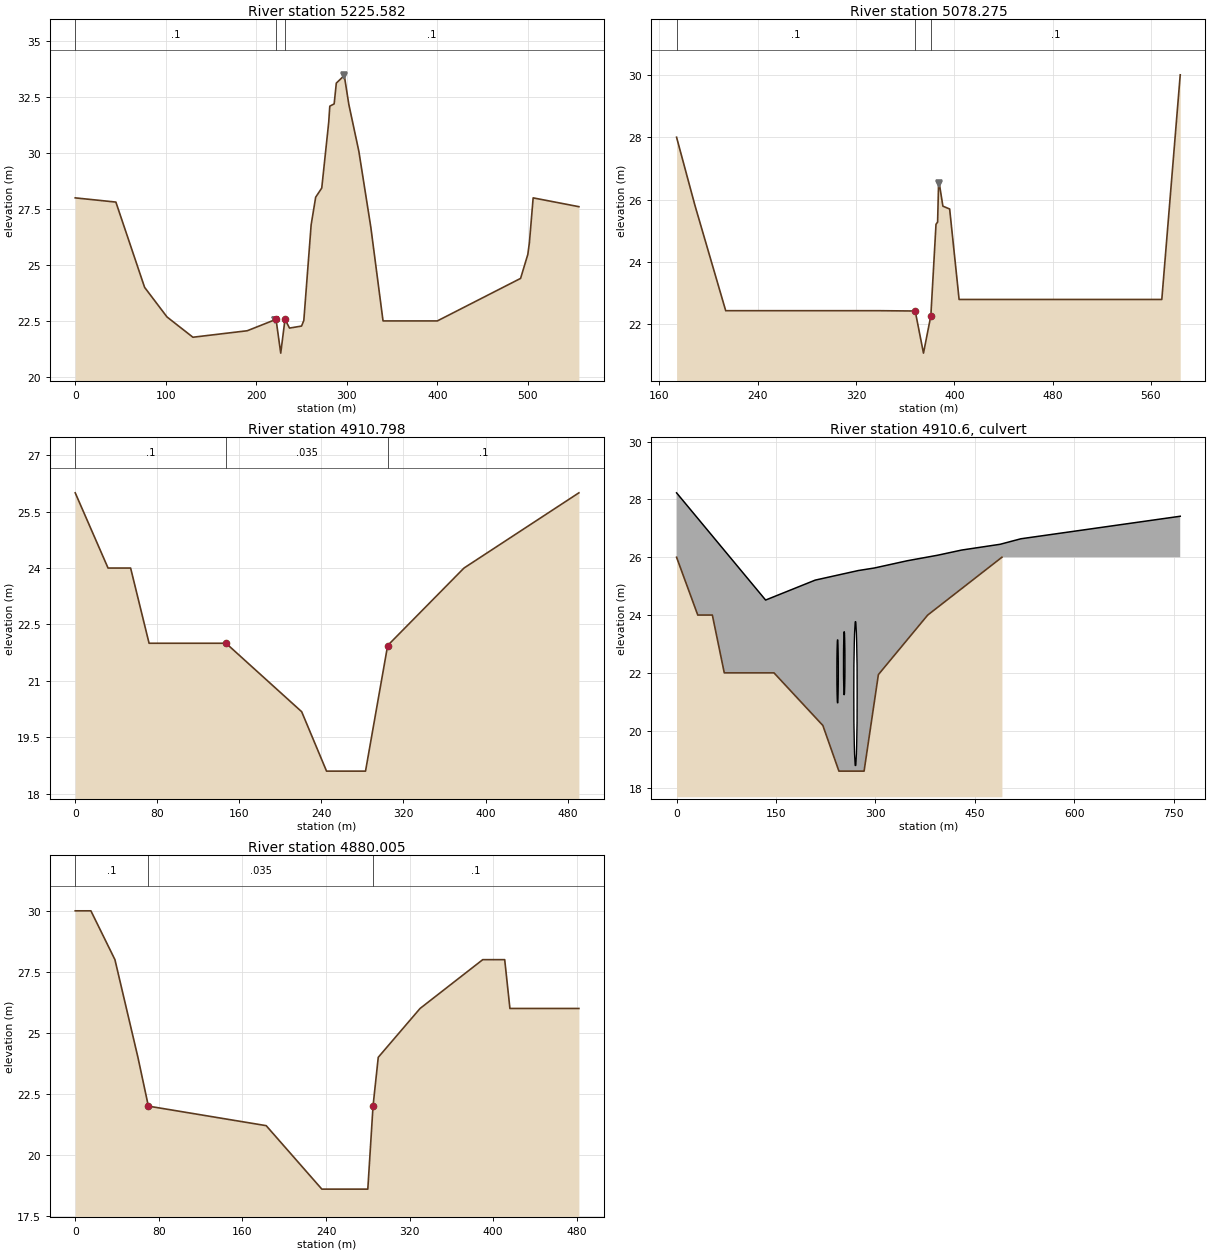
Type RM Length L Ch R = 1 ,5225.582,86.513,147.307,158.26
BEGIN DESCRIPTION:
1996 Survey Section (627.00)
END DESCRIPTION:
Node Name=W25
XS GIS Cut Line= 3
303397.6071004285379601.05336699303332.0186180245380036.13714577
303314.6786496865380151.16250803
#Sta/Elev= 30
       0      28  44.896  27.812  76.636      24 101.349  22.678     130   21.77
     190   22.06   221.8   22.57     227   21.06   231.7   22.57   236.7   22.18
     250   22.27   252.5   22.52   260.6    26.8   265.6   28.03   272.3   28.44
     280   31.38   281.2    32.1     286    32.2   288.4   33.13   297.2   33.47
   302.2   32.18   313.3   30.08   326.5   26.69     340    22.5     400    22.5
 491.924    24.4 499.908  25.472 501.669      26 505.808      28 556.325  27.606
#Mann= 3 , 0 , 0
       0      .1       0   221.8     .03       0   231.7      .1       0
Levee=-1,220.56,22.52,-1,297.36,33.5,Levee 34,Levee 35
Bank Sta=221.8,231.7
XS Rating Curve= 0 ,0
Exp/Cntr=0.3,0.1

Type RM Length L Ch R = 1 ,5078.275,131.874,182.721,103.016
BEGIN DESCRIPTION:
1996 Survey Section (626.00)
END DESCRIPTION:
Node Name=W24
XS GIS Cut Line= 2
 303352.251843395379637.18626122303130.9721827245379982.34539722
#Sta/Elev= 17
 173.918      28 188.918   25.81 213.918   22.44 338.818   22.44 367.918   22.43
 368.918   22.28 374.918   21.08 380.918   22.28 385.118   25.21 386.418   25.28
  387.22   26.53 387.618   26.56 390.718   25.79 396.218    25.7 403.918    22.8
 568.918    22.8 583.918      30
#Mann= 3 , 0 , 0
 173.918      .1       0 367.918     .03       0 380.918      .1       0
Levee=0,,,-1,387.22,26.51,,Levee 35
Bank Sta=367.918,380.918
XS Rating Curve= 0 ,0
Exp/Cntr=0.3,0.1

Type RM Length L Ch R = 1 ,4910.798,35,30.793,35
BEGIN DESCRIPTION:
1:2500 Community Mapping Section
END DESCRIPTION:
Node Name=490us
XS GIS Cut Line= 4
 303282.70595662 5379418.2374223303233.2754357335379582.20207694
303174.4464749665379777.34204437303135.1536623475379916.66644125
#Sta/Elev= 11
       0      26      32      24      54      24      72      22     147      22
  220.75   20.18     245    18.6     283    18.6  304.58   21.94     379      24
     491      26
#Mann= 3 , 0 , 0
       0      .1       0     147    .035       0  304.58      .1       0
Bank Sta=147,304.58
XS Rating Curve= 0 ,0
Exp/Cntr=0.5,0.3

Type RM Length L Ch R = 2 ,4910.6  ,,,
Node Photo=\HecRas Photos\Culverts.JPG
BEGIN DESCRIPTION:
Route 490 Culverts
END DESCRIPTION:
Bridge Culvert--1,0,-1,-1, 0
Deck Dist Width WeirC Skew NumUp NumDn MinLoCord MaxHiCord MaxSubmerge Is_Ogee
1,20,1.6,0, 11, 11, , , 0.98, 0, 1,1,,
       0  134.37  209.24  274.03  298.69  348.17  393.74  430.23  488.38  519.55
  760.07
   28.23   24.52   25.21   25.54   25.63   25.88   26.07   26.25   26.45   26.64
   27.42
       0       0       0       0       0       0       0       0       0       0
       0
       0  134.37  209.24  274.03  298.69  348.17  393.74  430.23  488.38  519.55
  760.07
   28.23   24.52   25.21   25.54   25.63   25.88   26.07   26.25   26.45   26.64
   27.42
       0       0       0       0       0       0       0       0       0       0
       0
BR Coef=-1 , 0 , 0 ,, 0 ,,,0.8,-1,,0,
WSPro=,,,, 1 ,,,, 0 ,,,, 0 ,,,,-1 ,-1 ,-1 , 0 , 0 , 0 , 0 , 0
Culvert=1,2.2,,30.01,0.024,0.9,1,2,3,20.95,243,20.84,243,Culvert #2  , 0 ,0.5
Culvert Bottom n=0.024
Culvert=1,2.2,,29.76,0.024,0.9,1,2,3,21.23,253,20.8,253,Culvert #3  , 0 ,0.5
Culvert Bottom n=0.024
Culvert=1,5,,25.57,0.024,0.9,1,2,3,18.78,270,18.9,270,Culvert #1  , 0 ,0.5
Culvert Bottom n=0.024
BC Design=,, 0 ,, 0 ,,,,,,
BC Use User HTab Curves=0
BC User HTab FreeFlow(D)= 0

Type RM Length L Ch R = 1 ,4880.005,330,319.623,330
BEGIN DESCRIPTION:
1:2500 Community Mapping Section
END DESCRIPTION:
Node Name=490ds
XS GIS Cut Line= 4
303256.8410883945379404.41309618303203.1435289995379577.89751884
 303147.184273635379758.68895924303110.1766013985379878.25220799
#Sta/Elev= 16
       0      30      15      30      38      28      49      26      60      24
      70      22  182.75    21.2     236    18.6     280    18.6     285      22
     290      24     330      26     390      28     411      28     416      26
     482      26
#Mann= 3 , 0 , 0
       0      .1       0      70    .035       0     285      .1       0
Bank Sta=70,285
XS Rating Curve= 0 ,0
Exp/Cntr=0.5,0.3

River Reach=Blanche Brook   ,DS of Confluence
Reach XY= 30
299764.8049859475379000.93201073299770.480056052 5378959.0906807
299763.876580931 5378930.8142616299737.2933605765378866.98066877
299682.9416807415378801.79251695299609.6261749195378755.06023148
299546.6391814655378699.01535289299514.9763648635378679.54356728
299424.0515920565378653.63762642299312.6391143855378635.52039981
 299273.187583545378605.55078196299253.8851178045378554.58549962
299241.8634066885378439.44798471299241.016807313   5378378.15419
 299209.692630465378324.14114992299189.0356057265378302.63752581
299171.4263387385378289.93853519299108.608665161 5378277.0702247
299069.4957740625378277.40886445298989.0688334975378293.15561282
298931.1614362885378293.15561282298884.0905110735378283.50437995
298823.1353561195378247.94720622298810.9443251275378221.36398587
298812.4682040015378201.55356051298828.8922318635378164.64182778
298890.0167066965378102.50143371298992.7938707455378030.87912663
299011.5883768555378009.03686277 299013.112255735377986.17867966

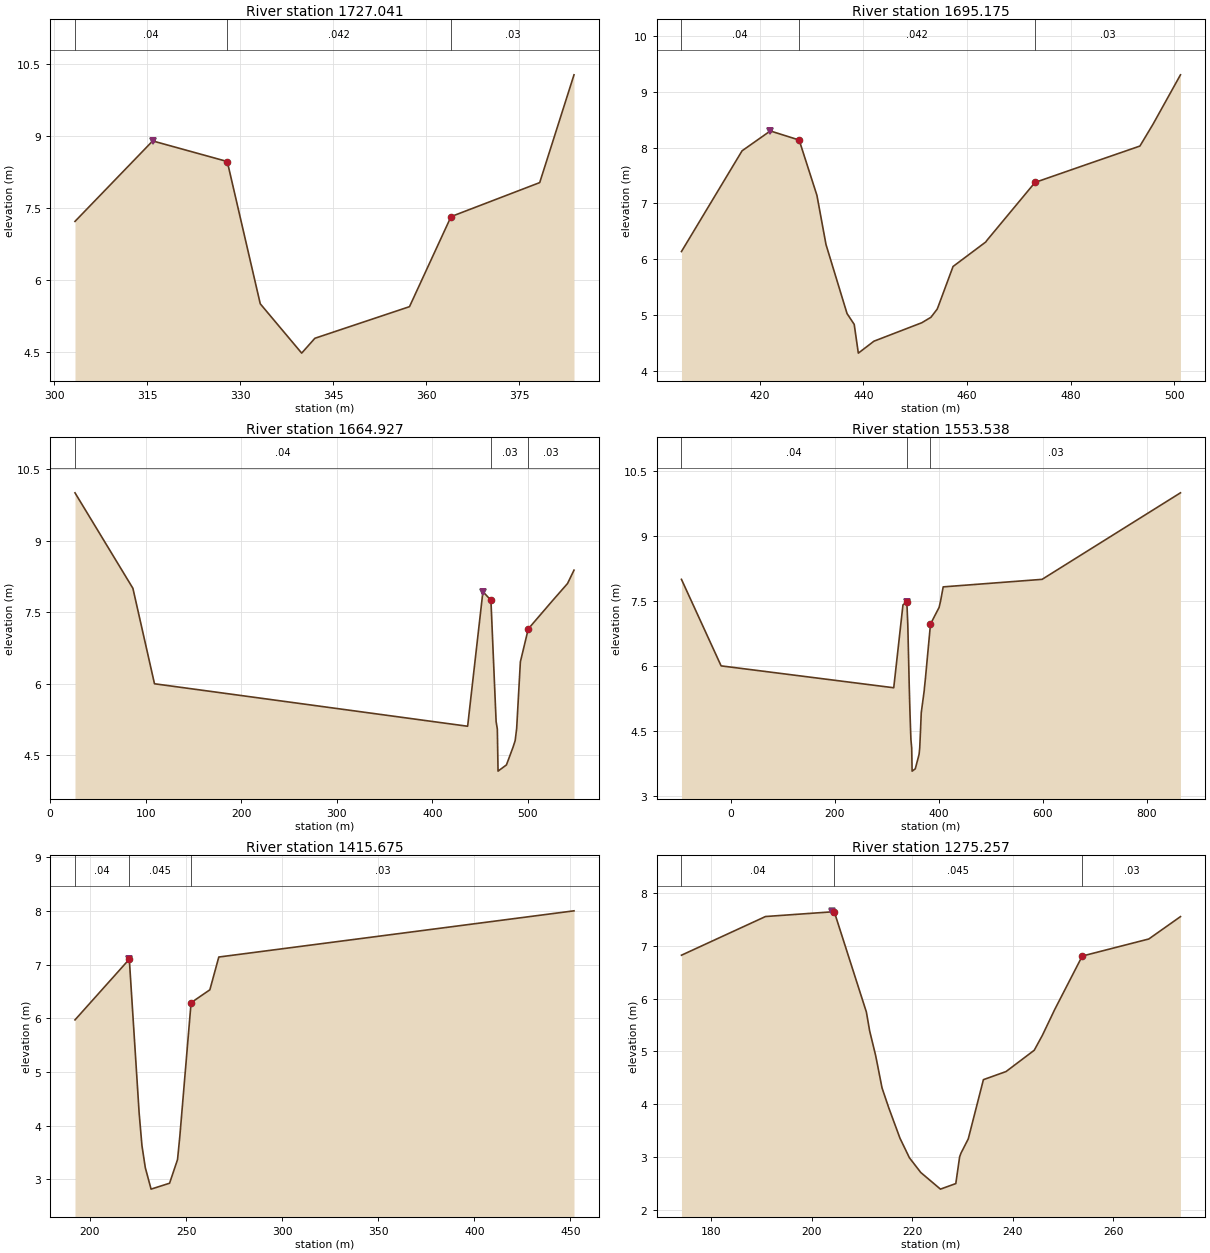
Type RM Length L Ch R = 1 ,1727.041,38.425,31.866,27.978
Node Photo=\HecRas Photos\BB11.JPG
BEGIN DESCRIPTION:
2008 Survey Section
END DESCRIPTION:
Node Name=BB11
XS GIS Cut Line= 3
299807.7864269475378971.57526448299733.2779646595378976.35237414
299727.4708878445378976.72469484
#Sta/Elev= 10
 303.369    7.22 315.899     8.9  327.93    8.47 333.249     5.5 339.929    4.47
 342.059    4.78 357.319    5.44 364.019    7.32 378.319    8.03 383.849   10.28
#Mann= 3 , 0 , 0
 303.369     .04       0  327.93    .042       0 364.019     .03       0
Levee=-1,315.94,8.9,0,,,Levee 14,
Bank Sta=327.93,364.019
XS Rating Curve= 0 ,0
Exp/Cntr=0.3,0.1

Type RM Length L Ch R = 1 ,1695.175,33,30.247,29.947
BEGIN DESCRIPTION:
Interpolated Section
END DESCRIPTION:
Node Name=BB10a
XS GIS Cut Line= 3
299799.994839391 5378935.1190029299718.8196115125378953.47964996
299706.0696942955378956.36349441
#Sta/Elev= 22
 404.903   6.137 416.601   7.943  422.05   8.299 427.618   8.136 431.047   7.144
 432.799   6.262 436.859   5.025 438.242   4.831 439.036   4.316 442.051    4.53
 451.292   4.861 453.052   4.959 454.256   5.105 454.507   5.165 457.315   5.869
  463.65    6.31 463.783    6.33 473.133   7.376 483.587   7.714 493.374   8.028
 495.906    8.42 501.201   9.305
#Mann= 3 , 0 , 0
 404.903     .04       0 427.618    .042       0 473.133     .03       0
Levee=-1,421.96,8.29,0,,,Levee 14,
Bank Sta=427.618,473.133
XS Rating Curve= 0 ,0
Exp/Cntr=0.3,0.1

Type RM Length L Ch R = 1 ,1664.927,121.636,111.389,102.212
Node Photo=\HecRas Photos\BB10.JPG
BEGIN DESCRIPTION:
2008 Survey Section
END DESCRIPTION:
Node Name=BB10
XS GIS Cut Line= 3
300189.4991452055378796.63387466299792.9686280485378904.34813455
299685.5516430365378933.52707675
#Sta/Elev= 19
  26.066      10  86.666       8 109.266       6 436.966    5.11 452.956    7.93
 461.346    7.75 466.766    5.21 468.056    5.05 468.796    4.17  477.57     4.3
 484.466    4.67 486.716    4.81 488.256    5.06 488.576    5.17 492.166    6.46
 500.436    7.15 525.756    7.74 541.506     8.1 548.276    8.38
#Mann= 3 , 0 , 0
  26.066     .04       0 461.346     .03       0 500.436     .03       0
Levee=-1,453.22,7.93,0,,,Levee 14,
Bank Sta=461.346,500.436
XS Rating Curve= 0 ,0
Exp/Cntr=0.3,0.1

Type RM Length L Ch R = 1 ,1553.538,157.692,137.863,125.752
BEGIN DESCRIPTION:
Interpolated Section
END DESCRIPTION:
Node Name=BB9a
XS GIS Cut Line= 4
300092.0795532485378629.07319585299725.3013170545378807.32741864
299630.6613077975378853.32246314  299220.71154245379052.55804913
#Sta/Elev= 29
 -94.377       8 -18.177       6 313.423   5.494 331.152   7.409 338.622   7.479
 340.455   6.945 343.196   5.536 344.489   4.966 346.041    4.42 346.465   4.292
 347.895   4.108 348.716   3.567  354.78    3.62 360.488   3.879 362.178   3.961
 363.335   4.103 363.576   4.165 365.033   4.554 366.273   4.917 372.047   5.434
 372.486   5.502 374.064    5.68 383.993   6.963 391.507   7.141 400.547   7.351
 403.339   7.495 408.425   7.826 598.425       8 864.225      10
#Mann= 3 , 0 , 0
 -94.377     .04       0 338.622     .03       0 383.993     .03       0
Levee=-1,338.37,7.48,0,,,Levee 14,
Bank Sta=338.622,383.993
XS Rating Curve= 0 ,0
Exp/Cntr=0.3,0.1

Type RM Length L Ch R = 1 ,1415.675,158.169,140.419,140.146
Node Photo=\HecRas Photos\BB09.JPG
BEGIN DESCRIPTION:
2008 Survey Section
END DESCRIPTION:
Node Name=BB9
XS GIS Cut Line= 3
299626.2413460285378705.45654513  299570.34668825378755.19468992
299432.2916858035378878.04363408
#Sta/Elev= 13
 192.244    5.97 220.504     7.1 225.634    4.23 227.084    3.63 228.824    3.22
 231.824    2.82 241.454    2.93 245.594    3.37 246.784     3.8 252.644    6.29
 262.414    6.53 267.064    7.14 451.864       8
#Mann= 3 , 0 , 0
 192.244     .04       0 220.504    .045       0 252.644     .03       0
Levee=-1,220.36,7.1,0,,,Levee 14,
Bank Sta=220.504,252.644
XS Rating Curve= 0 ,0
Exp/Cntr=0.3,0.1

Type RM Length L Ch R = 1 ,1275.257,168.064,166.177,163.118
BEGIN DESCRIPTION:
Interpolated Section
END DESCRIPTION:
Node Name=BB8a
XS GIS Cut Line= 2
299491.2122140655378643.65235928299425.9659520055378718.40909343
#Sta/Elev= 25
 174.101    6.82 190.812   7.552 204.481   7.644 210.871   5.745 211.531   5.384
 212.689   4.932 212.969     4.8 213.987   4.308  215.33    3.93 217.546   3.358
 219.432   2.986 221.696   2.707   225.6   2.393 228.654   2.498 229.417   3.005
 229.684   3.074 231.131   3.344 234.144   4.465 238.642   4.618 244.249   5.021
  245.86   5.302 248.325   5.793 253.797   6.804 267.029   7.127 273.326    7.55
#Mann= 3 , 0 , 0
 174.101     .04       0 204.481    .045       0 253.797     .03       0
Levee=-1,204.13,7.66,0,,,Levee 14,
Bank Sta=204.481,253.797
XS Rating Curve= 0 ,0
Exp/Cntr=0.3,0.1

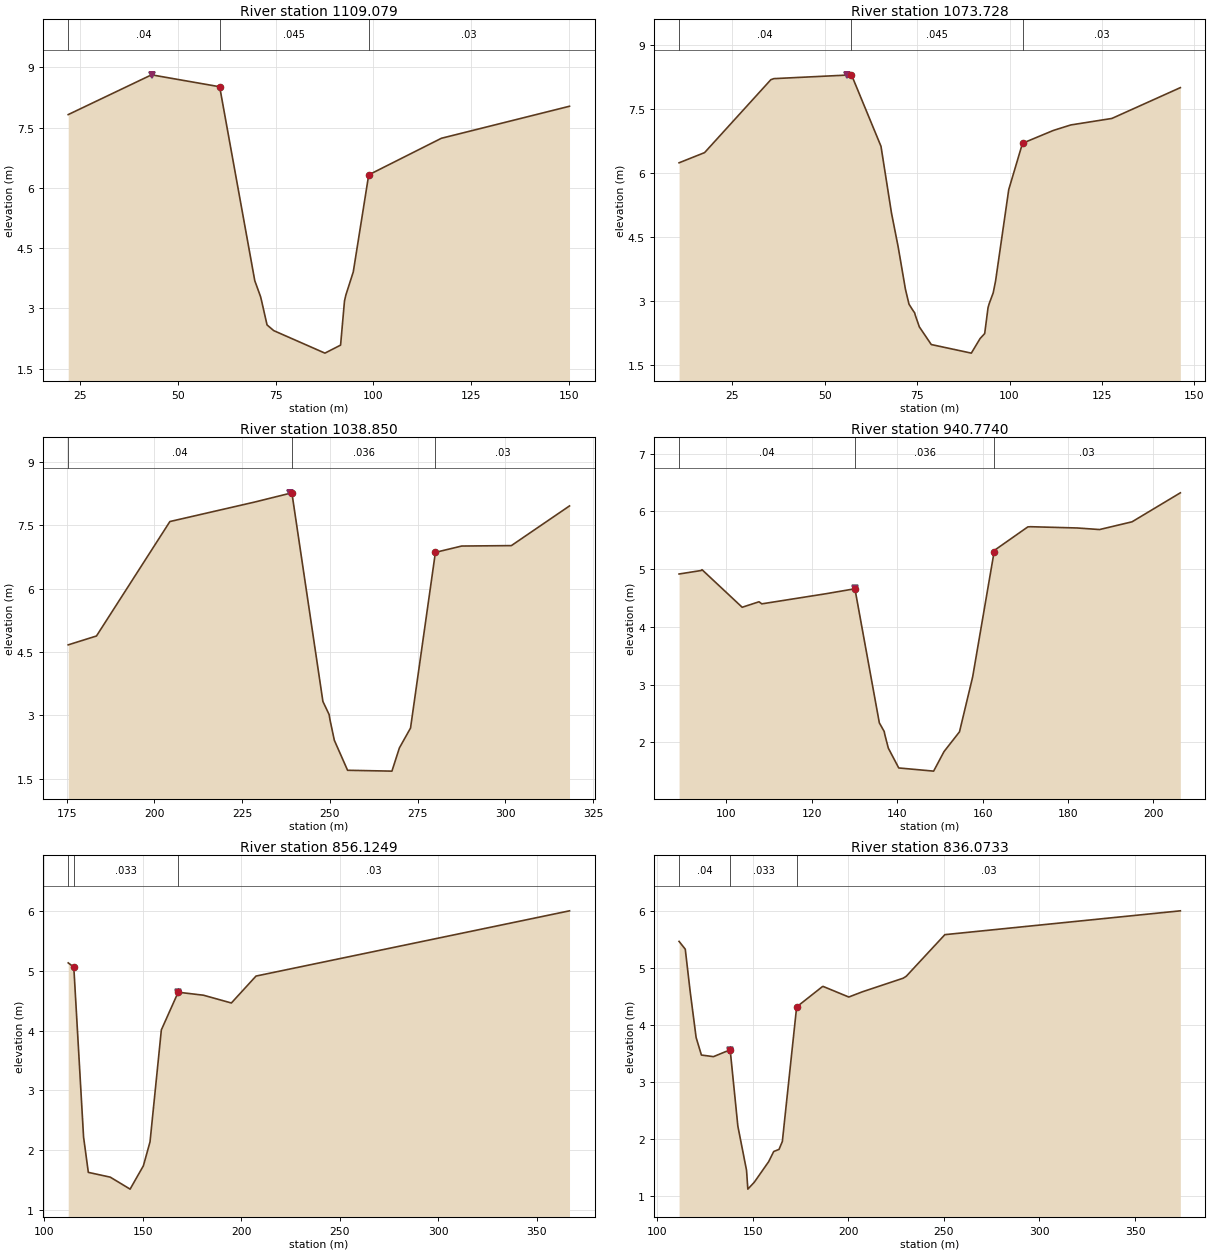
Type RM Length L Ch R = 1 ,1109.079,14.535,35.351,37.238
Node Photo=\HecRas Photos\BB08.JPG
BEGIN DESCRIPTION:
2008 Survey Section
END DESCRIPTION:
Node Name=BB8
XS GIS Cut Line= 2
299337.5536422835378578.67410541299279.4347148645378692.83831755
#Sta/Elev= 16
      22  7.8266  43.288  8.8167  60.701  8.5196  69.681  3.6886  71.157  3.2922
  71.513  3.1466   72.81  2.5897  74.521   2.447  87.603   1.887  91.603   2.086
  92.603  3.1863  92.952  3.3331  94.847  3.9095  98.793  6.3259 117.365  7.2368
 150.107  8.0342
#Mann= 3 , 0 , 0
      22     .04       0  60.701    .045       0  98.793     .03       0
Levee=-1,43.46,8.8,0,,,Levee 14,
Bank Sta=60.701,98.793
XS Rating Curve= 0 ,0
Exp/Cntr=0.3,0.1

Type RM Length L Ch R = 1 ,1073.728,15.434,34.878,36.514
BEGIN DESCRIPTION:
Interpolated Section
END DESCRIPTION:
Node Name=BB7a
XS GIS Cut Line= 2
299339.5825045725378565.28433151299234.883828444 5378651.3353084
#Sta/Elev= 30
  10.653   6.238  17.548   6.476  35.468   8.183  36.292   8.208  56.095   8.291
  57.264   8.297  65.243   6.624  68.079   5.063  69.857   4.283  70.285    4.07
  71.847    3.28  72.815   2.929  73.908   2.779  74.331   2.728  74.537   2.664
  75.607   2.398  78.837   1.984  89.664   1.783  92.043   2.125   93.28   2.241
  94.184   2.848    94.5   2.942  95.583   3.195  96.213   3.467  99.781   5.611
 103.502   6.695 111.867   6.996 116.573   7.124  127.67   7.276 146.176   7.997
#Mann= 3 , 0 , 0
  10.653     .04       0  57.264    .045       0 103.502     .03       0
Levee=-1,56.09,8.29,0,,,Levee 14,
Bank Sta=57.264,103.502
XS Rating Curve= 0 ,0
Exp/Cntr=0.3,0.1

Type RM Length L Ch R = 1 ,1038.850,97.122,98.076,97.578
Node Photo=\HecRas Photos\BB07.JPG
BEGIN DESCRIPTION:
2008 Survey Section
END DESCRIPTION:
Node Name=BB7
XS GIS Cut Line= 2
299346.6748915995378558.28651821299210.1001466295378600.12819631
#Sta/Elev= 17
 175.444    4.67 183.494    4.88 204.414    7.59 228.494    8.05 239.174    8.27
 248.014    3.33 249.784    3.02 250.024     2.9 251.274    2.41 255.044     1.7
 267.684    1.68 269.814    2.23 272.984     2.7 280.074    6.86 287.564    7.01
 301.714    7.02 318.284    7.96
#Mann= 3 , 0 , 0
 175.444     .04       0 239.174    .036       0 280.074     .03       0
Levee=-1,238.7,8.26,0,,,Levee 14,
Bank Sta=239.174,280.074
XS Rating Curve= 0 ,0
Exp/Cntr=0.3,0.1

Type RM Length L Ch R = 1 ,940.7740,81.937,84.649,84.827
BEGIN DESCRIPTION:
Interpolated Section
END DESCRIPTION:
Node Name=BB6a
XS GIS Cut Line= 2
299289.5190004735378475.50399297  299176.63230175378507.59647093
#Sta/Elev= 27
   88.93   4.917  94.131   4.978  94.298   4.992 103.705   4.341 107.647   4.436
 108.295     4.4 123.204   4.574 129.424   4.653 130.104   4.659 135.816   2.339
 136.959   2.189 137.114   2.132 137.922   1.901 140.358   1.558 148.524   1.503
 150.956   1.841 154.575   2.183 154.621   2.196 157.665   3.135 162.669   5.293
 162.859   5.332 170.583   5.733 171.219   5.736 182.172   5.714 187.373   5.687
  194.98   5.821  206.29   6.323
#Mann= 3 , 0 , 0
   88.93     .04       0 130.104    .036       0 162.669     .03       0
Levee=-1,130.08,4.68,0,,,Levee 14,
Bank Sta=130.104,162.669
XS Rating Curve= 0 ,0
Exp/Cntr=0.3,0.1

Type RM Length L Ch R = 1 ,856.1249,20.593,20.052,19.351
Node Photo=\HecRas Photos\BB06.JPG
BEGIN DESCRIPTION:
2008 Survey Section
END DESCRIPTION:
Node Name=BB6
XS GIS Cut Line= 3
299262.0412684325378398.81673008 299169.088876585378420.15556043
299013.9250261235378455.77610785
#Sta/Elev= 14
 112.121    5.13 114.951    5.06 119.911    2.22 122.331    1.63 133.471    1.55
 143.541    1.35 150.291    1.74 153.661    2.14 159.411    4.01 167.961    4.64
 180.791    4.59 194.971    4.46 207.491    4.91 366.691       6
#Mann= 3 , 0 , 0
 112.121     .04       0 114.951    .033       0 167.961     .03       0
Levee=0,,,-1,167.98,4.63,,Levee 15
Bank Sta=114.951,167.961
XS Rating Curve= 0 ,0
Exp/Cntr=0.3,0.1

Type RM Length L Ch R = 1 ,836.0733,22.384,21.424,19.965
BEGIN DESCRIPTION:
Interpolated Section
END DESCRIPTION:
Node Name=BB5a
XS GIS Cut Line= 3
299268.8219511995378376.18757931299134.3559988055378411.67550076
299015.2347044835378443.11369802
#Sta/Elev= 26
  111.46   5.464   114.7   5.327 117.229   4.595  120.38   3.778 123.151    3.47
 129.445   3.442 135.907   3.531 138.226    3.55 142.215   2.223  146.76   1.448
 147.438   1.118 150.789   1.238  158.32   1.599 160.976   1.778 163.752   1.815
 165.493   1.954 172.955   4.308 173.022   4.315   186.4   4.669 186.805   4.674
  200.25   4.488 207.488   4.581 228.713   4.818 230.347   4.853  250.53   5.582
  373.73       6
#Mann= 3 , 0 , 0
  111.46     .04       0 138.226    .033       0 173.022     .03       0
Levee=-1,138.2,3.55,0,,,Levee 16,
Bank Sta=138.226,173.022
XS Rating Curve= 0 ,0
Exp/Cntr=0.3,0.1

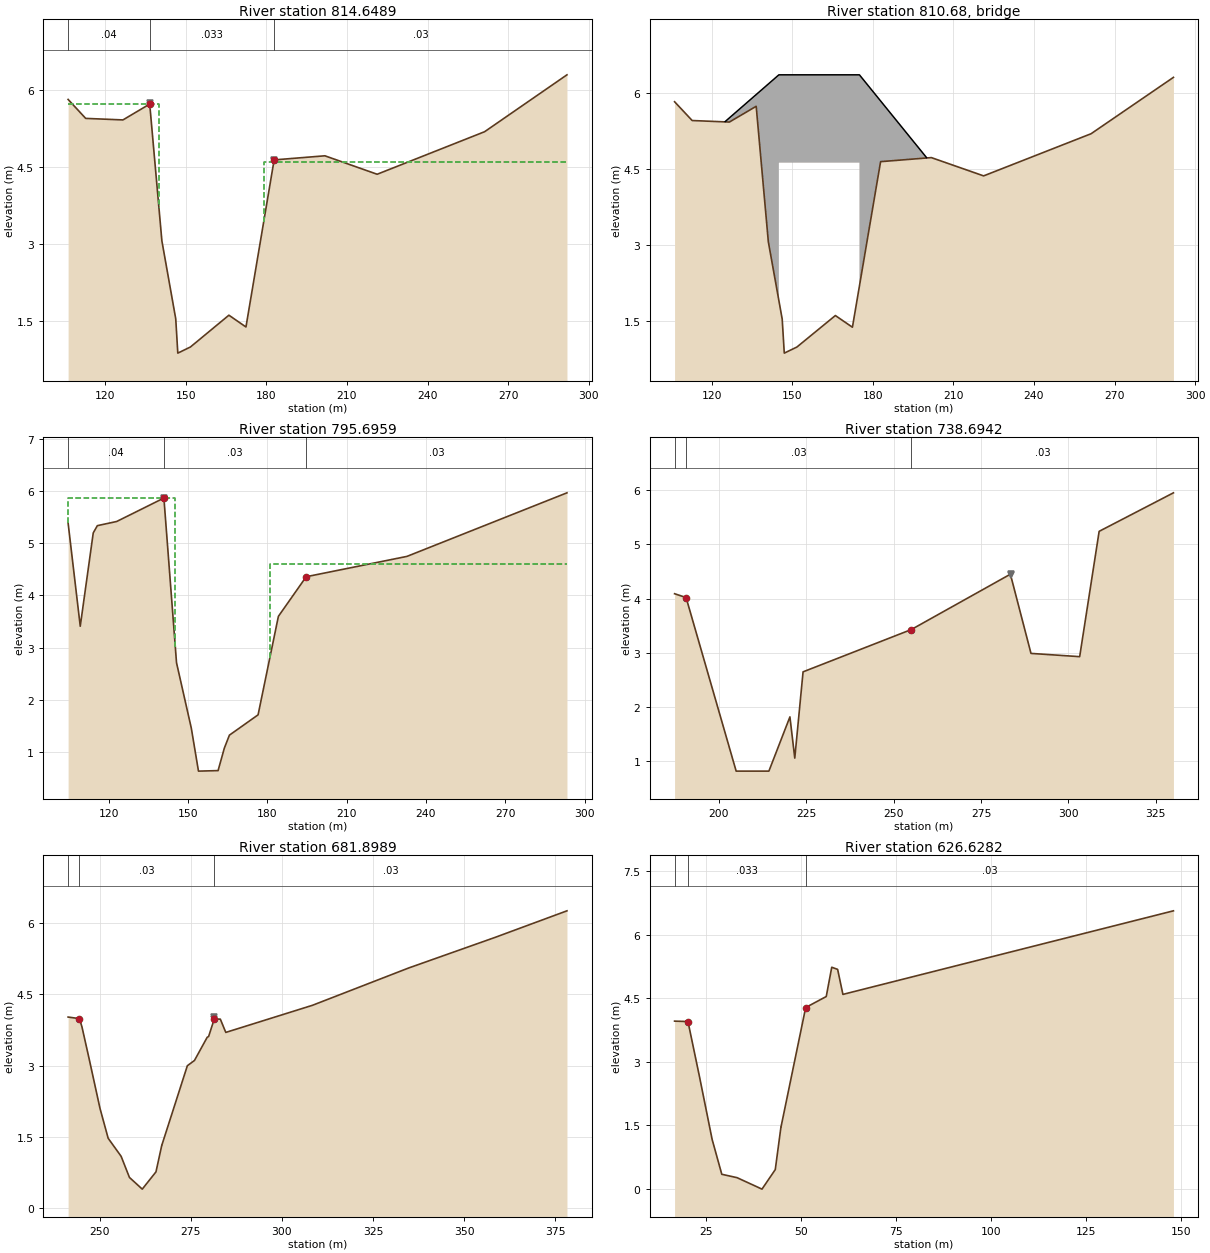
Type RM Length L Ch R = 1 ,814.6489,18.459,18.953,19.95
Node Photo=\HecRas Photos\BB05.JPG
BEGIN DESCRIPTION:
2008 Survey Section
END DESCRIPTION:
Node Name=BB5
XS GIS Cut Line= 2
299276.9551404685378350.11388619  299099.7180702 5378405.7680387
#Sta/Elev= 15
 106.164    5.82 112.714    5.45 126.584    5.42 136.554    5.73 141.084    3.06
 146.244    1.54 147.014     .87 151.724     .99 166.044    1.61 172.394    1.38
 182.884    4.64 201.784    4.72 221.254    4.36 261.264    5.19 291.934     6.3
#Mann= 3 , 0 , 0
 106.164     .04       0 136.554    .033       0 182.884     .03       0
Levee=-1,136.59,5.75,-1,182.82,4.63,Levee 16,Levee 17
#XS Ineff= 2 , 0
       0     140    5.73     179       0     4.6
Permanent Ineff=
       F       F
Bank Sta=136.554,182.884
XS Rating Curve= 0 ,0
Exp/Cntr=0.5,0.3

Type RM Length L Ch R = 3 ,810.68  ,,,
Node Photo=\HecRas Photos\West St Bridge.JPG
BEGIN DESCRIPTION:
West Street Bridge
END DESCRIPTION:
Bridge Culvert--1,0,-1,-1, 0
Deck Dist Width WeirC Skew NumUp NumDn MinLoCord MaxHiCord MaxSubmerge Is_Ogee
3.97,11.06,1.6,0, 6, 6, , , 0.98, 0, 1,1,,
     125     145     145     175     175     200
    5.43    6.35    6.35    6.35    6.35    4.72
       0       0    4.62    4.62       0       0
  123.09     148     148     178     178   210.5
    5.42    6.35    6.35    6.35    6.35    4.52
       0       0    4.62    4.62       0       0
BR Coef=-1 , 0 , 0 ,, 0 ,,,0.8,-1,,0,
WSPro=,,,, 1 ,,,, 0 ,,,, 0 ,,,,-1 ,-1 ,-1 , 0 , 0 , 0 , 0 , 0
BC Design=,, 0 ,, 0 ,,,,,,
BC Use User HTab Curves=0
BC User HTab FreeFlow(D)= 0

Type RM Length L Ch R = 1 ,795.6959,71.29,57.002,36.886
Node Photo=\HecRas Photos\BB04.JPG
BEGIN DESCRIPTION:
2008 Survey Section
END DESCRIPTION:
Node Name=BB4
XS GIS Cut Line= 3
299273.9015670265378331.84785611299103.7365074265378384.85630912
299093.8644150325378387.93158407
#Sta/Elev= 17
  104.72    5.39  109.31    3.41  114.22     5.2  115.77    5.34  123.09    5.42
  140.93    5.87   145.7    2.71  151.31    1.45     154     .63  161.41     .64
  163.77    1.07  165.69    1.32  176.53    1.71  184.21     3.6  194.72    4.36
  232.79    4.75  293.29    5.97
#Mann= 3 , 0 , 0
  104.72     .04       0  140.93     .03       0  194.72     .03       0
Levee=-1,140.88,5.86,0,,,Levee 16,
#XS Ineff= 2 , 0
       0   145.3    5.87     181       0     4.6
Permanent Ineff=
       F       F
Bank Sta=140.93,194.72
XS Rating Curve= 0 ,0
Exp/Cntr=0.5,0.3

Type RM Length L Ch R = 1 ,738.6942,67.074,56.795,41.781
Node Photo=\HecRas Photos\BB03.JPG
BEGIN DESCRIPTION:
2008 Survey Section
END DESCRIPTION:
Node Name=BB3
XS GIS Cut Line= 3
299199.8787955965378292.15458574299107.6693190495378383.02553655
299098.282487735 5378392.2761073
#Sta/Elev= 13
  187.38    4.09  190.67    4.02  204.99     .82  214.35     .82  220.36    1.82
  221.75    1.06  224.12    2.65  255.08    3.43   283.4    4.45  289.29    2.99
  303.21    2.93  308.78    5.24  330.02    5.95
#Mann= 3 , 0 , 0
  187.38     .04       0  190.67     .03       0  255.08     .03       0
Levee=0,,,-1,283.48,4.45,,Levee 18
Bank Sta=190.67,255.08
XS Rating Curve= 0 ,0
Exp/Cntr=0.3,0.1

Type RM Length L Ch R = 1 ,681.8989,63.606,55.271,49.993
BEGIN DESCRIPTION:
Interpolated Section
END DESCRIPTION:
Node Name=BB2a
XS GIS Cut Line= 3
299139.2552421285378276.84543925299090.8326266115378398.15095988
299088.4799503045378404.04474776
#Sta/Elev= 23
 241.292   4.024 244.413   3.991 245.096   3.817 247.056   3.149 250.043   2.104
 252.289   1.474 255.851   1.094  258.13     .65 261.649    .404 265.414    .767
 267.017   1.329 267.028   1.329  274.03       3 275.983   3.111  279.49     3.6
  279.86   3.613  281.42   3.983 283.087    3.98 284.582   3.701 308.363   4.271
 334.773   5.056 358.443   5.698 378.251   6.259
#Mann= 3 , 0 , 0
 241.292     .04       0 244.413     .03       0  281.42     .03       0
Levee=0,,,-1,281.4,4.03,,Levee 18
Bank Sta=244.413,281.42
XS Rating Curve= 0 ,0
Exp/Cntr=0.3,0.1

Type RM Length L Ch R = 1 ,626.6282,58.72,61.011,61.078
Node Photo=\HecRas Photos\BB02.JPG
BEGIN DESCRIPTION:
2008 Survey Section
END DESCRIPTION:
Node Name=BB2
XS GIS Cut Line= 2
299082.5492337485378262.56919484299085.0328686995378393.97606229
#Sta/Elev= 16
  16.645    3.96  20.175    3.95  23.165    2.67  26.545    1.17  29.085     .35
  33.115     .27  39.675       0  43.175     .46  44.665    1.46  44.675    1.46
  51.185    4.28  56.605    4.54  58.055    5.23  59.605    5.18  60.995    4.59
 148.075    6.56
#Mann= 3 , 0 , 0
  16.645     .04       0  20.175    .033       0  51.185     .03       0
Bank Sta=20.175,51.185
XS Rating Curve= 0 ,0
Exp/Cntr=0.3,0.1

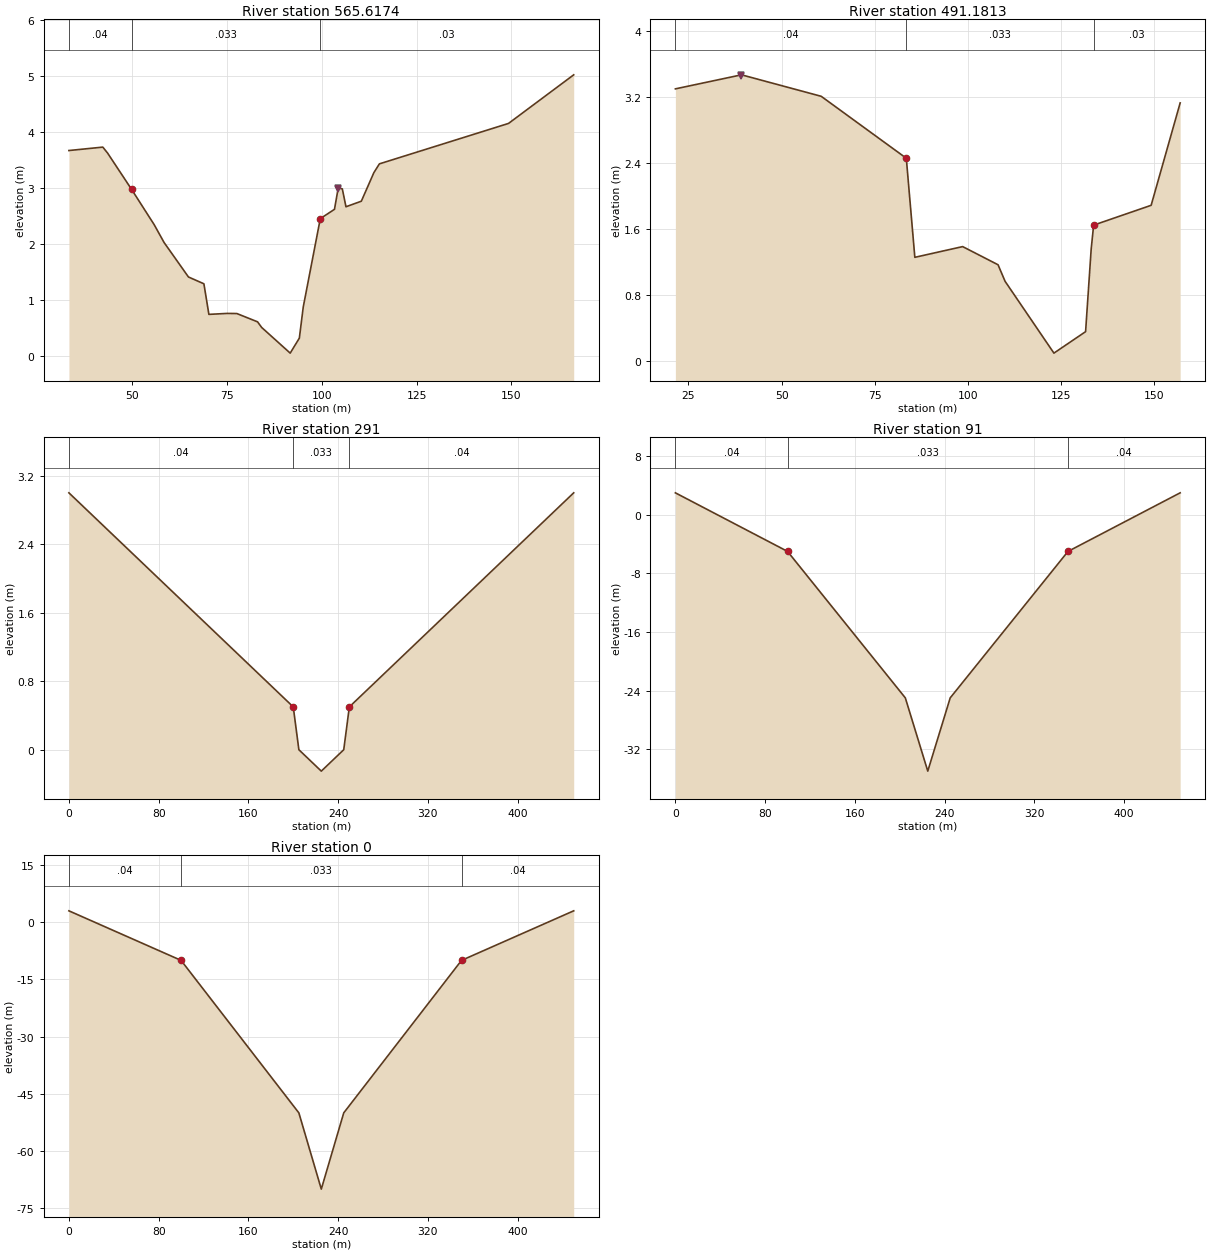
Type RM Length L Ch R = 1 ,565.6174,73.909,74.436,75.815
BEGIN DESCRIPTION:
Interpolated Section
END DESCRIPTION:
Node Name=BB1a
XS GIS Cut Line= 2
299027.9215376945378232.95440991 299015.484348895378365.61775714
#Sta/Elev= 26
  33.236   3.663  42.189   3.724  43.443   3.618  49.773    2.97  55.737    2.34
  58.345   2.022  64.788   1.405   68.87   1.283  70.187    .737  75.009    .754
  77.565    .752  83.028    .604  84.109    .504  91.647    .045  94.064    .313
  95.092    .869  99.593   2.447 103.335   2.613 104.336   2.998 105.406   2.978
 106.366   2.659 110.422   2.758 113.735   3.268 115.193   3.425 149.275   4.147
 166.481   5.015
#Mann= 3 , 0 , 0
  33.236     .04       0  49.773    .033       0  99.593     .03       0
Levee=0,,,-1,104.3,3,,Levee 19
Bank Sta=49.773,99.593
XS Rating Curve= 0 ,0
Exp/Cntr=0.3,0.1

Type RM Length L Ch R = 1 ,491.1813,180,200,230
Node Photo=\HecRas Photos\BB01.JPG
BEGIN DESCRIPTION:
2008 Survey Section
END DESCRIPTION:
Node Name=BB1
XS GIS Cut Line= 2
298957.0029866265378194.29174627298946.2925461565378329.32729963
#Sta/Elev= 14
  21.503     3.3  39.253    3.47  60.633    3.21  83.473    2.46  85.763    1.26
  98.593    1.39 108.093    1.17 109.973     .97 123.083      .1 131.583     .36
 133.083    1.36 133.743    1.65 149.173    1.89 156.963    3.13
#Mann= 3 , 0 , 0
  21.503     .04       0  83.473    .033       0 133.743     .03       0
Levee=-1,39.15,3.46,0,,,Levee 20,
Bank Sta=83.473,133.743
XS Rating Curve= 0 ,0
Exp/Cntr=0.3,0.1

Type RM Length L Ch R = 1 ,291     ,200,200,200
BEGIN DESCRIPTION:
Assumed section
END DESCRIPTION:
#Sta/Elev= 7
       0       3     200      .5     205       0     225    -.25     245       0
     250      .5     450       3
#Mann= 3 , 0 , 0
       0     .04       0     200    .033       0     250     .04       0
Bank Sta=200,250
XS Rating Curve= 0 ,0
Exp/Cntr=0.3,0.1

Type RM Length L Ch R = 1 ,91      ,91,91,91
BEGIN DESCRIPTION:
Assumed section
END DESCRIPTION:
#Sta/Elev= 7
       0       3     100      -5     205     -25     225     -35     245     -25
     350      -5     450       3
#Mann= 3 , 0 , 0
       0     .04       0     100    .033       0     350     .04       0
Bank Sta=100,350
XS Rating Curve= 0 ,0
Exp/Cntr=0.3,0.1

Type RM Length L Ch R = 1 ,0       ,0,0,0
BEGIN DESCRIPTION:
Assumed section
END DESCRIPTION:
#Sta/Elev= 7
       0       3     100     -10     205     -50     225     -70     245     -50
     350     -10     450       3
#Mann= 3 , 0 , 0
       0     .04       0     100    .033       0     350     .04       0
Bank Sta=100,350
XS Rating Curve= 0 ,0
Exp/Cntr=0.3,0.1

Storage Area=Noel's Pond     ,302249.2882657,5379863.9817382
Storage Area Surface Line= 6
301308.5563045185380145.89106011
301485.8209365635380340.88242513
302106.6851903295380351.06052765
303155.0297499675379552.07947977
 302386.583009655379338.33932683
 301307.704142455380142.40942597
Storage Area Type= 1
Storage Area Vol Elev= 4
   21.15       0      22  913.75      24 3393.75      25 4773.75

Chan Stop Cuts=-1
Use User Specified Reach Order=0

--- Blanche_Brook.g03 (geometry) ---

Geom Title=Structure Blockage Analysis
Program Version=4.00

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
River Reach=Blanche Brook   ,US of Confluence