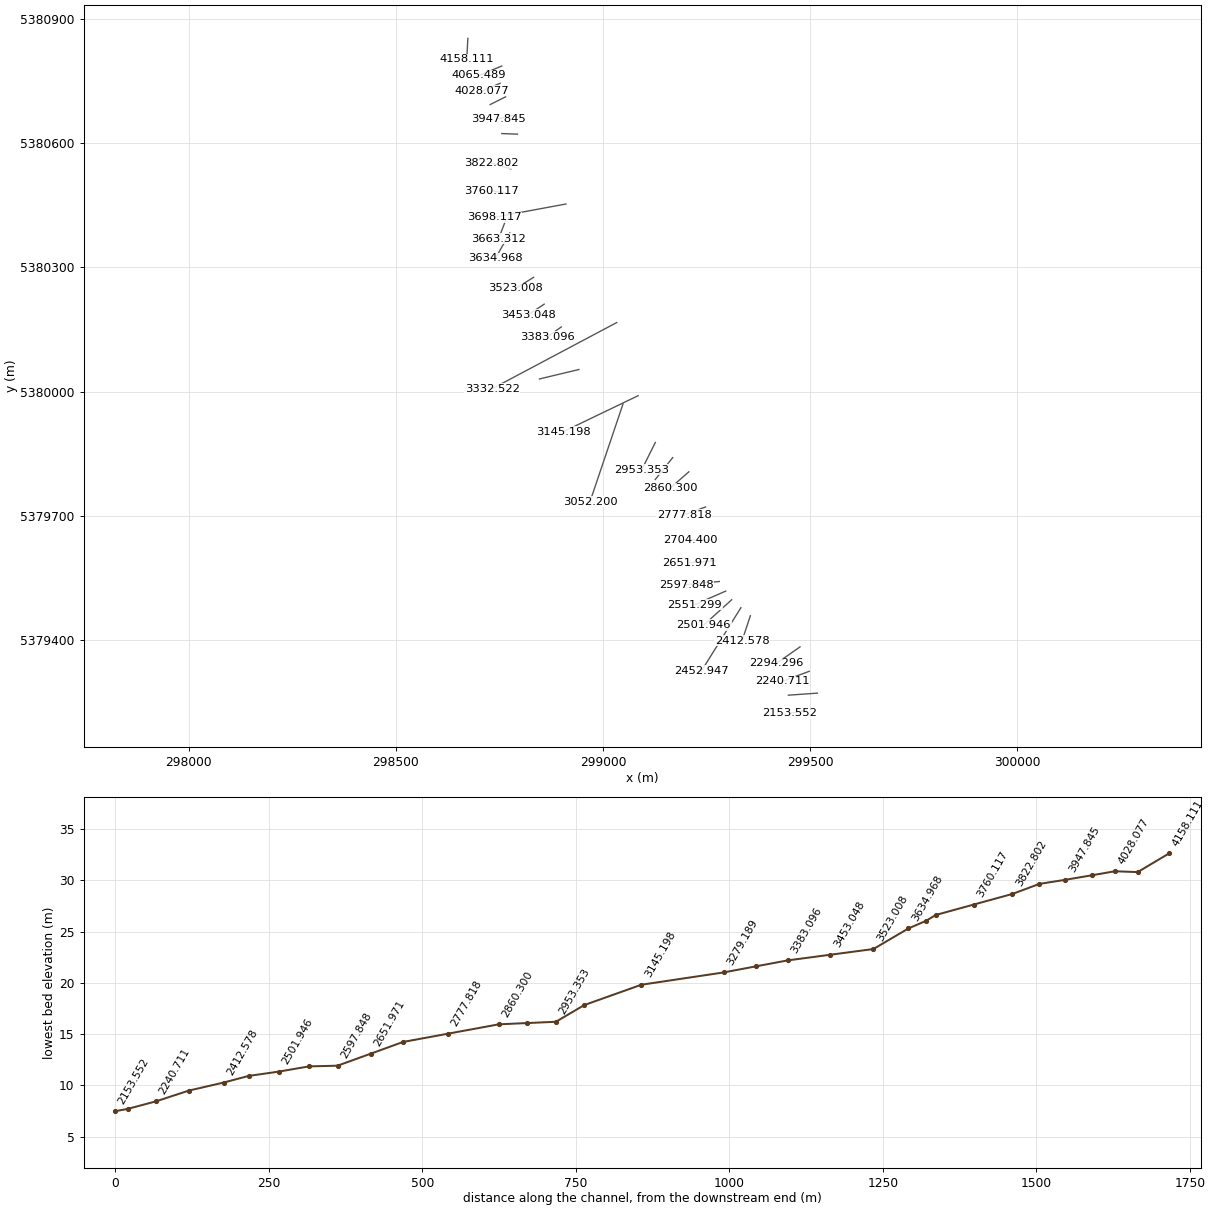
HEC-RAS study Blanche_Brook.prj: Stephenville Model

--- Blanche_Brook.g03 (geometry) --- (continued)

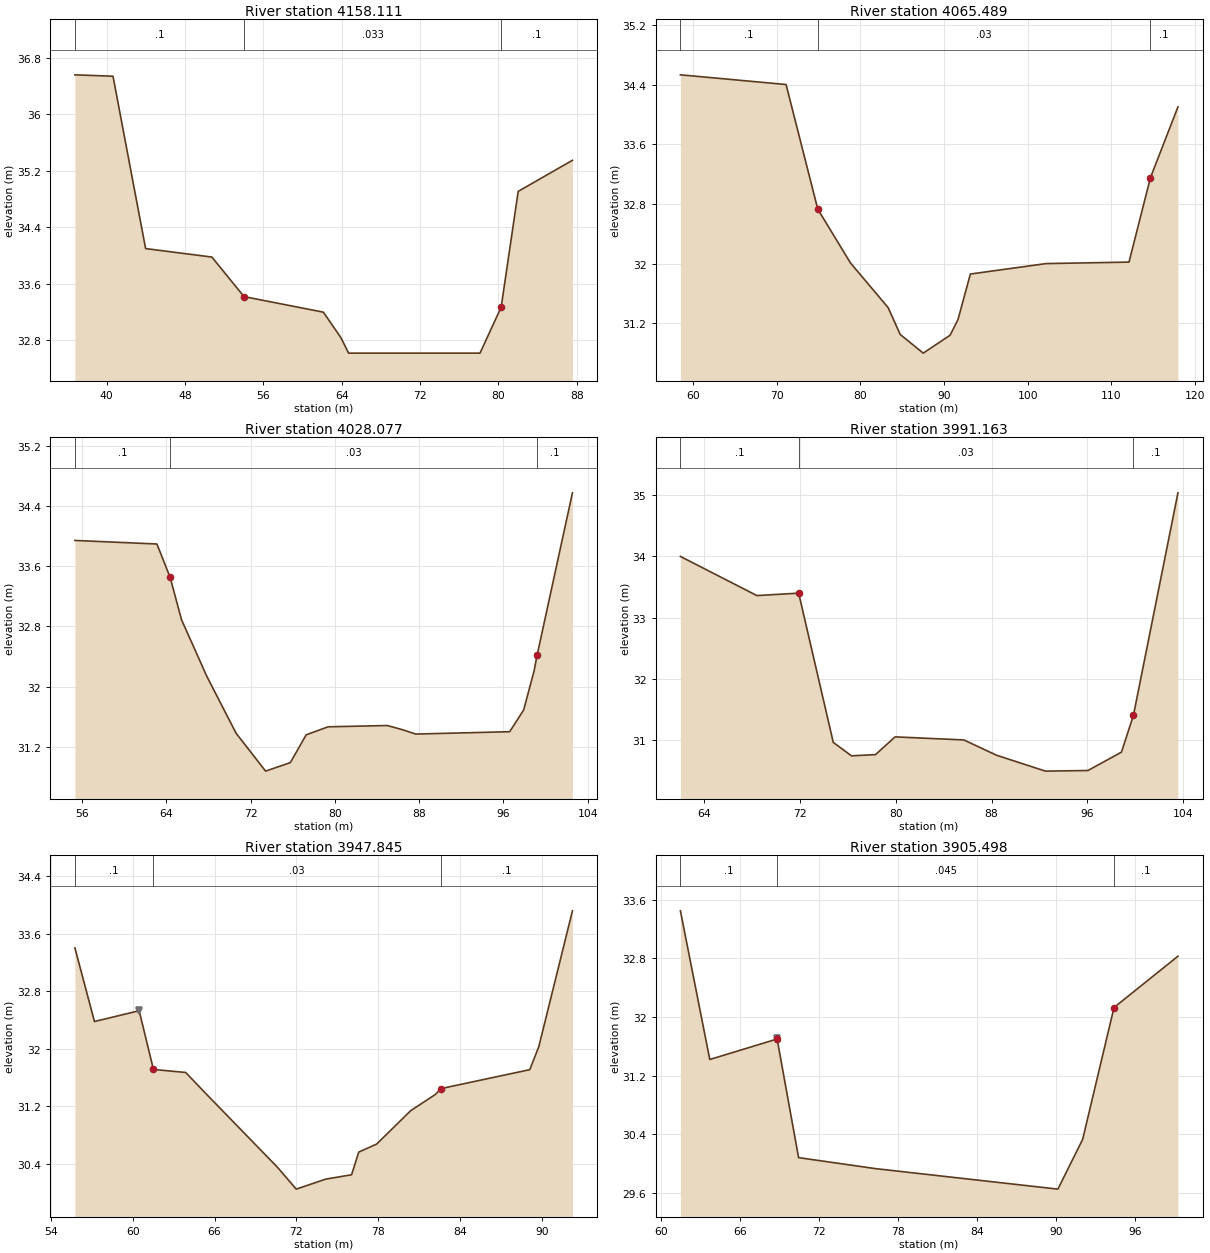
Type RM Length L Ch R = 1 ,4158.111,56.608,50.986,38.986
BEGIN DESCRIPTION:
2008 Survey Section
END DESCRIPTION:
Node Name=BB39
XS GIS Cut Line= 2
298673.7152083715380853.34084345 298671.076662985380802.59958592
#Sta/Elev= 12
  36.751   36.56  40.641   36.54  43.971    34.1  50.741   33.98  54.021   33.42
  62.121    33.2  63.911   32.84  64.701   32.62  78.121   32.62  80.281   33.27
  82.021   34.91  87.561   35.35
#Mann= 3 , 0 , 0
  36.751      .1       0  54.021    .033       0  80.281      .1       0
Bank Sta=54.021,80.281
XS Rating Curve= 0 ,0
Exp/Cntr=0.3,0.1

Type RM Length L Ch R = 1 ,4065.489,38.598,37.412,37.41
BEGIN DESCRIPTION:
2008 Survey Section
END DESCRIPTION:
Node Name=BB38
XS GIS Cut Line= 2
298755.4837313625380786.51361197 298700.593541525380763.62888025
#Sta/Elev= 14
  58.474   34.53  71.104    34.4  74.894   32.73  78.794   32.01  83.304   31.41
   84.75   31.05    87.5    30.8   90.71   31.04  91.654   31.25  93.134   31.86
 102.184      32 112.094   32.02 114.654   33.15 117.944    34.1
#Mann= 3 , 0 , 0
  58.474      .1       0  74.894     .03       0 114.654      .1       0
Bank Sta=74.894,114.654
XS Rating Curve= 0 ,0
Exp/Cntr=0.3,0.1

Type RM Length L Ch R = 1 ,4028.077,36.768,36.914,37.219
BEGIN DESCRIPTION:
Interpolated Section
END DESCRIPTION:
Node Name=BB37a
XS GIS Cut Line= 2
298751.6701636045380744.77469999298708.0944586265380726.52001277
#Sta/Elev= 19
  55.314  33.941  63.101  33.894  64.351  33.453  65.438  32.889  67.842  32.137
  70.622  31.382  71.835  31.165   73.42   30.88   75.77  30.993  77.278  31.362
  79.355  31.468  84.991  31.485    86.5  31.426  87.672  31.372  96.598  31.403
  97.924  31.691  98.906  32.204  99.206   32.42 102.559  34.573
#Mann= 3 , 0 , 0
  55.314      .1       0  64.351     .03       0  99.206      .1       0
Bank Sta=64.351,99.206
XS Rating Curve= 0 ,0
Exp/Cntr=0.3,0.1

Type RM Length L Ch R = 1 ,3991.163,44.678,43.318,41.969
BEGIN DESCRIPTION:
2008 Survey Section
END DESCRIPTION:
Node Name=BB37
XS GIS Cut Line= 3
298764.9254170855380712.09629316298759.2073460725380709.23725765
298727.7416325775380693.50440091
#Sta/Elev= 14
      62      34  68.393   33.36  71.883    33.4  74.773   30.96  76.293   30.74
    78.3   30.76  79.943   31.05  85.683      31  88.413   30.75    92.5   30.49
   96.05    30.5  98.853    30.8  99.853    31.4 103.573   35.04
#Mann= 3 , 0 , 0
      62      .1       0  71.883     .03       0  99.853      .1       0
Bank Sta=71.883,99.853
XS Rating Curve= 0 ,0
Exp/Cntr=0.3,0.1

Type RM Length L Ch R = 1 ,3947.845,45.414,42.347,39.914
BEGIN DESCRIPTION:
Interpolated Section
END DESCRIPTION:
Node Name=BB36a
XS GIS Cut Line= 2
298783.5906972145380667.79544014298748.1588359315380659.09287772
#Sta/Elev= 18
  55.762  33.406  57.194  32.382  60.474  32.532  61.521  31.715  63.888  31.673
  65.264  31.399  70.616  30.354   71.99   30.05  74.155  30.189   76.05   30.25
  76.576  30.565  77.889  30.677  80.383  31.141  82.193  31.367  82.615  31.449
  89.117  31.712   89.78  32.032  92.247  33.922
#Mann= 3 , 0 , 0
  55.762      .1       0  61.521     .03       0  82.615      .1       0
Levee=-1,60.47,32.54,0,,,,
Bank Sta=61.521,82.615
XS Rating Curve= 0 ,0
Exp/Cntr=0.3,0.1

Type RM Length L Ch R = 1 ,3905.498,44.577,44.11,42.837
BEGIN DESCRIPTION:
2008 Survey Section
END DESCRIPTION:
Node Name=BB36
XS GIS Cut Line= 2
298793.5339148415380621.95262812298755.8004084925380623.36763461
#Sta/Elev= 9
  61.485   33.45  63.715   31.42  68.825    31.7  70.455   30.08  76.285   29.93
  90.135   29.65  92.015   30.33  94.395   32.13  99.245   32.83
#Mann= 3 , 0 , 0
  61.485      .1       0  68.825    .045       0  94.395      .1       0
Levee=-1,68.84,31.71,0,,,,
Bank Sta=68.825,94.395
XS Rating Curve= 0 ,0
Exp/Cntr=0.3,0.1

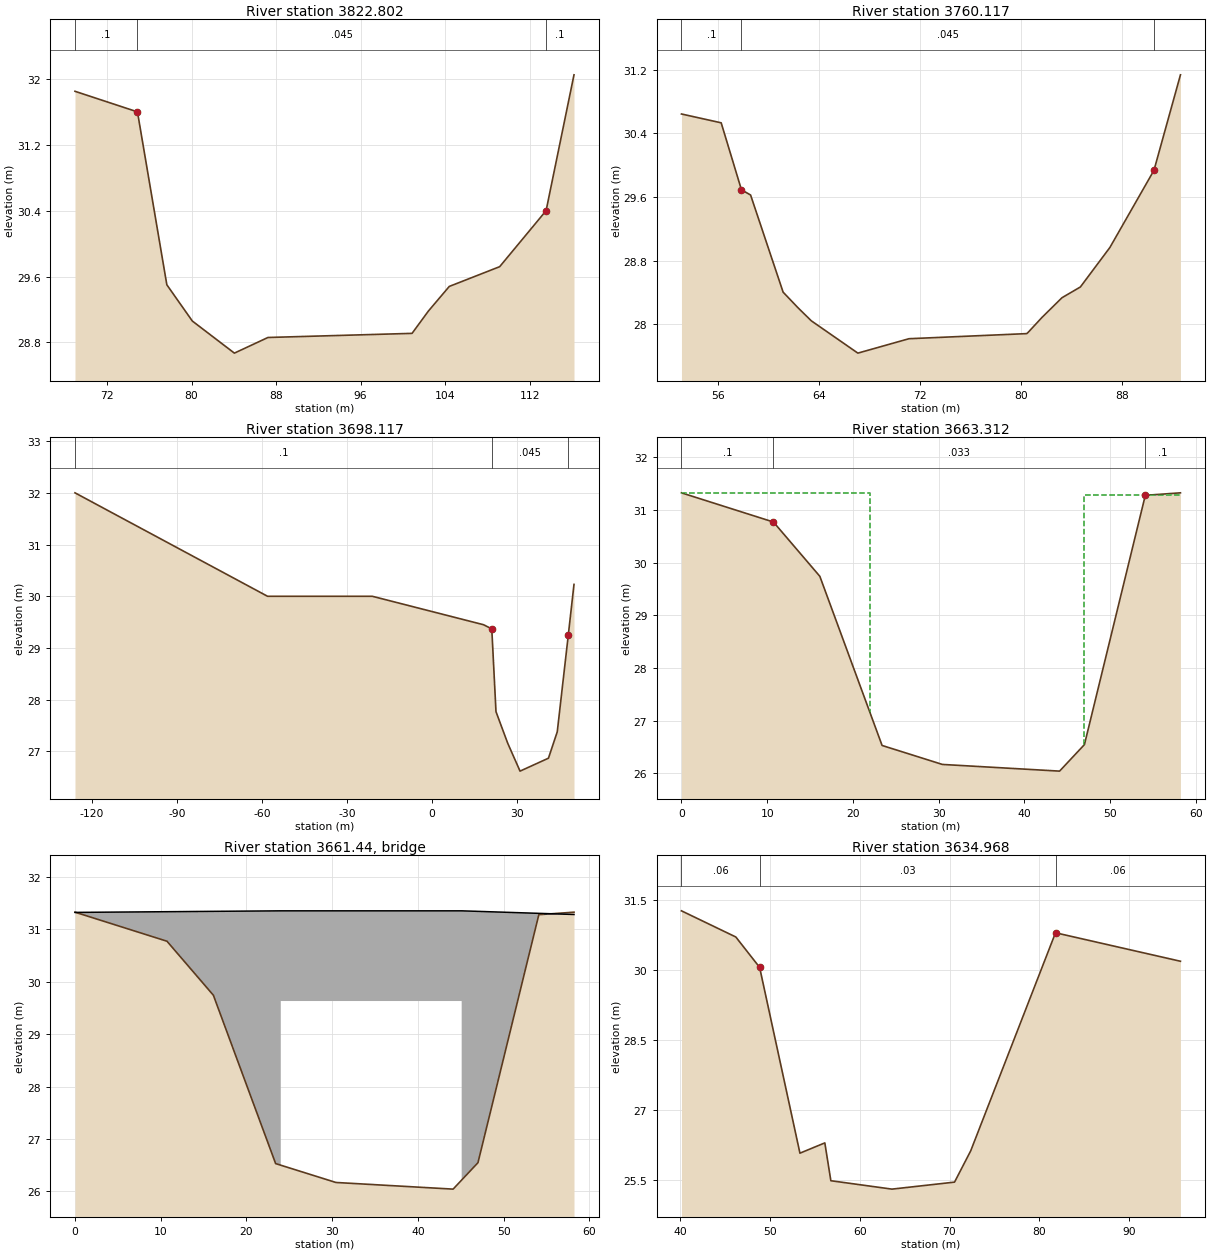
Type RM Length L Ch R = 1 ,3822.802,61.91,62.684,63.038
BEGIN DESCRIPTION:
2008 Survey Section
END DESCRIPTION:
Node Name=BB35
XS GIS Cut Line= 2
298777.8696352115380538.01749845298731.3351375525380551.67608821
#Sta/Elev= 12
  68.973   31.85  74.883    31.6  77.663    29.5  80.073   29.06  84.053   28.67
   87.23   28.86 100.863   28.91 102.403   29.18 104.383   29.48 109.153   29.72
 113.543    30.4 116.183   32.05
#Mann= 3 , 0 , 0
  68.973      .1       0  74.883    .045       0 113.543      .1       0
Bank Sta=74.883,113.543
XS Rating Curve= 0 ,0
Exp/Cntr=0.3,0.1

Type RM Length L Ch R = 1 ,3760.117,58.614,62,62.497
BEGIN DESCRIPTION:
Interpolated Section
END DESCRIPTION:
Node Name=BB34a
XS GIS Cut Line= 2
298769.9586677435380478.33507839298731.0398285855380485.25398313
#Sta/Elev= 17
  53.088  30.643  56.235  30.532   57.84  29.691  58.565  29.625  61.141  28.405
  62.332  28.207  63.374  28.045  67.062  27.639   71.11   27.82  80.432  27.884
  80.517  27.894  81.657  28.089  83.232  28.335  84.689   28.47  87.026  28.966
  90.517  29.935  92.617  31.135
#Mann= 3 , 0 , 0
  53.088      .1       0   57.84    .045       0  90.517      .1       0
Bank Sta=57.84,90.517
XS Rating Curve= 0 ,0
Exp/Cntr=0.3,0.1

Type RM Length L Ch R = 1 ,3698.117,12.698,16.184,17.773
BEGIN DESCRIPTION:
2008 Survey Section
END DESCRIPTION:
Node Name=BB34
XS GIS Cut Line= 3
298910.5745372965380453.29789571298768.7181217225380426.94205896
298737.3256638325380421.10958045
#Sta/Elev= 12
    -126      32     -58      30     -21      30  18.284   29.45  21.184   29.37
  22.664   27.77  26.804   27.16  31.164   26.62  41.194   26.87  44.304   27.38
    48.2   29.25  50.214   30.23
#Mann= 3 , 0 , 0
    -126      .1       0  21.184    .045       0    48.2      .1       0
Bank Sta=21.184,48.2
XS Rating Curve= 0 ,0
Exp/Cntr=0.3,0.1

Type RM Length L Ch R = 1 ,3663.312,28.407,28.345,23.772
BEGIN DESCRIPTION:
2008 Survey Section
END DESCRIPTION:
Node Name=BB33
XS GIS Cut Line= 3
298773.493453953 5380419.3569334298765.3284293535380414.64798742
298747.8633755695380369.10757782
#Sta/Elev= 9
       0 31.3243   10.73   30.77   16.14   29.74    23.4   26.53   30.43   26.17
    44.1  26.043      47 26.5466    54.131.27667    58.2 31.3243
#Mann= 3 , 0 , 0
       0      .1       0   10.73    .033       0    54.1      .1       0
#XS Ineff= 2 , 0
       0      22   31.32      47       0   31.29
Permanent Ineff=
       F       F
Bank Sta=10.73,54.1
XS Rating Curve= 0 ,0
Exp/Cntr=0.5,0.3

Type RM Length L Ch R = 3 ,3661.44 ,,,
BEGIN DESCRIPTION:
Hansen Highway Bridge
END DESCRIPTION:
Bridge Culvert--1,0,-1,-1, 0
Deck Dist Width WeirC Skew NumUp NumDn MinLoCord MaxHiCord MaxSubmerge Is_Ogee
1.88,19.66,1.6,0, 6, 6, , , 0.98, 0, 1,1,,
       0      24      24    45.1    45.1    58.2
   31.32   31.35   31.35   31.35   31.35   31.28
       0       0   29.63   29.63       0       0
   40.16      53      53    74.1    74.1    81.8
   31.27   31.35   31.35   31.35   31.35    30.8
       0       0   29.63    29.6       0       0
BR Coef=-1 , 0 , 0 ,, 0 ,,,0.8,-1,,0,
WSPro=,,,, 1 ,,,, 0 ,,,, 0 ,,,,-1 ,-1 ,-1 , 0 , 0 , 0 , 0 , 0
BC Design=,, 0 ,, 0 ,,,,,,
BC Use User HTab Curves=0
BC User HTab FreeFlow(D)= 0

Type RM Length L Ch R = 1 ,3634.968,58.975,57.091,54.669
BEGIN DESCRIPTION:
2008 Survey Section
END DESCRIPTION:
Node Name=BB32
XS GIS Cut Line= 2
298775.0955149675380383.50380243298740.4601418835380322.35740304
#Sta/Elev= 11
  40.159   31.27  46.209   30.71  48.859   30.06  53.349   26.08  56.119    26.3
   56.79   25.49   63.59   25.31  70.559   25.46  72.359   26.13  81.799    30.8
  95.709   30.19
#Mann= 3 , 0 , 0
  40.159     .06       0  48.859     .03       0  81.799     .06       0
Bank Sta=48.859,81.799
XS Rating Curve= 0 ,0
Exp/Cntr=0.5,0.3

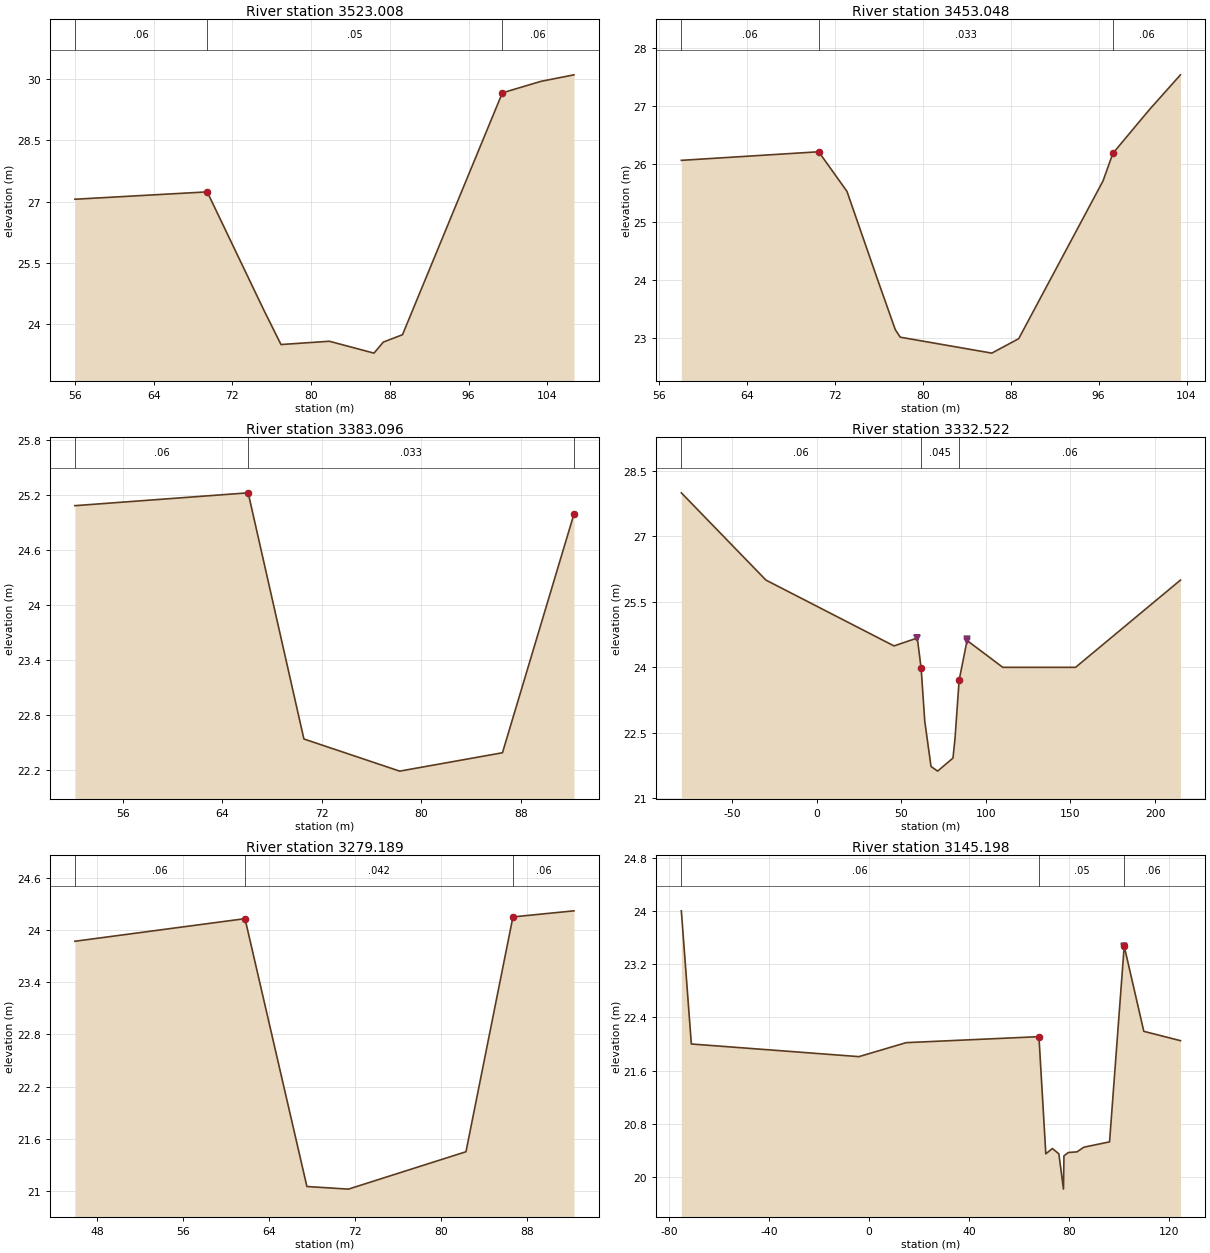
Type RM Length L Ch R = 1 ,3523.008,69.291,69.959,70.085
BEGIN DESCRIPTION:
2008 Survey Section
END DESCRIPTION:
Node Name=BB31
XS GIS Cut Line= 3
298832.3941906645380276.10690404298832.3941906645380276.10690404
298789.2477190425380249.42421764
#Sta/Elev= 11
  55.988   27.06  69.438   27.24  75.198   24.35  76.938   23.51   81.85   23.59
  86.388    23.3   87.34   23.57  89.288   23.75  99.438   29.66 103.348   29.94
 106.718    30.1
#Mann= 3 , 0 , 0
  55.988     .06       0  69.438     .05       0  99.438     .06       0
Bank Sta=69.438,99.438
XS Rating Curve= 0 ,0
Exp/Cntr=0.3,0.1

Type RM Length L Ch R = 1 ,3453.048,69.452,69.952,70.023
BEGIN DESCRIPTION:
Interpolated Section
END DESCRIPTION:
Node Name=BB30a
XS GIS Cut Line= 2
298857.952628618 5380211.4348508298820.2367358365380186.11870359
#Sta/Elev= 12
  58.023   26.07  70.524  26.218  73.097  25.535  75.877  24.017  77.495   23.15
  77.945   23.02  86.278  22.745  88.727  22.994  96.401  25.715  97.299  26.191
 100.602   26.94 103.448  27.545
#Mann= 3 , 0 , 0
  58.023     .06       0  70.524    .033       0  97.299     .06       0
Bank Sta=70.524,97.299
XS Rating Curve= 0 ,0
Exp/Cntr=0.3,0.1

Type RM Length L Ch R = 1 ,3383.096,51.839,50.574,49.975
BEGIN DESCRIPTION:
2008 Survey Section
END DESCRIPTION:
Node Name=BB30
XS GIS Cut Line= 3
298899.4708048295380156.47007593 298874.948404555380138.98051497
298866.806920213 5380133.1739469
#Sta/Elev= 6
   52.14   25.08   66.07   25.22   70.55   22.54   78.25   22.19   86.51   22.39
   92.26   24.99
#Mann= 3 , 0 , 0
   52.14     .06       0   66.07    .033       0   92.26     .06       0
Bank Sta=66.07,92.26
XS Rating Curve= 0 ,0
Exp/Cntr=0.3,0.1

Type RM Length L Ch R = 1 ,3332.522,55.876,53.334,52.416
BEGIN DESCRIPTION:
Interpolated Section
END DESCRIPTION:
Node Name=BB29a
XS GIS Cut Line= 5
299033.1001833255380166.93724838 298922.090959655380107.98019658
298857.4339517015380073.64082873 298844.186395325380066.60504519
298732.8097724545380007.45286744
#Sta/Elev= 15
     -80      28     -30      26  45.694  24.491  59.453  24.672  61.735   23.98
  63.878  22.764  67.572  21.728  71.483  21.621  80.556  21.921  81.746  22.364
   84.18  23.701   88.89  24.615     110      24     153      24     215      26
#Mann= 3 , 0 , 0
     -80     .06       0  61.735    .045       0   84.18     .06       0
Levee=-1,59.47,24.67,-1,88.95,24.64,,
Bank Sta=61.735,84.18
XS Rating Curve= 0 ,0
Exp/Cntr=0.3,0.1

Type RM Length L Ch R = 1 ,3279.189,132.549,133.991,134.931
BEGIN DESCRIPTION:
2008 Survey Section
END DESCRIPTION:
Node Name=BB29
XS GIS Cut Line= 2
298941.8571116835380053.59592442298846.664155566 5380030.7989058
#Sta/Elev= 7
  45.937   23.87  61.767   24.13  67.527   21.05  71.387   21.02  82.327   21.45
  86.697   24.15  92.377   24.22
#Mann= 3 , 0 , 0
  45.937     .06       0  61.767    .042       0  86.697     .06       0
Bank Sta=61.767,86.697
XS Rating Curve= 0 ,0
Exp/Cntr=0.3,0.1

Type RM Length L Ch R = 1 ,3145.198,86.734,92.999,98.011
BEGIN DESCRIPTION:
Interpolated Section
END DESCRIPTION:
Node Name=BB28
XS GIS Cut Line= 6
299084.9688441235379990.36292937298950.048134001  5379925.460582
298943.706669001  5379922.365416298938.788753001  5379920.047918
   298927.120776  5379914.339685298905.1691484545379903.80580976
#Sta/Elev= 17
     -75      24     -71      22      -4   21.81   14.88   22.02   67.97   22.11
   70.72   20.35   73.33   20.43   75.94   20.35   77.78   19.82   77.97   20.32
   79.71   20.37   83.21   20.38   85.94   20.45    96.2   20.53  102.06   23.47
   109.9   22.19  124.55   22.05
#Mann= 3 , 0 , 0
     -75     .06       0   67.97     .05       0  102.06     .06       0
Levee=0,,,-1,102.08,23.46,,
Bank Sta=67.97,102.06
XS Rating Curve= 0 ,0
Exp/Cntr=0.3,0.1

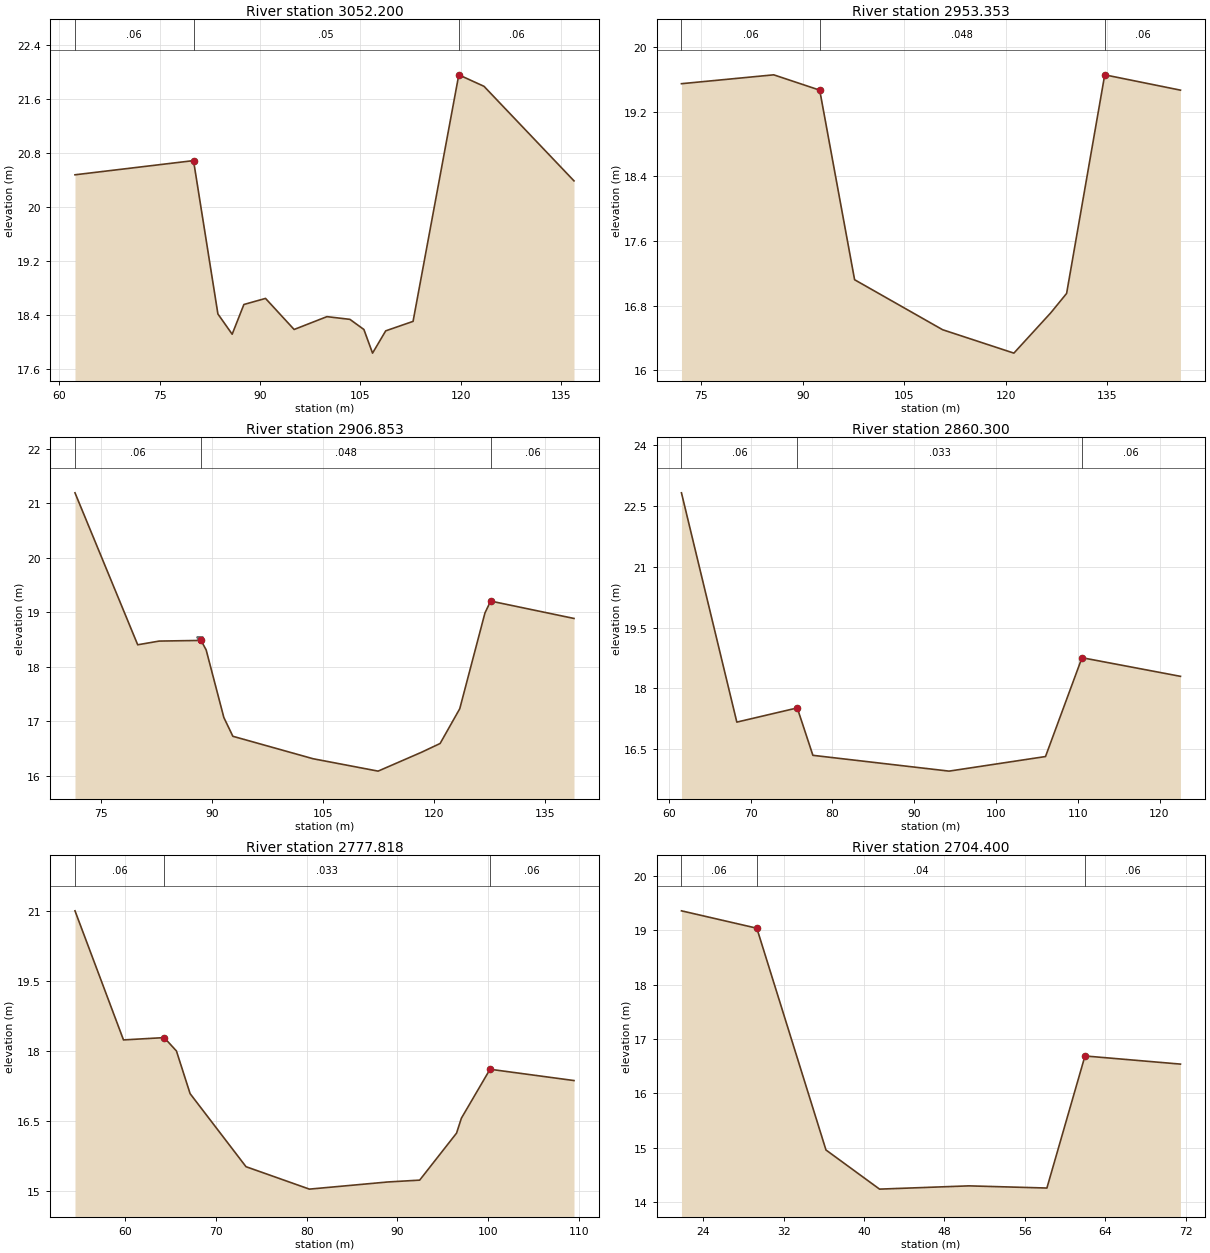
Type RM Length L Ch R = 1 ,3052.200,46.777,46.316,45.575
BEGIN DESCRIPTION:
2008 Survey Section
END DESCRIPTION:
Node Name=BB27
XS GIS Cut Line= 2
299048.4392323935379970.52160635298968.7777899655379734.72373676
#Sta/Elev= 16
  62.372   20.48  80.072   20.69  83.712   18.42  85.842   18.12  87.592   18.56
  90.822   18.65  95.092   18.19  99.992   18.38 103.422   18.34  105.51   18.19
 106.802   17.84  108.77   18.17 112.852   18.31 119.682   21.96 123.442   21.79
 136.882   20.39
#Mann= 3 , 0 , 0
  62.372     .06       0  80.072     .05       0 119.682     .06       0
Bank Sta=80.072,119.682
XS Rating Curve= 0 ,0
Exp/Cntr=0.3,0.1

Type RM Length L Ch R = 1 ,2953.353,50.421,46.5,44.883
BEGIN DESCRIPTION:
2008 Survey Section
END DESCRIPTION:
Node Name=BB26
XS GIS Cut Line= 2
299126.4199556795379877.36670024 299093.459059855379811.32461335
#Sta/Elev= 10
  72.061   19.55  85.711   19.66  92.511   19.47  97.671   17.12 110.691    16.5
 121.231   16.21 126.691   16.71 129.031   16.95 134.671   19.66 145.871   19.47
#Mann= 3 , 0 , 0
  72.061     .06       0  92.511    .048       0 134.671     .06       0
Bank Sta=92.511,134.671
XS Rating Curve= 0 ,0
Exp/Cntr=0.3,0.1

Type RM Length L Ch R = 1 ,2906.853,48.345,46.553,44.606
BEGIN DESCRIPTION:
Interpolated Section
END DESCRIPTION:
Node Name=BB25a
XS GIS Cut Line= 3
299168.4107590725379840.79985326299136.5495561975379800.87889946
299126.358653183 5379788.1100605
#Sta/Elev= 15
  71.485  21.189  79.958  18.402  82.853   18.47  88.516  18.482  89.207  18.307
  91.597  17.068  92.814  16.724 103.657  16.312 112.435  16.085 118.299  16.431
 120.812  16.592 123.464  17.229  126.87  18.986 127.636  19.204 138.899  18.885
#Mann= 3 , 0 , 0
  71.485     .06       0  88.516    .048       0 127.636     .06       0
Levee=-1,88.44,18.49,0,,,,
Bank Sta=88.516,127.636
XS Rating Curve= 0 ,0
Exp/Cntr=0.3,0.1

Type RM Length L Ch R = 1 ,2860.300,84.652,82.482,80.116
BEGIN DESCRIPTION:
2008 Survey Section
END DESCRIPTION:
Node Name=BB25
XS GIS Cut Line= 2
299207.4483746195379806.59041551299161.5662235355379766.37791238
#Sta/Elev= 8
  61.552   22.83  68.322   17.17  75.712   17.52  77.622   16.35  94.272   15.96
 106.062   16.32 110.522   18.76 122.562    18.3
#Mann= 3 , 0 , 0
  61.552     .06       0  75.712    .033       0 110.522     .06       0
Bank Sta=75.712,110.522
XS Rating Curve= 0 ,0
Exp/Cntr=0.3,0.1

Type RM Length L Ch R = 1 ,2777.818,74.613,73.418,70.108
BEGIN DESCRIPTION:
Interpolated Section
END DESCRIPTION:
Node Name=BB24a
XS GIS Cut Line= 2
299247.6661660225379721.71371389299196.204875676 5379702.3028763
#Sta/Elev= 13
  54.467  20.994  59.813  18.237  64.298  18.286  65.648  18.001  67.156  17.089
  73.317  15.529  80.304   15.05  88.963  15.203  92.458  15.242  96.522  16.246
  97.055  16.565 100.213   17.61 109.467  17.369
#Mann= 3 , 0 , 0
  54.467     .06       0  64.298    .033       0 100.213     .06       0
Bank Sta=64.298,100.213
XS Rating Curve= 0 ,0
Exp/Cntr=0.3,0.1

Type RM Length L Ch R = 1 ,2704.400,52.02,52.429,52.896
BEGIN DESCRIPTION:
2008 Survey Section
END DESCRIPTION:
Node Name=BB24
XS GIS Cut Line= 2
299259.6692445625379642.28641383299210.0312172815379641.18334655
#Sta/Elev= 8
  21.842   19.36  29.342   19.04  36.222   14.96  41.552   14.24  50.442    14.3
  58.202   14.26  61.992   16.69  71.492   16.54
#Mann= 3 , 0 , 0
  21.842     .06       0  29.342     .04       0  61.992     .06       0
Bank Sta=29.342,61.992
XS Rating Curve= 0 ,0
Exp/Cntr=0.3,0.1

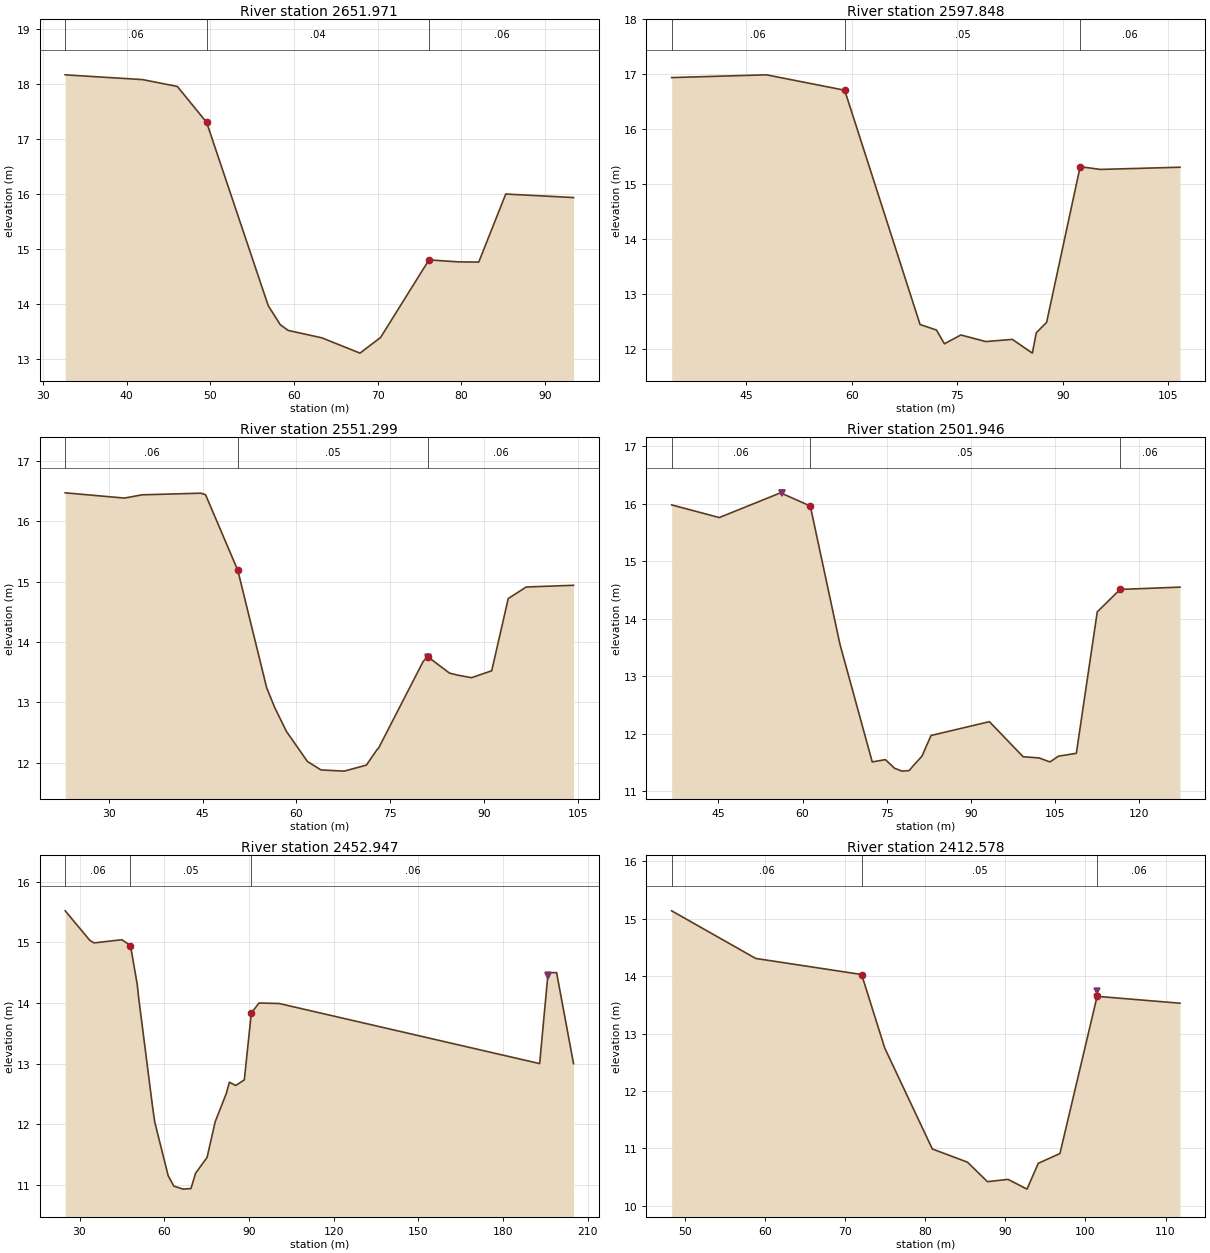
Type RM Length L Ch R = 1 ,2651.971,52.676,54.123,52.466
BEGIN DESCRIPTION:
Interpolated Section
END DESCRIPTION:
Node Name=BB23a
XS GIS Cut Line= 2
299270.1266359735379592.20213984299209.549906461 5379587.0466735
#Sta/Elev= 16
  32.642  18.169  41.906  18.082  46.057  17.957  49.555  17.304  56.922  13.968
  58.363  13.621    59.3  13.517  63.347  13.381  67.897  13.103  70.366  13.389
   75.48  14.637  76.167    14.8   79.67  14.764    82.1   14.76  85.333  15.999
  93.438  15.935
#Mann= 3 , 0 , 0
  32.642     .06       0  49.555     .04       0  76.167     .06       0
Bank Sta=49.555,76.167
XS Rating Curve= 0 ,0
Exp/Cntr=0.3,0.1

Type RM Length L Ch R = 1 ,2597.848,44.068,46.55,47.373
BEGIN DESCRIPTION:
2008 Survey Section
END DESCRIPTION:
Node Name=BB23
XS GIS Cut Line= 2
299280.9740230735379541.65443018299201.2944488485379534.09224837
#Sta/Elev= 15
  34.371   16.94  47.851   16.99  58.981   16.71  69.701   12.45   72.03   12.35
  73.161    12.1   75.51   12.26  79.051   12.14   82.83   12.18  85.671   11.93
   86.23    12.3  87.701   12.49  92.471   15.32  95.351   15.27 106.671   15.31
#Mann= 3 , 0 , 0
  34.371     .06       0  58.981     .05       0  92.471     .06       0
Bank Sta=58.981,92.471
XS Rating Curve= 0 ,0
Exp/Cntr=0.3,0.1

Type RM Length L Ch R = 1 ,2551.299,47.165,49.353,50.132
BEGIN DESCRIPTION:
Interpolated Section
END DESCRIPTION:
Node Name=BB22a
XS GIS Cut Line= 2
299296.470358839 5379518.4881891299222.0654506495379485.91949263
#Sta/Elev= 24
  23.057  16.474  32.526  16.387  35.339  16.441  44.727  16.468  45.481  16.443
  50.638  15.188  55.248  13.242  56.527  12.916  58.401  12.519   61.76   12.02
   63.93   11.88   67.64   11.86   71.18   11.96  72.882  12.216  73.132  12.242
  80.241  13.676  80.964  13.758  84.448  13.486  85.693  13.453  87.983  13.409
  91.206  13.524  93.844  14.721  96.721  14.913 104.278  14.941
#Mann= 3 , 0 , 0
  23.057     .06       0  50.638     .05       0  80.964     .06       0
Levee=0,,,-1,81.06,13.74,,
Bank Sta=50.638,80.964
XS Rating Curve= 0 ,0
Exp/Cntr=0.3,0.1

Type RM Length L Ch R = 1 ,2501.946,48.982,48.999,49.706
BEGIN DESCRIPTION:
2008 Survey Section
END DESCRIPTION:
Node Name=BB22
XS GIS Cut Line= 2
299310.7872617965379497.53829081299243.5765624745379436.66460028
#Sta/Elev= 22
   36.65   15.98   45.14   15.76   56.08   16.19   61.38   15.96   66.66   13.56
   72.43   11.51   74.78   11.55   76.41    11.4   77.72   11.35   79.02   11.36
   79.89   11.46    81.3   11.61   82.92   11.97   93.33   12.21   99.35    11.6
  102.17   11.58  104.13   11.51  105.65   11.61  108.84   11.66  112.57   14.12
  116.64   14.51  127.33   14.55
#Mann= 3 , 0 , 0
   36.65     .06       0   61.38     .05       0  116.64     .06       0
Levee=-1,56.26,16.18,0,,,,
Bank Sta=61.38,116.64
XS Rating Curve= 0 ,0
Exp/Cntr=0.3,0.1

Type RM Length L Ch R = 1 ,2452.947,38.657,40.37,41.644
BEGIN DESCRIPTION:
Interpolated Section
END DESCRIPTION:
Node Name=BB21a
XS GIS Cut Line= 3
299333.1367144015379478.42671757299293.0598857775379414.16559581
299237.8935478975379325.70922645
#Sta/Elev= 28
  24.924  15.519  33.683   15.03  35.156   14.99   44.97  15.042   48.04  14.947
  50.437  14.303  50.849  14.118  55.885  12.277  56.643  12.033   61.39   11.15
   63.39   10.98   66.65   10.93   69.46   10.94  71.067   11.19  75.158  11.453
  78.003  12.038  81.968  12.508  83.056  12.693  85.299  12.639  88.338  12.731
  90.823  13.833  93.535  13.999 100.658  13.991 192.907      13 195.907    14.5
 197.407    14.5 198.907    14.5 204.907      13
#Mann= 3 , 0 , 0
  24.924     .06       0   48.04     .05       0  90.823     .06       0
Levee=0,,,-1,195.8,14.46,,
Bank Sta=48.04,90.823
XS Rating Curve= 0 ,0
Exp/Cntr=0.3,0.1

Type RM Length L Ch R = 1 ,2412.578,58.965,57.021,55.229
BEGIN DESCRIPTION:
2008 Survey Section
END DESCRIPTION:
Node Name=BB21
XS GIS Cut Line= 2
299355.9413159975379458.91732217299335.9667231285379398.72542823
#Sta/Elev= 13
  48.389   15.14  58.879   14.31  72.089   14.03  74.969   12.75  80.909   10.99
   85.29   10.76  87.789   10.42   90.36   10.46  92.719   10.29   94.13   10.74
  96.829   10.91 101.469   13.65 111.809   13.53
#Mann= 3 , 0 , 0
  48.389     .06       0  72.089     .05       0 101.469     .06       0
Levee=0,,,-1,101.45,13.74,,
Bank Sta=72.089,101.469
XS Rating Curve= 0 ,0
Exp/Cntr=0.3,0.1

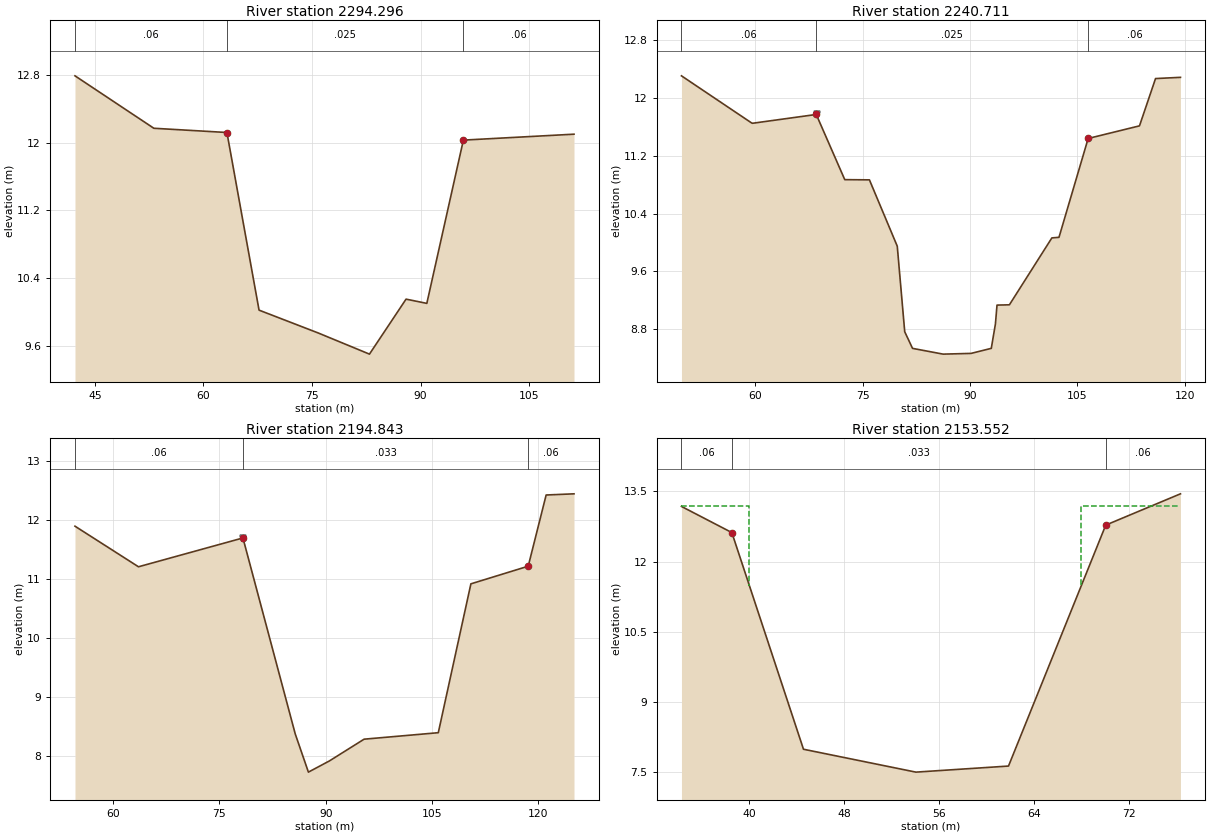
Type RM Length L Ch R = 1 ,2294.296,55.328,53.585,51.797
BEGIN DESCRIPTION:
2008 Survey Section
END DESCRIPTION:
Node Name=BB20
XS GIS Cut Line= 2
299475.8415631235379383.70187447299419.2919906735379344.21755761
#Sta/Elev= 10
  42.241   12.79  53.141   12.17  63.241   12.12  67.681   10.02  75.861    9.75
  82.941     9.5  88.001   10.15  90.871    10.1  95.921   12.03 111.211    12.1
#Mann= 3 , 0 , 0
  42.241     .06       0  63.241    .025       0  95.921     .06       0
Bank Sta=63.241,95.921
XS Rating Curve= 0 ,0
Exp/Cntr=0.3,0.1

Type RM Length L Ch R = 1 ,2240.711,47.275,45.868,43.163
BEGIN DESCRIPTION:
Interpolated Section
END DESCRIPTION:
Node Name=BB19a
XS GIS Cut Line= 2
299498.0517355245379324.77532383299432.6901053495379300.42003958
#Sta/Elev= 21
  49.661   12.31  59.442  11.658  59.595  11.652  68.504  11.774  72.488   10.87
  75.936  10.867  79.827   9.947   80.87    8.76   81.96    8.53   86.23    8.45
   90.14    8.46   92.97    8.53   93.55    8.87   93.77    9.13  95.502   9.134
 101.439  10.062 102.433   10.07 106.511  11.441 113.685  11.616 115.928  12.272
 119.413  12.289
#Mann= 3 , 0 , 0
  49.661     .06       0  68.504    .025       0 106.511     .06       0
Levee=-1,68.55,11.78,0,,,,
Bank Sta=68.504,106.511
XS Rating Curve= 0 ,0
Exp/Cntr=0.3,0.1

Type RM Length L Ch R = 1 ,2194.843,20.394,20.418,20.397
BEGIN DESCRIPTION:
2008 Survey Section
END DESCRIPTION:
Node Name=BB19
XS GIS Cut Line= 3
 299517.90990038 5379272.0366088299447.815151001  5379267.099045
  299447.66412915379267.08840682
#Sta/Elev= 12
  54.609    11.9  63.569   11.21  78.309    11.7  85.689    8.37  87.549    7.72
  90.509    7.91  95.409    8.28 105.879    8.39 110.479   10.92 118.569   11.22
 121.099   12.43 125.029   12.45
#Mann= 3 , 0 , 0
  54.609     .06       0  78.309    .033       0 118.569     .06       0
Levee=-1,78.33,11.7,0,,,,
Bank Sta=78.309,118.569
XS Rating Curve= 0 ,0
Exp/Cntr=0.3,0.1

Type RM Length L Ch R = 1 ,2153.552,17.891,18.471,17.928
BEGIN DESCRIPTION:
2008 Survey Section
END DESCRIPTION:
Node Name=BB18
XS GIS Cut Line= 2
299492.3074642465379231.14339987299450.9894636985379223.16975064
#Sta/Elev= 7
  34.266   13.18  38.516   12.62  44.556    7.98  54.036    7.49  61.846    7.62
  70.046   12.78  76.346   13.45
#Mann= 3 , 0 , 0
  34.266     .06       0  38.516    .033       0  70.046     .06       0
#XS Ineff= 2 , 0
       0      40   13.18      68       0   13.18
Permanent Ineff=
       F       F
Bank Sta=38.516,70.046
XS Rating Curve= 0 ,0
Exp/Cntr=0.5,0.3