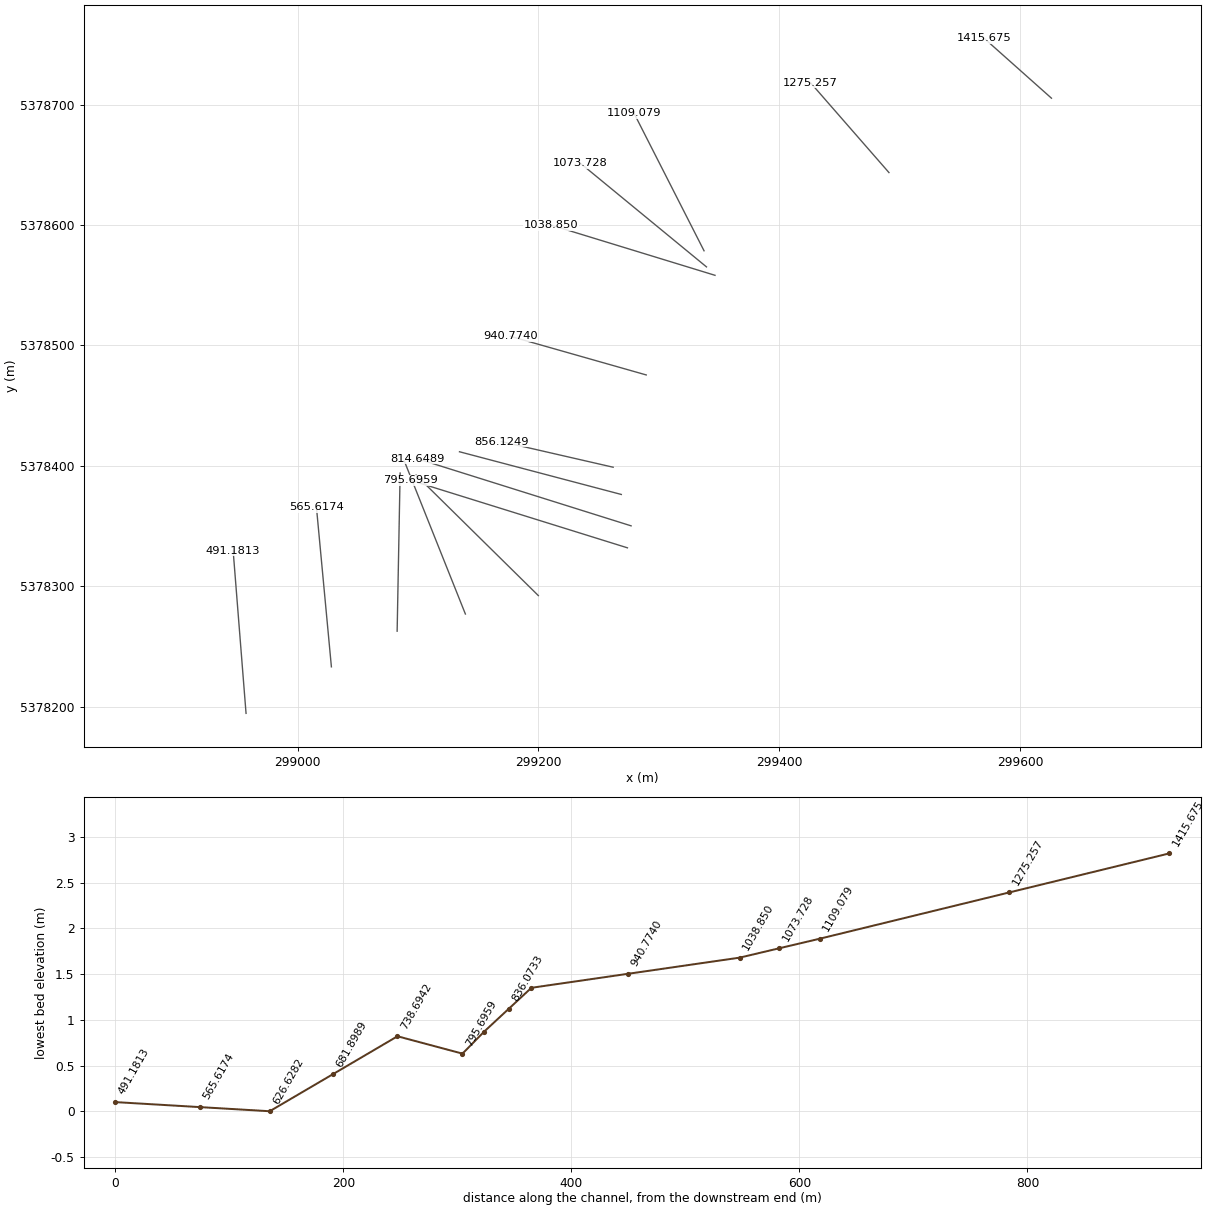
HEC-RAS study Blanche_Brook.prj: Stephenville Model

--- Blanche_Brook.g03 (geometry) --- (continued)

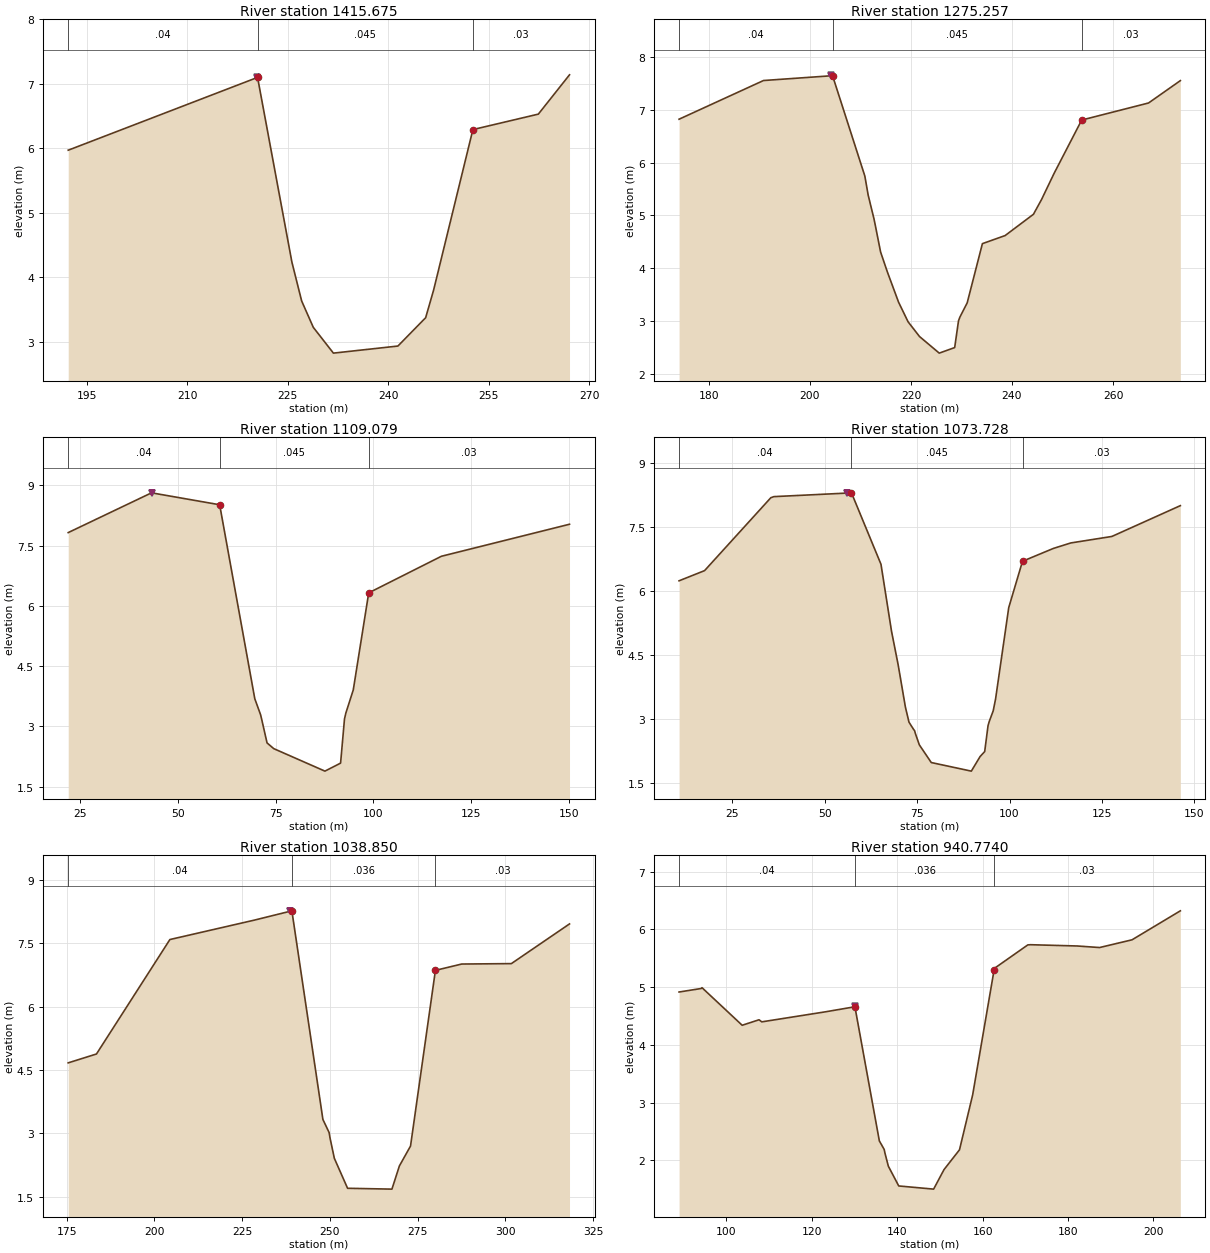
Type RM Length L Ch R = 1 ,1415.675,158.169,140.419,140.146
BEGIN DESCRIPTION:
2008 Survey Section
END DESCRIPTION:
Node Name=BB9
XS GIS Cut Line= 2
299626.2413460285378705.45654513  299570.34668825378755.19468992
#Sta/Elev= 12
 192.244    5.97 220.504     7.1 225.634    4.23 227.084    3.63 228.824    3.22
 231.824    2.82 241.454    2.93 245.594    3.37 246.784     3.8 252.644    6.29
 262.414    6.53 267.064    7.14
#Mann= 3 , 0 , 0
 192.244     .04       0 220.504    .045       0 252.644     .03       0
Levee=-1,220.36,7.1,0,,,,
Bank Sta=220.504,252.644
XS Rating Curve= 0 ,0
Exp/Cntr=0.3,0.1

Type RM Length L Ch R = 1 ,1275.257,168.064,166.177,163.118
BEGIN DESCRIPTION:
Interpolated Section
END DESCRIPTION:
Node Name=BB8a
XS GIS Cut Line= 2
299491.2122140655378643.65235928299425.9659520055378718.40909343
#Sta/Elev= 25
 174.101    6.82 190.812   7.552 204.481   7.644 210.871   5.745 211.531   5.384
 212.689   4.932 212.969     4.8 213.987   4.308  215.33    3.93 217.546   3.358
 219.432   2.986 221.696   2.707   225.6   2.393 228.654   2.498 229.417   3.005
 229.684   3.074 231.131   3.344 234.144   4.465 238.642   4.618 244.249   5.021
  245.86   5.302 248.325   5.793 253.797   6.804 267.029   7.127 273.326    7.55
#Mann= 3 , 0 , 0
 174.101     .04       0 204.481    .045       0 253.797     .03       0
Levee=-1,204.13,7.66,0,,,,
Bank Sta=204.481,253.797
XS Rating Curve= 0 ,0
Exp/Cntr=0.3,0.1

Type RM Length L Ch R = 1 ,1109.079,14.535,35.351,37.238
BEGIN DESCRIPTION:
2008 Survey Section
END DESCRIPTION:
Node Name=BB8
XS GIS Cut Line= 2
299337.5536422835378578.67410541299279.4347148645378692.83831755
#Sta/Elev= 16
      22  7.8266  43.288  8.8167  60.701  8.5196  69.681  3.6886  71.157  3.2922
  71.513  3.1466   72.81  2.5897  74.521   2.447  87.603   1.887  91.603   2.086
  92.603  3.1863  92.952  3.3331  94.847  3.9095  98.793  6.3259 117.365  7.2368
 150.107  8.0342
#Mann= 3 , 0 , 0
      22     .04       0  60.701    .045       0  98.793     .03       0
Levee=-1,43.46,8.8,0,,,,
Bank Sta=60.701,98.793
XS Rating Curve= 0 ,0
Exp/Cntr=0.3,0.1

Type RM Length L Ch R = 1 ,1073.728,15.434,34.878,36.514
BEGIN DESCRIPTION:
Interpolated Section
END DESCRIPTION:
Node Name=BB7a
XS GIS Cut Line= 2
299339.5825045725378565.28433151299234.883828444 5378651.3353084
#Sta/Elev= 30
  10.653   6.238  17.548   6.476  35.468   8.183  36.292   8.208  56.095   8.291
  57.264   8.297  65.243   6.624  68.079   5.063  69.857   4.283  70.285    4.07
  71.847    3.28  72.815   2.929  73.908   2.779  74.331   2.728  74.537   2.664
  75.607   2.398  78.837   1.984  89.664   1.783  92.043   2.125   93.28   2.241
  94.184   2.848    94.5   2.942  95.583   3.195  96.213   3.467  99.781   5.611
 103.502   6.695 111.867   6.996 116.573   7.124  127.67   7.276 146.176   7.997
#Mann= 3 , 0 , 0
  10.653     .04       0  57.264    .045       0 103.502     .03       0
Levee=-1,56.09,8.29,0,,,,
Bank Sta=57.264,103.502
XS Rating Curve= 0 ,0
Exp/Cntr=0.3,0.1

Type RM Length L Ch R = 1 ,1038.850,97.122,98.076,97.578
BEGIN DESCRIPTION:
2008 Survey Section
END DESCRIPTION:
Node Name=BB7
XS GIS Cut Line= 2
299346.6748915995378558.28651821299210.1001466295378600.12819631
#Sta/Elev= 17
 175.444    4.67 183.494    4.88 204.414    7.59 228.494    8.05 239.174    8.27
 248.014    3.33 249.784    3.02 250.024     2.9 251.274    2.41 255.044     1.7
 267.684    1.68 269.814    2.23 272.984     2.7 280.074    6.86 287.564    7.01
 301.714    7.02 318.284    7.96
#Mann= 3 , 0 , 0
 175.444     .04       0 239.174    .036       0 280.074     .03       0
Levee=-1,238.7,8.26,0,,,,
Bank Sta=239.174,280.074
XS Rating Curve= 0 ,0
Exp/Cntr=0.3,0.1

Type RM Length L Ch R = 1 ,940.7740,81.937,84.649,84.827
BEGIN DESCRIPTION:
Interpolated Section
END DESCRIPTION:
Node Name=BB6a
XS GIS Cut Line= 2
299289.5190004735378475.50399297  299176.63230175378507.59647093
#Sta/Elev= 27
   88.93   4.917  94.131   4.978  94.298   4.992 103.705   4.341 107.647   4.436
 108.295     4.4 123.204   4.574 129.424   4.653 130.104   4.659 135.816   2.339
 136.959   2.189 137.114   2.132 137.922   1.901 140.358   1.558 148.524   1.503
 150.956   1.841 154.575   2.183 154.621   2.196 157.665   3.135 162.669   5.293
 162.859   5.332 170.583   5.733 171.219   5.736 182.172   5.714 187.373   5.687
  194.98   5.821  206.29   6.323
#Mann= 3 , 0 , 0
   88.93     .04       0 130.104    .036       0 162.669     .03       0
Levee=-1,130.08,4.68,0,,,,
Bank Sta=130.104,162.669
XS Rating Curve= 0 ,0
Exp/Cntr=0.3,0.1

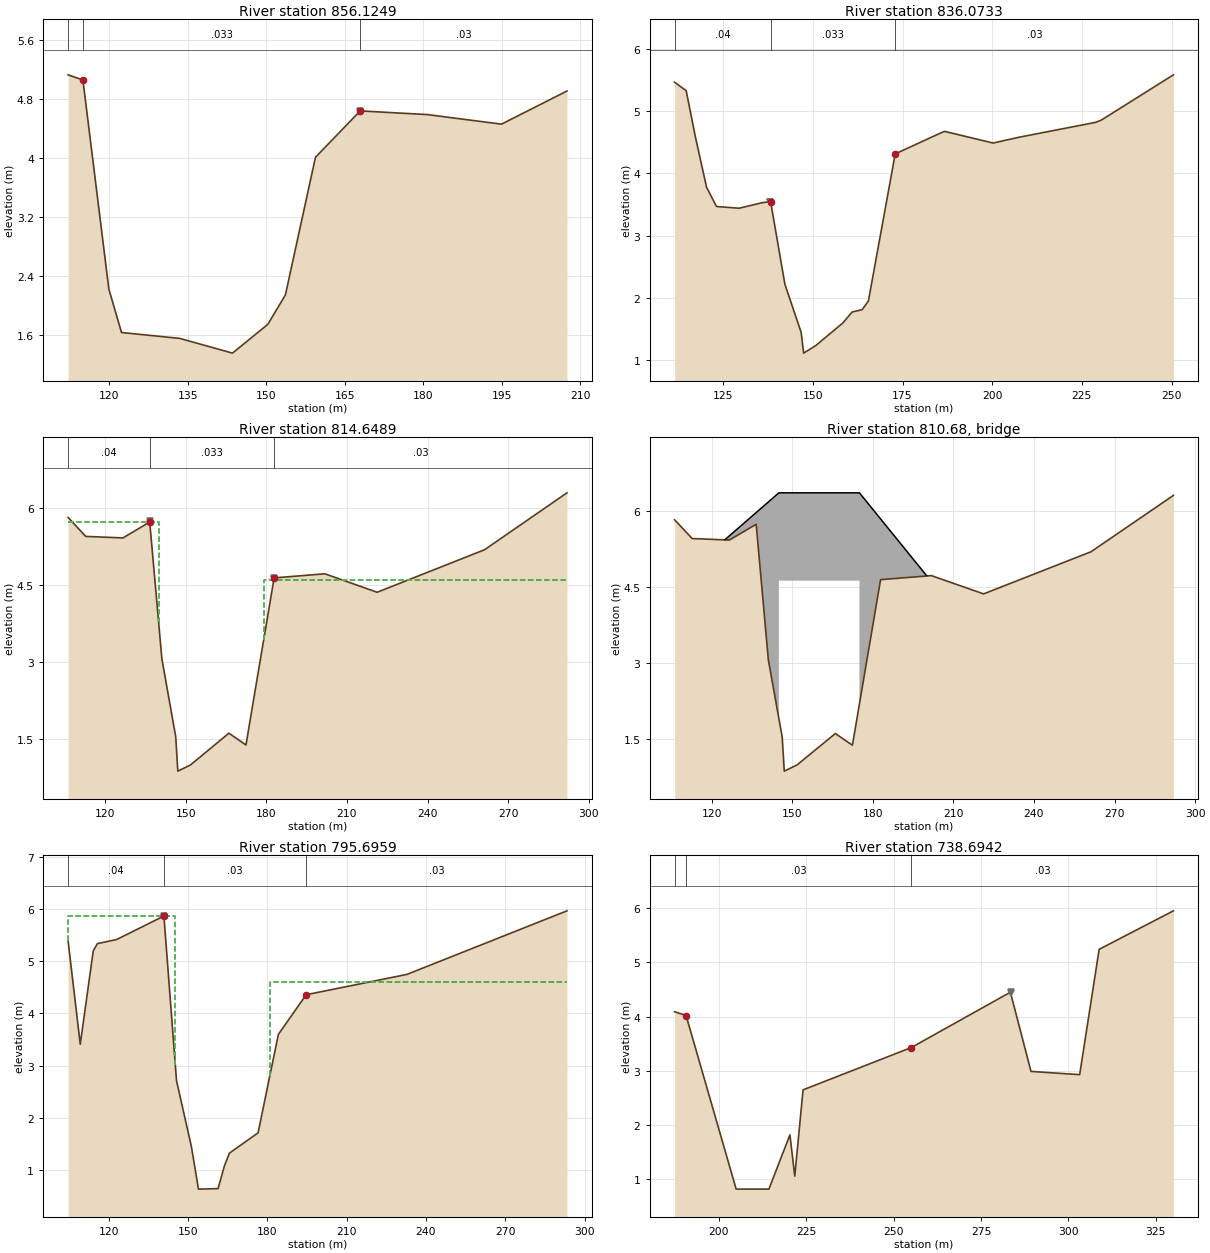
Type RM Length L Ch R = 1 ,856.1249,20.593,20.052,19.351
BEGIN DESCRIPTION:
2008 Survey Section
END DESCRIPTION:
Node Name=BB6
XS GIS Cut Line= 2
299262.0412684325378398.81673008 299169.088876585378420.15556043
#Sta/Elev= 13
 112.121    5.13 114.951    5.06 119.911    2.22 122.331    1.63 133.471    1.55
 143.541    1.35 150.291    1.74 153.661    2.14 159.411    4.01 167.961    4.64
 180.791    4.59 194.971    4.46 207.491    4.91
#Mann= 3 , 0 , 0
 112.121     .04       0 114.951    .033       0 167.961     .03       0
Levee=0,,,-1,167.98,4.63,,
Bank Sta=114.951,167.961
XS Rating Curve= 0 ,0
Exp/Cntr=0.3,0.1

Type RM Length L Ch R = 1 ,836.0733,22.384,21.424,19.965
BEGIN DESCRIPTION:
Interpolated Section
END DESCRIPTION:
Node Name=BB5a
XS GIS Cut Line= 2
299268.8219511995378376.18757931299134.3559988055378411.67550076
#Sta/Elev= 25
  111.46   5.464   114.7   5.327 117.229   4.595  120.38   3.778 123.151    3.47
 129.445   3.442 135.907   3.531 138.226    3.55 142.215   2.223  146.76   1.448
 147.438   1.118 150.789   1.238  158.32   1.599 160.976   1.778 163.752   1.815
 165.493   1.954 172.955   4.308 173.022   4.315   186.4   4.669 186.805   4.674
  200.25   4.488 207.488   4.581 228.713   4.818 230.347   4.853  250.53   5.582
#Mann= 3 , 0 , 0
  111.46     .04       0 138.226    .033       0 173.022     .03       0
Levee=-1,138.2,3.55,0,,,,
Bank Sta=138.226,173.022
XS Rating Curve= 0 ,0
Exp/Cntr=0.3,0.1

Type RM Length L Ch R = 1 ,814.6489,18.459,18.953,19.95
BEGIN DESCRIPTION:
2008 Survey Section
END DESCRIPTION:
Node Name=BB5
XS GIS Cut Line= 2
299276.9551404685378350.11388619  299099.7180702 5378405.7680387
#Sta/Elev= 15
 106.164    5.82 112.714    5.45 126.584    5.42 136.554    5.73 141.084    3.06
 146.244    1.54 147.014     .87 151.724     .99 166.044    1.61 172.394    1.38
 182.884    4.64 201.784    4.72 221.254    4.36 261.264    5.19 291.934     6.3
#Mann= 3 , 0 , 0
 106.164     .04       0 136.554    .033       0 182.884     .03       0
Levee=-1,136.59,5.75,-1,182.82,4.63,,
#XS Ineff= 2 , 0
       0     140    5.73     179       0     4.6
Permanent Ineff=
       F       F
Bank Sta=136.554,182.884
XS Rating Curve= 0 ,0
Exp/Cntr=0.5,0.3

Type RM Length L Ch R = 3 ,810.68  ,,,
BEGIN DESCRIPTION:
West Street Bridge
END DESCRIPTION:
Bridge Culvert--1,0,-1,-1, 0
Deck Dist Width WeirC Skew NumUp NumDn MinLoCord MaxHiCord MaxSubmerge Is_Ogee
3.97,11.06,1.6,0, 6, 6, , , 0.98, 0, 1,1,,
     125     145     145     175     175     200
    5.43    6.35    6.35    6.35    6.35    4.72
       0       0    4.62    4.62       0       0
  123.09     148     148     178     178   210.5
    5.42    6.35    6.35    6.35    6.35    4.52
       0       0    4.62    4.62       0       0
BR Coef=-1 , 0 , 0 ,, 0 ,,,0.8,-1,,0,
WSPro=,,,, 1 ,,,, 0 ,,,, 0 ,,,,-1 ,-1 ,-1 , 0 , 0 , 0 , 0 , 0
BC Design=,, 0 ,, 0 ,,,,,,
BC Use User HTab Curves=0
BC User HTab FreeFlow(D)= 0

Type RM Length L Ch R = 1 ,795.6959,71.29,57.002,36.886
BEGIN DESCRIPTION:
2008 Survey Section
END DESCRIPTION:
Node Name=BB4
XS GIS Cut Line= 3
299273.9015670265378331.84785611299103.7365074265378384.85630912
299093.8644150325378387.93158407
#Sta/Elev= 17
  104.72    5.39  109.31    3.41  114.22     5.2  115.77    5.34  123.09    5.42
  140.93    5.87   145.7    2.71  151.31    1.45     154     .63  161.41     .64
  163.77    1.07  165.69    1.32  176.53    1.71  184.21     3.6  194.72    4.36
  232.79    4.75  293.29    5.97
#Mann= 3 , 0 , 0
  104.72     .04       0  140.93     .03       0  194.72     .03       0
Levee=-1,140.88,5.86,0,,,,
#XS Ineff= 2 , 0
       0   145.3    5.87     181       0     4.6
Permanent Ineff=
       F       F
Bank Sta=140.93,194.72
XS Rating Curve= 0 ,0
Exp/Cntr=0.5,0.3

Type RM Length L Ch R = 1 ,738.6942,67.074,56.795,41.781
BEGIN DESCRIPTION:
2008 Survey Section
END DESCRIPTION:
Node Name=BB3
XS GIS Cut Line= 3
299199.8787955965378292.15458574299107.6693190495378383.02553655
299098.282487735 5378392.2761073
#Sta/Elev= 13
  187.38    4.09  190.67    4.02  204.99     .82  214.35     .82  220.36    1.82
  221.75    1.06  224.12    2.65  255.08    3.43   283.4    4.45  289.29    2.99
  303.21    2.93  308.78    5.24  330.02    5.95
#Mann= 3 , 0 , 0
  187.38     .04       0  190.67     .03       0  255.08     .03       0
Levee=0,,,-1,283.48,4.45,,
Bank Sta=190.67,255.08
XS Rating Curve= 0 ,0
Exp/Cntr=0.3,0.1

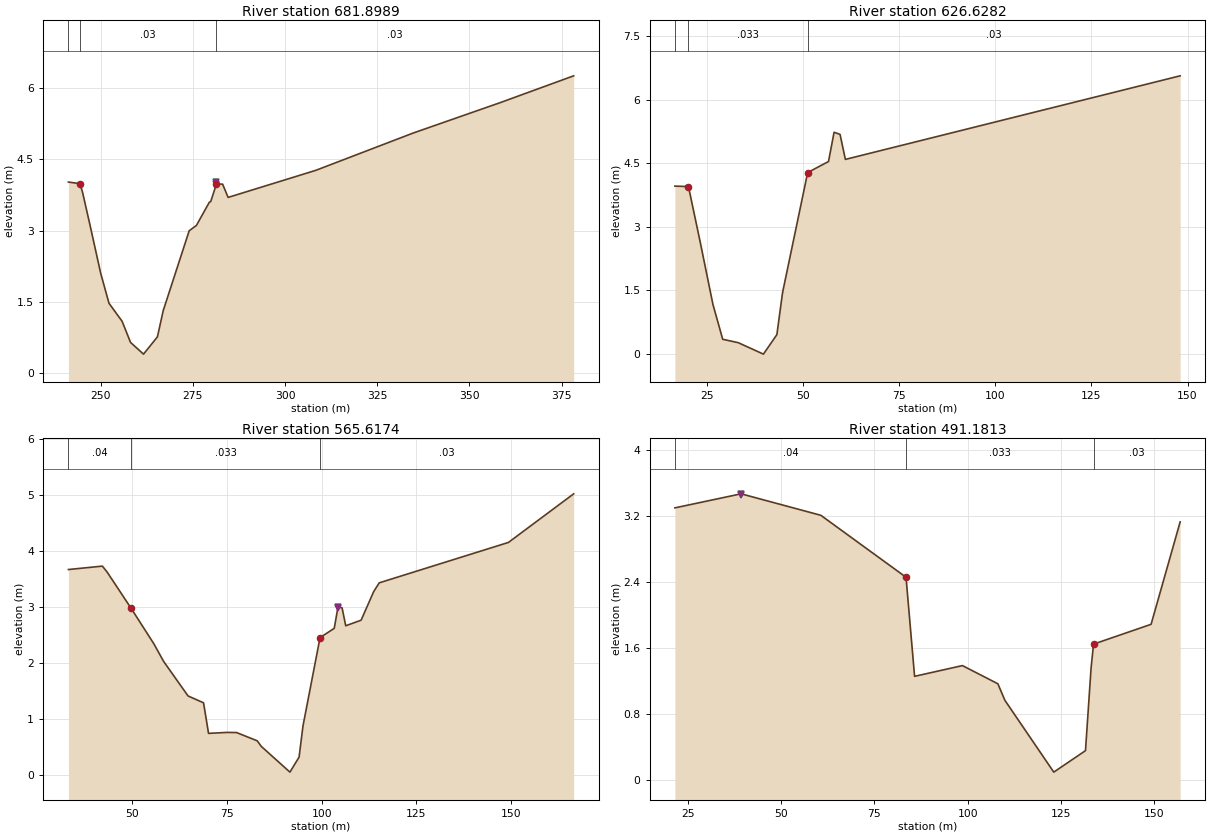
Type RM Length L Ch R = 1 ,681.8989,63.606,55.271,49.993
BEGIN DESCRIPTION:
Interpolated Section
END DESCRIPTION:
Node Name=BB2a
XS GIS Cut Line= 3
299139.2552421285378276.84543925299090.8326266115378398.15095988
299088.4799503045378404.04474776
#Sta/Elev= 23
 241.292   4.024 244.413   3.991 245.096   3.817 247.056   3.149 250.043   2.104
 252.289   1.474 255.851   1.094  258.13     .65 261.649    .404 265.414    .767
 267.017   1.329 267.028   1.329  274.03       3 275.983   3.111  279.49     3.6
  279.86   3.613  281.42   3.983 283.087    3.98 284.582   3.701 308.363   4.271
 334.773   5.056 358.443   5.698 378.251   6.259
#Mann= 3 , 0 , 0
 241.292     .04       0 244.413     .03       0  281.42     .03       0
Levee=0,,,-1,281.4,4.03,,
Bank Sta=244.413,281.42
XS Rating Curve= 0 ,0
Exp/Cntr=0.3,0.1

Type RM Length L Ch R = 1 ,626.6282,58.72,61.011,61.078
BEGIN DESCRIPTION:
2008 Survey Section
END DESCRIPTION:
Node Name=BB2
XS GIS Cut Line= 2
299082.5492337485378262.56919484299085.0328686995378393.97606229
#Sta/Elev= 16
  16.645    3.96  20.175    3.95  23.165    2.67  26.545    1.17  29.085     .35
  33.115     .27  39.675       0  43.175     .46  44.665    1.46  44.675    1.46
  51.185    4.28  56.605    4.54  58.055    5.23  59.605    5.18  60.995    4.59
 148.075    6.56
#Mann= 3 , 0 , 0
  16.645     .04       0  20.175    .033       0  51.185     .03       0
Bank Sta=20.175,51.185
XS Rating Curve= 0 ,0
Exp/Cntr=0.3,0.1

Type RM Length L Ch R = 1 ,565.6174,73.909,74.436,75.815
BEGIN DESCRIPTION:
Interpolated Section
END DESCRIPTION:
Node Name=BB1a
XS GIS Cut Line= 2
299027.9215376945378232.95440991 299015.484348895378365.61775714
#Sta/Elev= 26
  33.236   3.663  42.189   3.724  43.443   3.618  49.773    2.97  55.737    2.34
  58.345   2.022  64.788   1.405   68.87   1.283  70.187    .737  75.009    .754
  77.565    .752  83.028    .604  84.109    .504  91.647    .045  94.064    .313
  95.092    .869  99.593   2.447 103.335   2.613 104.336   2.998 105.406   2.978
 106.366   2.659 110.422   2.758 113.735   3.268 115.193   3.425 149.275   4.147
 166.481   5.015
#Mann= 3 , 0 , 0
  33.236     .04       0  49.773    .033       0  99.593     .03       0
Levee=0,,,-1,104.3,3,,
Bank Sta=49.773,99.593
XS Rating Curve= 0 ,0
Exp/Cntr=0.3,0.1

Type RM Length L Ch R = 1 ,491.1813,180,200,230
BEGIN DESCRIPTION:
2008 Survey Section
END DESCRIPTION:
Node Name=BB1
XS GIS Cut Line= 2
298957.0029866265378194.29174627298946.2925461565378329.32729963
#Sta/Elev= 14
  21.503     3.3  39.253    3.47  60.633    3.21  83.473    2.46  85.763    1.26
  98.593    1.39 108.093    1.17 109.973     .97 123.083      .1 131.583     .36
 133.083    1.36 133.743    1.65 149.173    1.89 156.963    3.13
#Mann= 3 , 0 , 0
  21.503     .04       0  83.473    .033       0 133.743     .03       0
Levee=-1,39.15,3.46,0,,,,
Bank Sta=83.473,133.743
XS Rating Curve= 0 ,0
Exp/Cntr=0.3,0.1

--- Blanche_Brook.g05 (geometry) ---

Geom Title=Structure Blockage Analysis w Ice Cover
Program Version=4.00

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
River Reach=Blanche Brook   ,US of Confluence

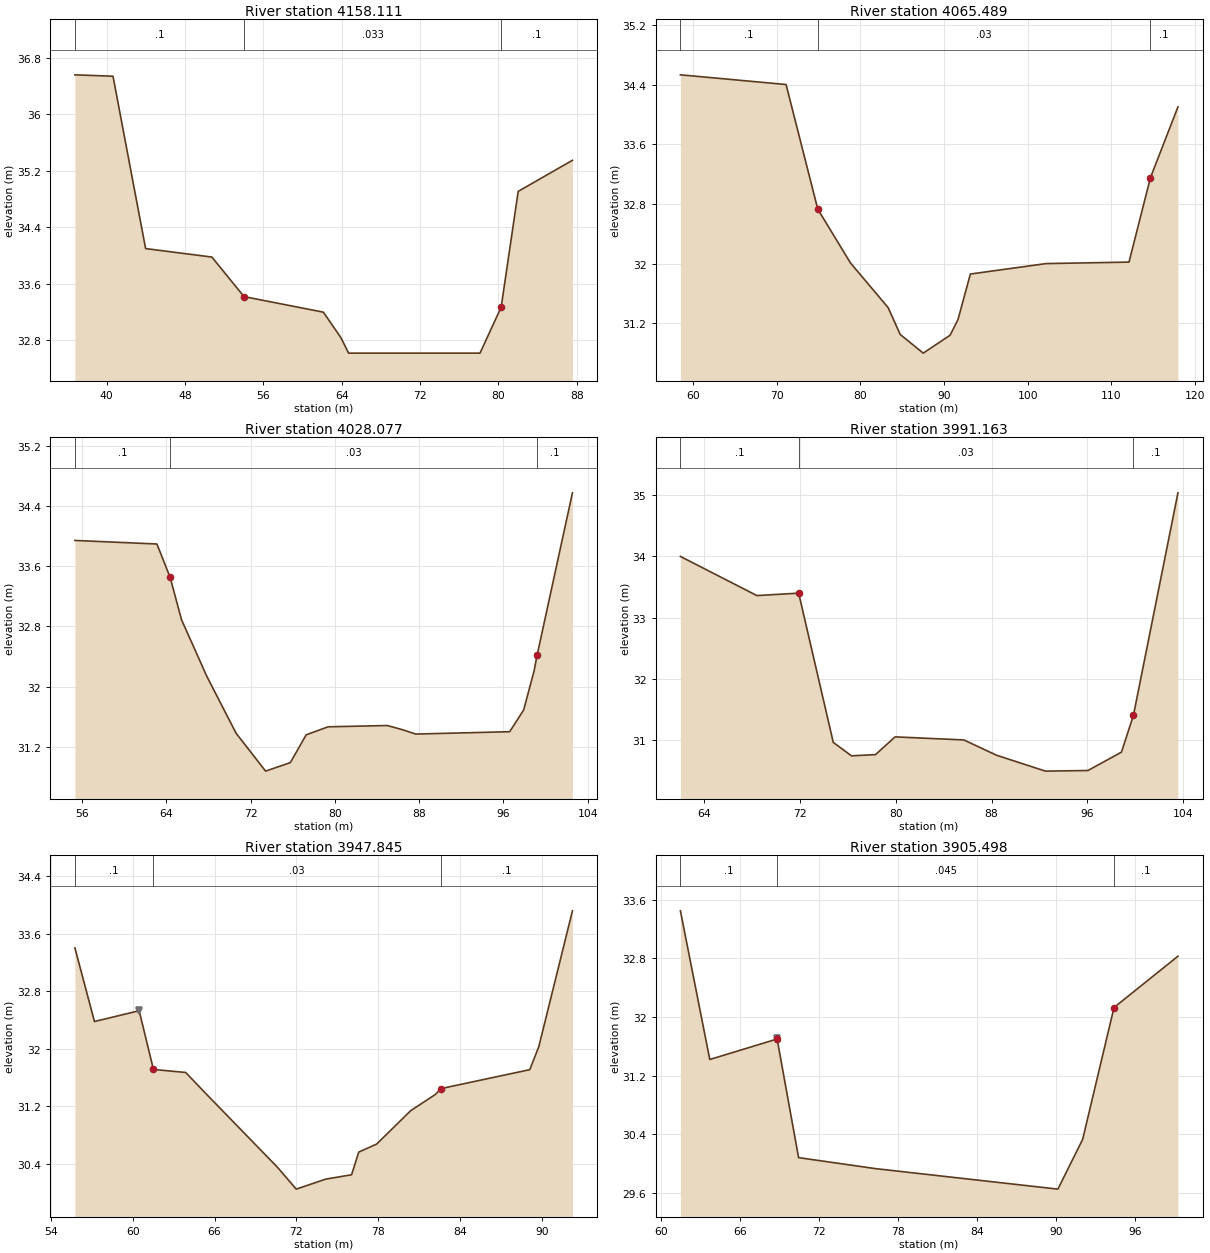
Type RM Length L Ch R = 1 ,4158.111,56.608,50.986,38.986
BEGIN DESCRIPTION:
2008 Survey Section
END DESCRIPTION:
Node Name=BB39
XS GIS Cut Line= 2
298673.7152083715380853.34084345 298671.076662985380802.59958592
#Sta/Elev= 12
  36.751   36.56  40.641   36.54  43.971    34.1  50.741   33.98  54.021   33.42
  62.121    33.2  63.911   32.84  64.701   32.62  78.121   32.62  80.281   33.27
  82.021   34.91  87.561   35.35
#Mann= 3 , 0 , 0
  36.751      .1       0  54.021    .033       0  80.281      .1       0
Bank Sta=54.021,80.281
XS Rating Curve= 0 ,0
Exp/Cntr=0.3,0.1

Type RM Length L Ch R = 1 ,4065.489,38.598,37.412,37.41
BEGIN DESCRIPTION:
2008 Survey Section
END DESCRIPTION:
Node Name=BB38
XS GIS Cut Line= 2
298755.4837313625380786.51361197 298700.593541525380763.62888025
#Sta/Elev= 14
  58.474   34.53  71.104    34.4  74.894   32.73  78.794   32.01  83.304   31.41
   84.75   31.05    87.5    30.8   90.71   31.04  91.654   31.25  93.134   31.86
 102.184      32 112.094   32.02 114.654   33.15 117.944    34.1
#Mann= 3 , 0 , 0
  58.474      .1       0  74.894     .03       0 114.654      .1       0
Bank Sta=74.894,114.654
XS Rating Curve= 0 ,0
Exp/Cntr=0.3,0.1

Type RM Length L Ch R = 1 ,4028.077,36.768,36.914,37.219
BEGIN DESCRIPTION:
Interpolated Section
END DESCRIPTION:
Node Name=BB37a
XS GIS Cut Line= 2
298751.6701636045380744.77469999298708.0944586265380726.52001277
#Sta/Elev= 19
  55.314  33.941  63.101  33.894  64.351  33.453  65.438  32.889  67.842  32.137
  70.622  31.382  71.835  31.165   73.42   30.88   75.77  30.993  77.278  31.362
  79.355  31.468  84.991  31.485    86.5  31.426  87.672  31.372  96.598  31.403
  97.924  31.691  98.906  32.204  99.206   32.42 102.559  34.573
#Mann= 3 , 0 , 0
  55.314      .1       0  64.351     .03       0  99.206      .1       0
Bank Sta=64.351,99.206
XS Rating Curve= 0 ,0
Exp/Cntr=0.3,0.1

Type RM Length L Ch R = 1 ,3991.163,44.678,43.318,41.969
BEGIN DESCRIPTION:
2008 Survey Section
END DESCRIPTION:
Node Name=BB37
XS GIS Cut Line= 3
298764.9254170855380712.09629316298759.2073460725380709.23725765
298727.7416325775380693.50440091
#Sta/Elev= 14
      62      34  68.393   33.36  71.883    33.4  74.773   30.96  76.293   30.74
    78.3   30.76  79.943   31.05  85.683      31  88.413   30.75    92.5   30.49
   96.05    30.5  98.853    30.8  99.853    31.4 103.573   35.04
#Mann= 3 , 0 , 0
      62      .1       0  71.883     .03       0  99.853      .1       0
Bank Sta=71.883,99.853
XS Rating Curve= 0 ,0
Exp/Cntr=0.3,0.1

Type RM Length L Ch R = 1 ,3947.845,45.414,42.347,39.914
BEGIN DESCRIPTION:
Interpolated Section
END DESCRIPTION:
Node Name=BB36a
XS GIS Cut Line= 2
298783.5906972145380667.79544014298748.1588359315380659.09287772
#Sta/Elev= 18
  55.762  33.406  57.194  32.382  60.474  32.532  61.521  31.715  63.888  31.673
  65.264  31.399  70.616  30.354   71.99   30.05  74.155  30.189   76.05   30.25
  76.576  30.565  77.889  30.677  80.383  31.141  82.193  31.367  82.615  31.449
  89.117  31.712   89.78  32.032  92.247  33.922
#Mann= 3 , 0 , 0
  55.762      .1       0  61.521     .03       0  82.615      .1       0
Levee=-1,60.47,32.54,0,,,,
Bank Sta=61.521,82.615
XS Rating Curve= 0 ,0
Exp/Cntr=0.3,0.1

Type RM Length L Ch R = 1 ,3905.498,44.577,44.11,42.837
BEGIN DESCRIPTION:
2008 Survey Section
END DESCRIPTION:
Node Name=BB36
XS GIS Cut Line= 2
298793.5339148415380621.95262812298755.8004084925380623.36763461
#Sta/Elev= 9
  61.485   33.45  63.715   31.42  68.825    31.7  70.455   30.08  76.285   29.93
  90.135   29.65  92.015   30.33  94.395   32.13  99.245   32.83
#Mann= 3 , 0 , 0
  61.485      .1       0  68.825    .045       0  94.395      .1       0
Levee=-1,68.84,31.71,0,,,,
Bank Sta=68.825,94.395
XS Rating Curve= 0 ,0
Exp/Cntr=0.3,0.1

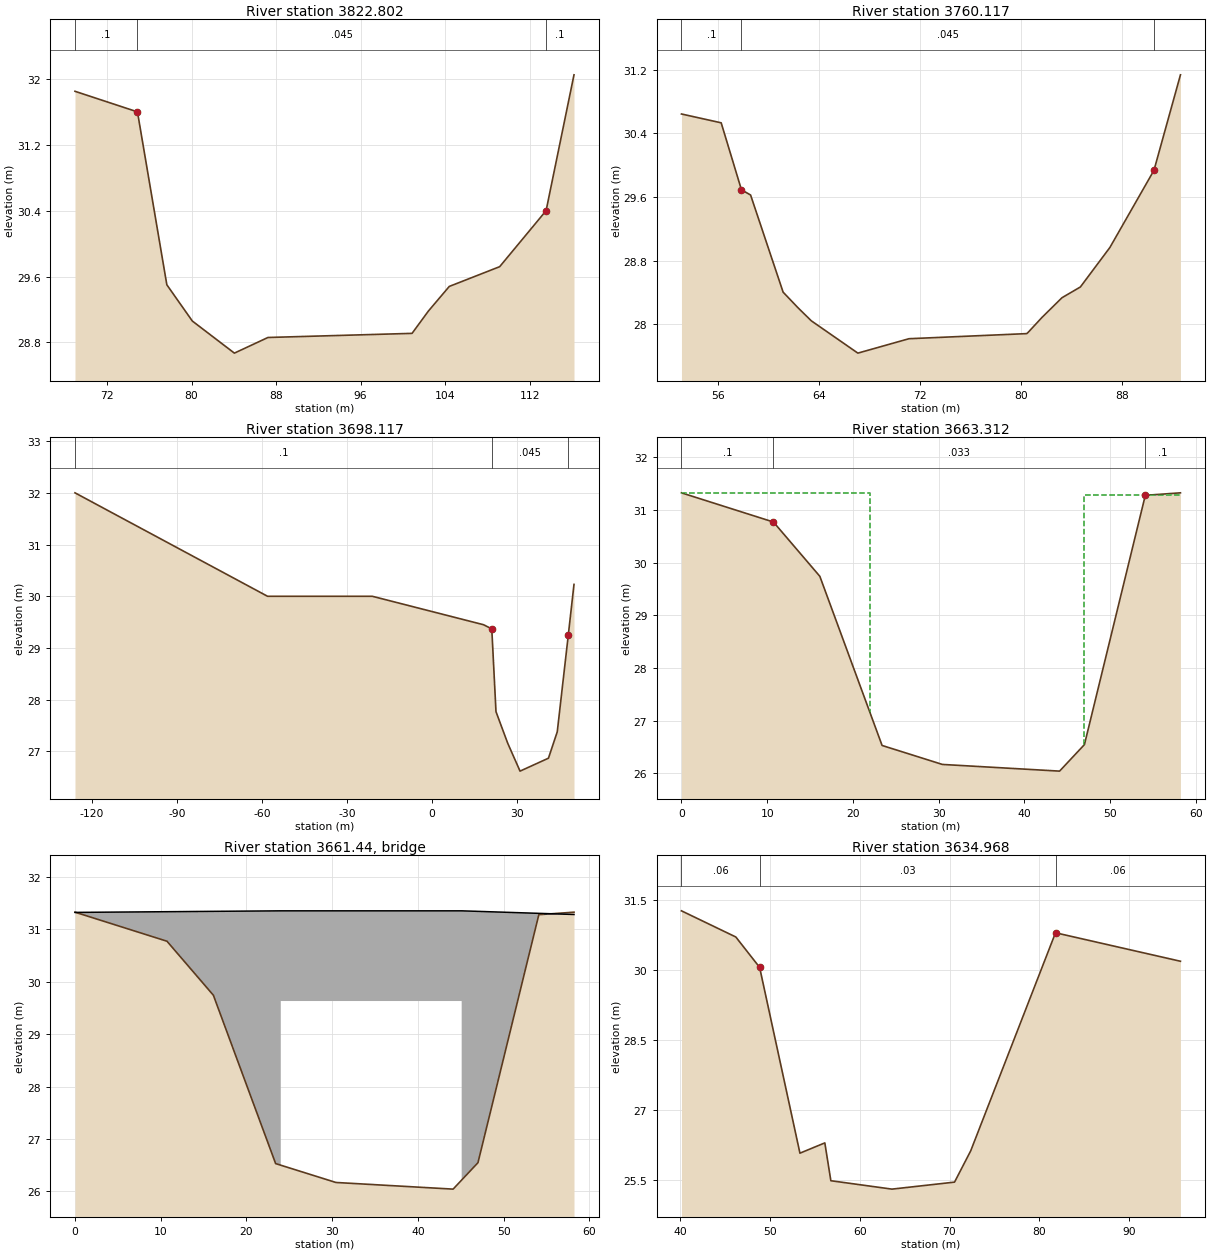
Type RM Length L Ch R = 1 ,3822.802,61.91,62.684,63.038
BEGIN DESCRIPTION:
2008 Survey Section
END DESCRIPTION:
Node Name=BB35
XS GIS Cut Line= 2
298777.8696352115380538.01749845298731.3351375525380551.67608821
#Sta/Elev= 12
  68.973   31.85  74.883    31.6  77.663    29.5  80.073   29.06  84.053   28.67
   87.23   28.86 100.863   28.91 102.403   29.18 104.383   29.48 109.153   29.72
 113.543    30.4 116.183   32.05
#Mann= 3 , 0 , 0
  68.973      .1       0  74.883    .045       0 113.543      .1       0
Bank Sta=74.883,113.543
XS Rating Curve= 0 ,0
Exp/Cntr=0.3,0.1

Type RM Length L Ch R = 1 ,3760.117,58.614,62,62.497
BEGIN DESCRIPTION:
Interpolated Section
END DESCRIPTION:
Node Name=BB34a
XS GIS Cut Line= 2
298769.9586677435380478.33507839298731.0398285855380485.25398313
#Sta/Elev= 17
  53.088  30.643  56.235  30.532   57.84  29.691  58.565  29.625  61.141  28.405
  62.332  28.207  63.374  28.045  67.062  27.639   71.11   27.82  80.432  27.884
  80.517  27.894  81.657  28.089  83.232  28.335  84.689   28.47  87.026  28.966
  90.517  29.935  92.617  31.135
#Mann= 3 , 0 , 0
  53.088      .1       0   57.84    .045       0  90.517      .1       0
Bank Sta=57.84,90.517
XS Rating Curve= 0 ,0
Exp/Cntr=0.3,0.1

Type RM Length L Ch R = 1 ,3698.117,12.698,16.184,17.773
BEGIN DESCRIPTION:
2008 Survey Section
END DESCRIPTION:
Node Name=BB34
XS GIS Cut Line= 3
298910.5745372965380453.29789571298768.7181217225380426.94205896
298737.3256638325380421.10958045
#Sta/Elev= 12
    -126      32     -58      30     -21      30  18.284   29.45  21.184   29.37
  22.664   27.77  26.804   27.16  31.164   26.62  41.194   26.87  44.304   27.38
    48.2   29.25  50.214   30.23
#Mann= 3 , 0 , 0
    -126      .1       0  21.184    .045       0    48.2      .1       0
Bank Sta=21.184,48.2
XS Rating Curve= 0 ,0
Exp/Cntr=0.3,0.1

Type RM Length L Ch R = 1 ,3663.312,28.407,28.345,23.772
BEGIN DESCRIPTION:
2008 Survey Section
END DESCRIPTION:
Node Name=BB33
XS GIS Cut Line= 3
298773.493453953 5380419.3569334298765.3284293535380414.64798742
298747.8633755695380369.10757782
#Sta/Elev= 9
       0 31.3243   10.73   30.77   16.14   29.74    23.4   26.53   30.43   26.17
    44.1  26.043      47 26.5466    54.131.27667    58.2 31.3243
#Mann= 3 , 0 , 0
       0      .1       0   10.73    .033       0    54.1      .1       0
#XS Ineff= 2 , 0
       0      22   31.32      47       0   31.29
Permanent Ineff=
       F       F
Bank Sta=10.73,54.1
XS Rating Curve= 0 ,0
Exp/Cntr=0.5,0.3

Type RM Length L Ch R = 3 ,3661.44 ,,,
BEGIN DESCRIPTION:
Hansen Highway Bridge
END DESCRIPTION:
Bridge Culvert--1,0,-1,-1, 0
Deck Dist Width WeirC Skew NumUp NumDn MinLoCord MaxHiCord MaxSubmerge Is_Ogee
1.88,19.66,1.6,0, 6, 6, , , 0.98, 0, 1,1,,
       0      24      24    45.1    45.1    58.2
   31.32   31.35   31.35   31.35   31.35   31.28
       0       0   29.63   29.63       0       0
   40.16      53      53    74.1    74.1    81.8
   31.27   31.35   31.35   31.35   31.35    30.8
       0       0   29.63    29.6       0       0
BR Coef=-1 , 0 , 0 ,, 0 ,,,0.8,-1,,0,
WSPro=,,,, 1 ,,,, 0 ,,,, 0 ,,,,-1 ,-1 ,-1 , 0 , 0 , 0 , 0 , 0
BC Design=,, 0 ,, 0 ,,,,,,
BC Use User HTab Curves=0
BC User HTab FreeFlow(D)= 0

Type RM Length L Ch R = 1 ,3634.968,58.975,57.091,54.669
BEGIN DESCRIPTION:
2008 Survey Section
END DESCRIPTION:
Node Name=BB32
XS GIS Cut Line= 2
298775.0955149675380383.50380243298740.4601418835380322.35740304
#Sta/Elev= 11
  40.159   31.27  46.209   30.71  48.859   30.06  53.349   26.08  56.119    26.3
   56.79   25.49   63.59   25.31  70.559   25.46  72.359   26.13  81.799    30.8
  95.709   30.19
#Mann= 3 , 0 , 0
  40.159     .06       0  48.859     .03       0  81.799     .06       0
Bank Sta=48.859,81.799
XS Rating Curve= 0 ,0
Exp/Cntr=0.5,0.3

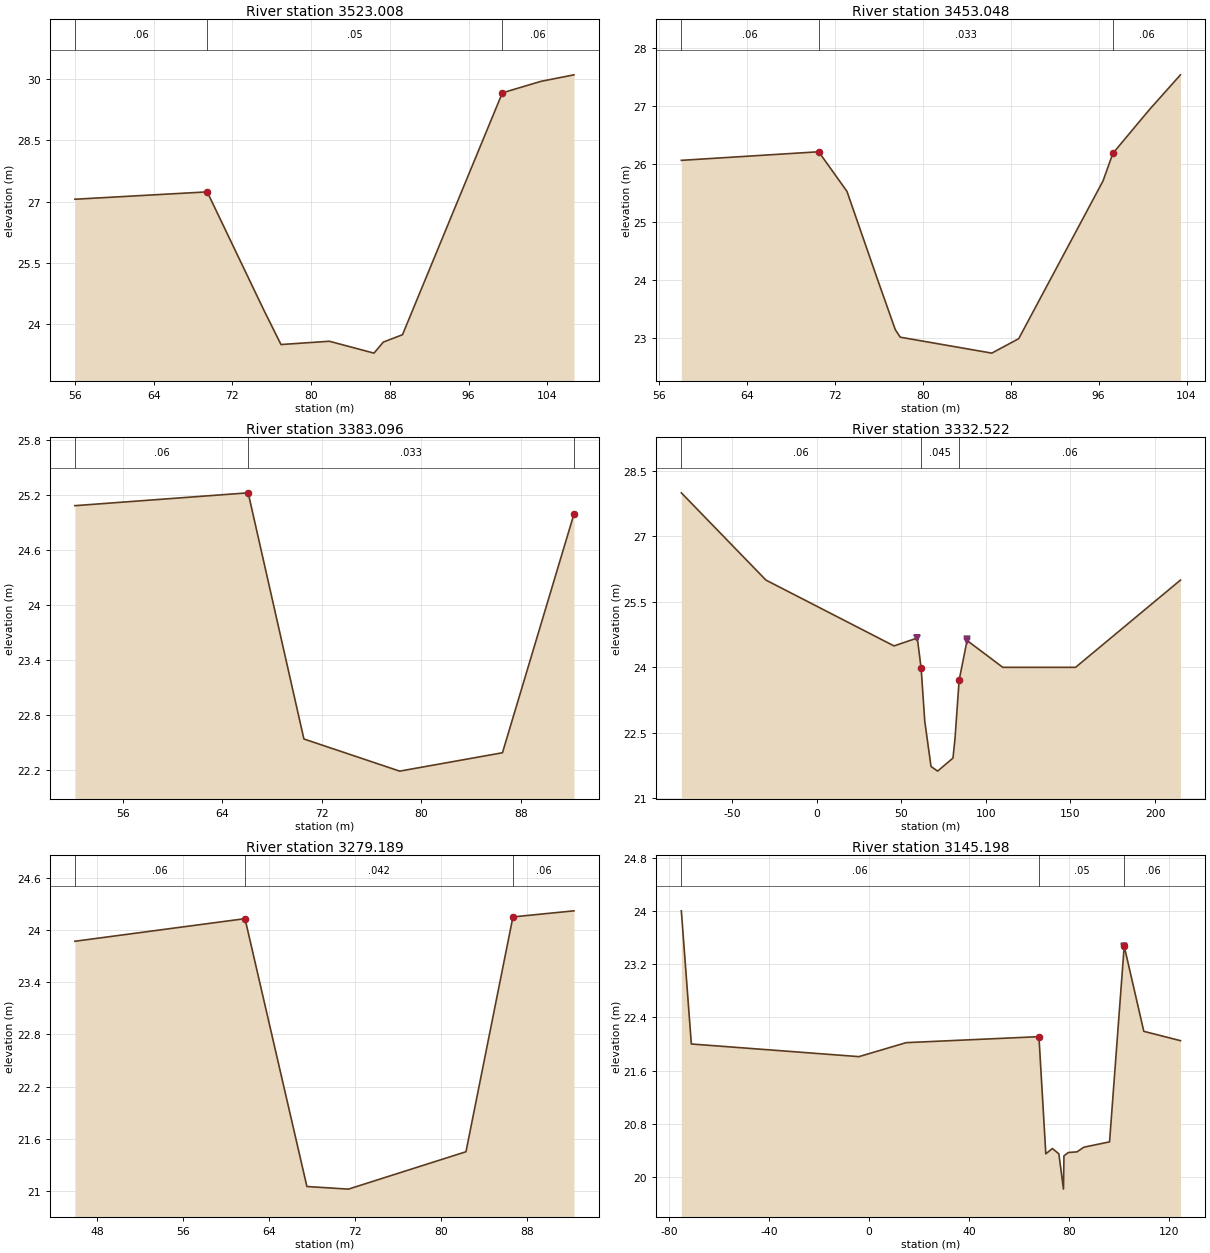
Type RM Length L Ch R = 1 ,3523.008,69.291,69.959,70.085
BEGIN DESCRIPTION:
2008 Survey Section
END DESCRIPTION:
Node Name=BB31
XS GIS Cut Line= 3
298832.3941906645380276.10690404298832.3941906645380276.10690404
298789.2477190425380249.42421764
#Sta/Elev= 11
  55.988   27.06  69.438   27.24  75.198   24.35  76.938   23.51   81.85   23.59
  86.388    23.3   87.34   23.57  89.288   23.75  99.438   29.66 103.348   29.94
 106.718    30.1
#Mann= 3 , 0 , 0
  55.988     .06       0  69.438     .05       0  99.438     .06       0
Bank Sta=69.438,99.438
XS Rating Curve= 0 ,0
Exp/Cntr=0.3,0.1

Type RM Length L Ch R = 1 ,3453.048,69.452,69.952,70.023
BEGIN DESCRIPTION:
Interpolated Section
END DESCRIPTION:
Node Name=BB30a
XS GIS Cut Line= 2
298857.952628618 5380211.4348508298820.2367358365380186.11870359
#Sta/Elev= 12
  58.023   26.07  70.524  26.218  73.097  25.535  75.877  24.017  77.495   23.15
  77.945   23.02  86.278  22.745  88.727  22.994  96.401  25.715  97.299  26.191
 100.602   26.94 103.448  27.545
#Mann= 3 , 0 , 0
  58.023     .06       0  70.524    .033       0  97.299     .06       0
Bank Sta=70.524,97.299
XS Rating Curve= 0 ,0
Exp/Cntr=0.3,0.1

Type RM Length L Ch R = 1 ,3383.096,51.839,50.574,49.975
BEGIN DESCRIPTION:
2008 Survey Section
END DESCRIPTION:
Node Name=BB30
XS GIS Cut Line= 3
298899.4708048295380156.47007593 298874.948404555380138.98051497
298866.806920213 5380133.1739469
#Sta/Elev= 6
   52.14   25.08   66.07   25.22   70.55   22.54   78.25   22.19   86.51   22.39
   92.26   24.99
#Mann= 3 , 0 , 0
   52.14     .06       0   66.07    .033       0   92.26     .06       0
Bank Sta=66.07,92.26
XS Rating Curve= 0 ,0
Exp/Cntr=0.3,0.1

Type RM Length L Ch R = 1 ,3332.522,55.876,53.334,52.416
BEGIN DESCRIPTION:
Interpolated Section
END DESCRIPTION:
Node Name=BB29a
XS GIS Cut Line= 5
299033.1001833255380166.93724838 298922.090959655380107.98019658
298857.4339517015380073.64082873 298844.186395325380066.60504519
298732.8097724545380007.45286744
#Sta/Elev= 15
     -80      28     -30      26  45.694  24.491  59.453  24.672  61.735   23.98
  63.878  22.764  67.572  21.728  71.483  21.621  80.556  21.921  81.746  22.364
   84.18  23.701   88.89  24.615     110      24     153      24     215      26
#Mann= 3 , 0 , 0
     -80     .06       0  61.735    .045       0   84.18     .06       0
Levee=-1,59.47,24.67,-1,88.95,24.64,,
Bank Sta=61.735,84.18
XS Rating Curve= 0 ,0
Exp/Cntr=0.3,0.1

Type RM Length L Ch R = 1 ,3279.189,132.549,133.991,134.931
BEGIN DESCRIPTION:
2008 Survey Section
END DESCRIPTION:
Node Name=BB29
XS GIS Cut Line= 2
298941.8571116835380053.59592442298846.664155566 5380030.7989058
#Sta/Elev= 7
  45.937   23.87  61.767   24.13  67.527   21.05  71.387   21.02  82.327   21.45
  86.697   24.15  92.377   24.22
#Mann= 3 , 0 , 0
  45.937     .06       0  61.767    .042       0  86.697     .06       0
Bank Sta=61.767,86.697
XS Rating Curve= 0 ,0
Exp/Cntr=0.3,0.1

Type RM Length L Ch R = 1 ,3145.198,86.734,92.999,98.011
BEGIN DESCRIPTION:
Interpolated Section
END DESCRIPTION:
Node Name=BB28
XS GIS Cut Line= 6
299084.9688441235379990.36292937298950.048134001  5379925.460582
298943.706669001  5379922.365416298938.788753001  5379920.047918
   298927.120776  5379914.339685298905.1691484545379903.80580976
#Sta/Elev= 17
     -75      24     -71      22      -4   21.81   14.88   22.02   67.97   22.11
   70.72   20.35   73.33   20.43   75.94   20.35   77.78   19.82   77.97   20.32
   79.71   20.37   83.21   20.38   85.94   20.45    96.2   20.53  102.06   23.47
   109.9   22.19  124.55   22.05
#Mann= 3 , 0 , 0
     -75     .06       0   67.97     .05       0  102.06     .06       0
Levee=0,,,-1,102.08,23.46,,
Bank Sta=67.97,102.06
XS Rating Curve= 0 ,0
Exp/Cntr=0.3,0.1

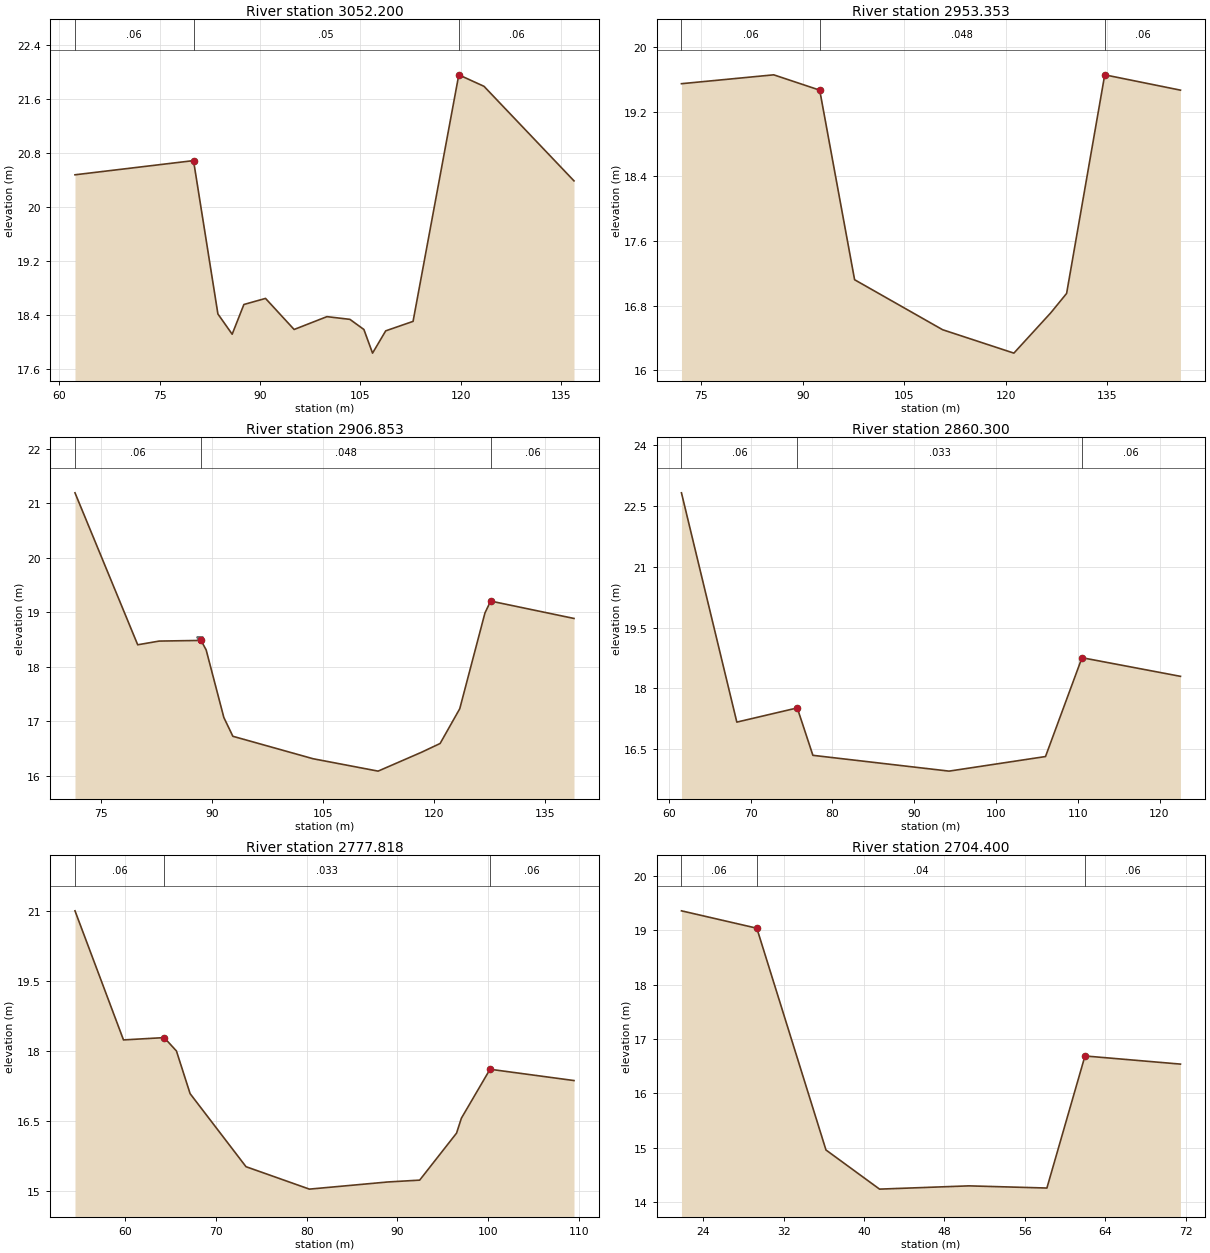
Type RM Length L Ch R = 1 ,3052.200,46.777,46.316,45.575
BEGIN DESCRIPTION:
2008 Survey Section
END DESCRIPTION:
Node Name=BB27
XS GIS Cut Line= 2
299048.4392323935379970.52160635298968.7777899655379734.72373676
#Sta/Elev= 16
  62.372   20.48  80.072   20.69  83.712   18.42  85.842   18.12  87.592   18.56
  90.822   18.65  95.092   18.19  99.992   18.38 103.422   18.34  105.51   18.19
 106.802   17.84  108.77   18.17 112.852   18.31 119.682   21.96 123.442   21.79
 136.882   20.39
#Mann= 3 , 0 , 0
  62.372     .06       0  80.072     .05       0 119.682     .06       0
Bank Sta=80.072,119.682
XS Rating Curve= 0 ,0
Exp/Cntr=0.3,0.1

Type RM Length L Ch R = 1 ,2953.353,50.421,46.5,44.883
BEGIN DESCRIPTION:
2008 Survey Section
END DESCRIPTION:
Node Name=BB26
XS GIS Cut Line= 2
299126.4199556795379877.36670024 299093.459059855379811.32461335
#Sta/Elev= 10
  72.061   19.55  85.711   19.66  92.511   19.47  97.671   17.12 110.691    16.5
 121.231   16.21 126.691   16.71 129.031   16.95 134.671   19.66 145.871   19.47
#Mann= 3 , 0 , 0
  72.061     .06       0  92.511    .048       0 134.671     .06       0
Bank Sta=92.511,134.671
XS Rating Curve= 0 ,0
Exp/Cntr=0.3,0.1

Type RM Length L Ch R = 1 ,2906.853,48.345,46.553,44.606
BEGIN DESCRIPTION:
Interpolated Section
END DESCRIPTION:
Node Name=BB25a
XS GIS Cut Line= 3
299168.4107590725379840.79985326299136.5495561975379800.87889946
299126.358653183 5379788.1100605
#Sta/Elev= 15
  71.485  21.189  79.958  18.402  82.853   18.47  88.516  18.482  89.207  18.307
  91.597  17.068  92.814  16.724 103.657  16.312 112.435  16.085 118.299  16.431
 120.812  16.592 123.464  17.229  126.87  18.986 127.636  19.204 138.899  18.885
#Mann= 3 , 0 , 0
  71.485     .06       0  88.516    .048       0 127.636     .06       0
Levee=-1,88.44,18.49,0,,,,
Bank Sta=88.516,127.636
XS Rating Curve= 0 ,0
Exp/Cntr=0.3,0.1

Type RM Length L Ch R = 1 ,2860.300,84.652,82.482,80.116
BEGIN DESCRIPTION:
2008 Survey Section
END DESCRIPTION:
Node Name=BB25
XS GIS Cut Line= 2
299207.4483746195379806.59041551299161.5662235355379766.37791238
#Sta/Elev= 8
  61.552   22.83  68.322   17.17  75.712   17.52  77.622   16.35  94.272   15.96
 106.062   16.32 110.522   18.76 122.562    18.3
#Mann= 3 , 0 , 0
  61.552     .06       0  75.712    .033       0 110.522     .06       0
Bank Sta=75.712,110.522
XS Rating Curve= 0 ,0
Exp/Cntr=0.3,0.1

Type RM Length L Ch R = 1 ,2777.818,74.613,73.418,70.108
BEGIN DESCRIPTION:
Interpolated Section
END DESCRIPTION:
Node Name=BB24a
XS GIS Cut Line= 2
299247.6661660225379721.71371389299196.204875676 5379702.3028763
#Sta/Elev= 13
  54.467  20.994  59.813  18.237  64.298  18.286  65.648  18.001  67.156  17.089
  73.317  15.529  80.304   15.05  88.963  15.203  92.458  15.242  96.522  16.246
  97.055  16.565 100.213   17.61 109.467  17.369
#Mann= 3 , 0 , 0
  54.467     .06       0  64.298    .033       0 100.213     .06       0
Bank Sta=64.298,100.213
XS Rating Curve= 0 ,0
Exp/Cntr=0.3,0.1

Type RM Length L Ch R = 1 ,2704.400,52.02,52.429,52.896
BEGIN DESCRIPTION:
2008 Survey Section
END DESCRIPTION:
Node Name=BB24
XS GIS Cut Line= 2
299259.6692445625379642.28641383299210.0312172815379641.18334655
#Sta/Elev= 8
  21.842   19.36  29.342   19.04  36.222   14.96  41.552   14.24  50.442    14.3
  58.202   14.26  61.992   16.69  71.492   16.54
#Mann= 3 , 0 , 0
  21.842     .06       0  29.342     .04       0  61.992     .06       0
Bank Sta=29.342,61.992
XS Rating Curve= 0 ,0
Exp/Cntr=0.3,0.1