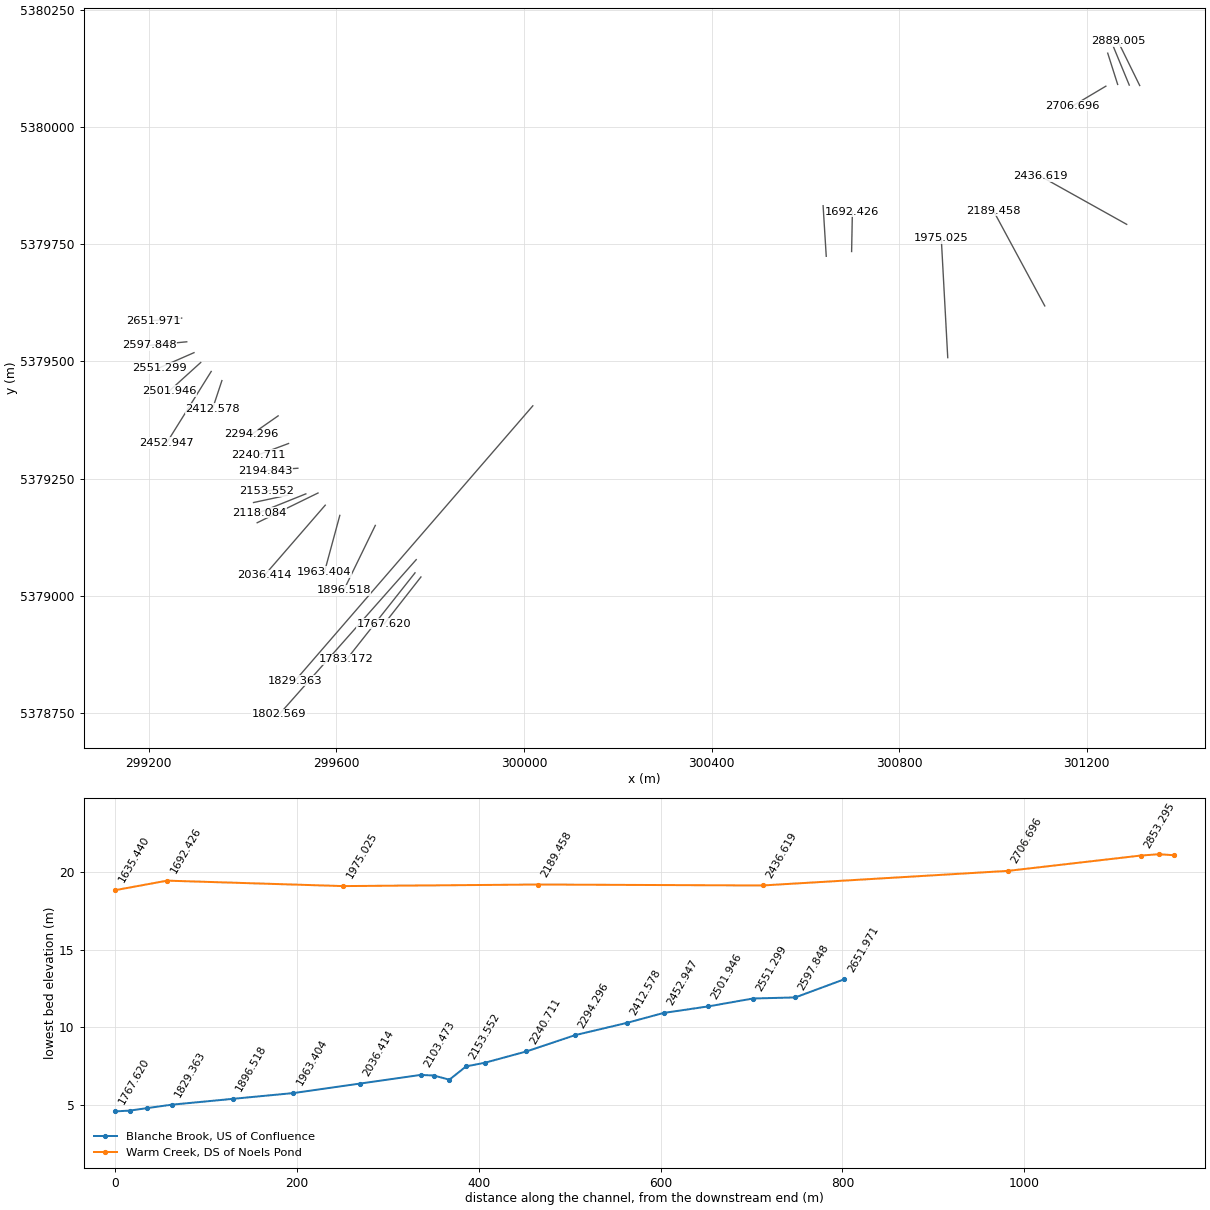
HEC-RAS study Blanche_Brook.prj: Stephenville Model

--- Blanche_Brook.g05 (geometry) --- (continued)

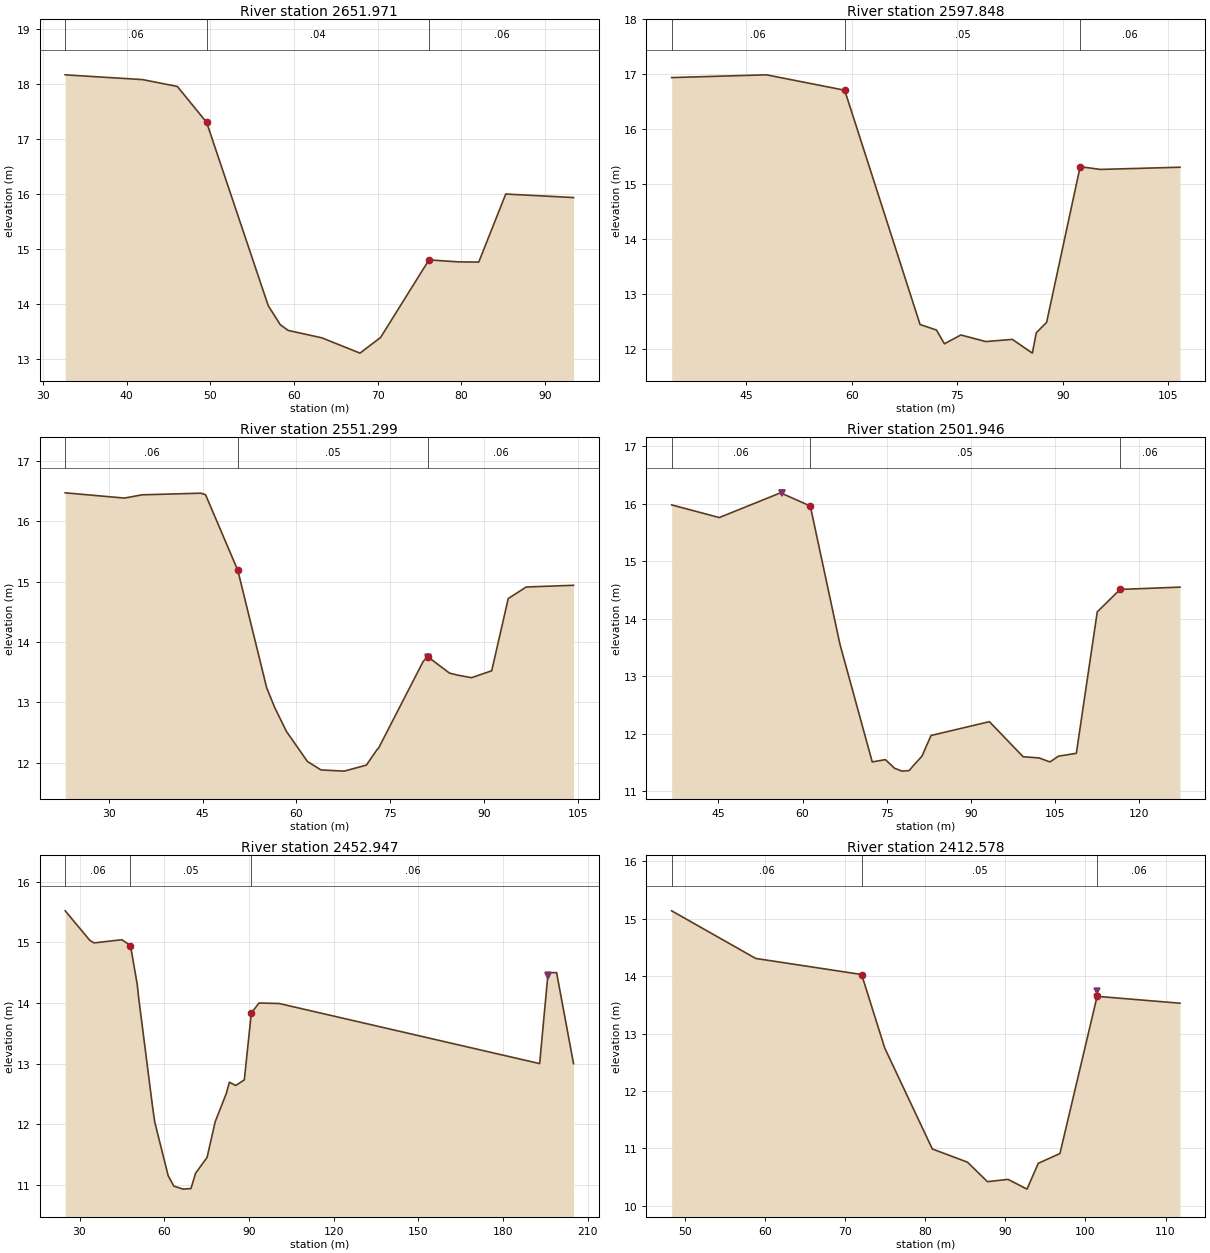
Type RM Length L Ch R = 1 ,2651.971,52.676,54.123,52.466
BEGIN DESCRIPTION:
Interpolated Section
END DESCRIPTION:
Node Name=BB23a
XS GIS Cut Line= 2
299270.1266359735379592.20213984299209.549906461 5379587.0466735
#Sta/Elev= 16
  32.642  18.169  41.906  18.082  46.057  17.957  49.555  17.304  56.922  13.968
  58.363  13.621    59.3  13.517  63.347  13.381  67.897  13.103  70.366  13.389
   75.48  14.637  76.167    14.8   79.67  14.764    82.1   14.76  85.333  15.999
  93.438  15.935
#Mann= 3 , 0 , 0
  32.642     .06       0  49.555     .04       0  76.167     .06       0
Bank Sta=49.555,76.167
XS Rating Curve= 0 ,0
Exp/Cntr=0.3,0.1

Type RM Length L Ch R = 1 ,2597.848,44.068,46.55,47.373
BEGIN DESCRIPTION:
2008 Survey Section
END DESCRIPTION:
Node Name=BB23
XS GIS Cut Line= 2
299280.9740230735379541.65443018299201.2944488485379534.09224837
#Sta/Elev= 15
  34.371   16.94  47.851   16.99  58.981   16.71  69.701   12.45   72.03   12.35
  73.161    12.1   75.51   12.26  79.051   12.14   82.83   12.18  85.671   11.93
   86.23    12.3  87.701   12.49  92.471   15.32  95.351   15.27 106.671   15.31
#Mann= 3 , 0 , 0
  34.371     .06       0  58.981     .05       0  92.471     .06       0
Bank Sta=58.981,92.471
XS Rating Curve= 0 ,0
Exp/Cntr=0.3,0.1

Type RM Length L Ch R = 1 ,2551.299,47.165,49.353,50.132
BEGIN DESCRIPTION:
Interpolated Section
END DESCRIPTION:
Node Name=BB22a
XS GIS Cut Line= 2
299296.470358839 5379518.4881891299222.0654506495379485.91949263
#Sta/Elev= 24
  23.057  16.474  32.526  16.387  35.339  16.441  44.727  16.468  45.481  16.443
  50.638  15.188  55.248  13.242  56.527  12.916  58.401  12.519   61.76   12.02
   63.93   11.88   67.64   11.86   71.18   11.96  72.882  12.216  73.132  12.242
  80.241  13.676  80.964  13.758  84.448  13.486  85.693  13.453  87.983  13.409
  91.206  13.524  93.844  14.721  96.721  14.913 104.278  14.941
#Mann= 3 , 0 , 0
  23.057     .06       0  50.638     .05       0  80.964     .06       0
Levee=0,,,-1,81.06,13.74,,
Bank Sta=50.638,80.964
XS Rating Curve= 0 ,0
Exp/Cntr=0.3,0.1

Type RM Length L Ch R = 1 ,2501.946,48.982,48.999,49.706
BEGIN DESCRIPTION:
2008 Survey Section
END DESCRIPTION:
Node Name=BB22
XS GIS Cut Line= 2
299310.7872617965379497.53829081299243.5765624745379436.66460028
#Sta/Elev= 22
   36.65   15.98   45.14   15.76   56.08   16.19   61.38   15.96   66.66   13.56
   72.43   11.51   74.78   11.55   76.41    11.4   77.72   11.35   79.02   11.36
   79.89   11.46    81.3   11.61   82.92   11.97   93.33   12.21   99.35    11.6
  102.17   11.58  104.13   11.51  105.65   11.61  108.84   11.66  112.57   14.12
  116.64   14.51  127.33   14.55
#Mann= 3 , 0 , 0
   36.65     .06       0   61.38     .05       0  116.64     .06       0
Levee=-1,56.26,16.18,0,,,,
Bank Sta=61.38,116.64
XS Rating Curve= 0 ,0
Exp/Cntr=0.3,0.1

Type RM Length L Ch R = 1 ,2452.947,38.657,40.37,41.644
BEGIN DESCRIPTION:
Interpolated Section
END DESCRIPTION:
Node Name=BB21a
XS GIS Cut Line= 3
299333.1367144015379478.42671757299293.0598857775379414.16559581
299237.8935478975379325.70922645
#Sta/Elev= 28
  24.924  15.519  33.683   15.03  35.156   14.99   44.97  15.042   48.04  14.947
  50.437  14.303  50.849  14.118  55.885  12.277  56.643  12.033   61.39   11.15
   63.39   10.98   66.65   10.93   69.46   10.94  71.067   11.19  75.158  11.453
  78.003  12.038  81.968  12.508  83.056  12.693  85.299  12.639  88.338  12.731
  90.823  13.833  93.535  13.999 100.658  13.991 192.907      13 195.907    14.5
 197.407    14.5 198.907    14.5 204.907      13
#Mann= 3 , 0 , 0
  24.924     .06       0   48.04     .05       0  90.823     .06       0
Levee=0,,,-1,195.8,14.46,,
Bank Sta=48.04,90.823
XS Rating Curve= 0 ,0
Exp/Cntr=0.3,0.1

Type RM Length L Ch R = 1 ,2412.578,58.965,57.021,55.229
BEGIN DESCRIPTION:
2008 Survey Section
END DESCRIPTION:
Node Name=BB21
XS GIS Cut Line= 2
299355.9413159975379458.91732217299335.9667231285379398.72542823
#Sta/Elev= 13
  48.389   15.14  58.879   14.31  72.089   14.03  74.969   12.75  80.909   10.99
   85.29   10.76  87.789   10.42   90.36   10.46  92.719   10.29   94.13   10.74
  96.829   10.91 101.469   13.65 111.809   13.53
#Mann= 3 , 0 , 0
  48.389     .06       0  72.089     .05       0 101.469     .06       0
Levee=0,,,-1,101.45,13.74,,
Bank Sta=72.089,101.469
XS Rating Curve= 0 ,0
Exp/Cntr=0.3,0.1

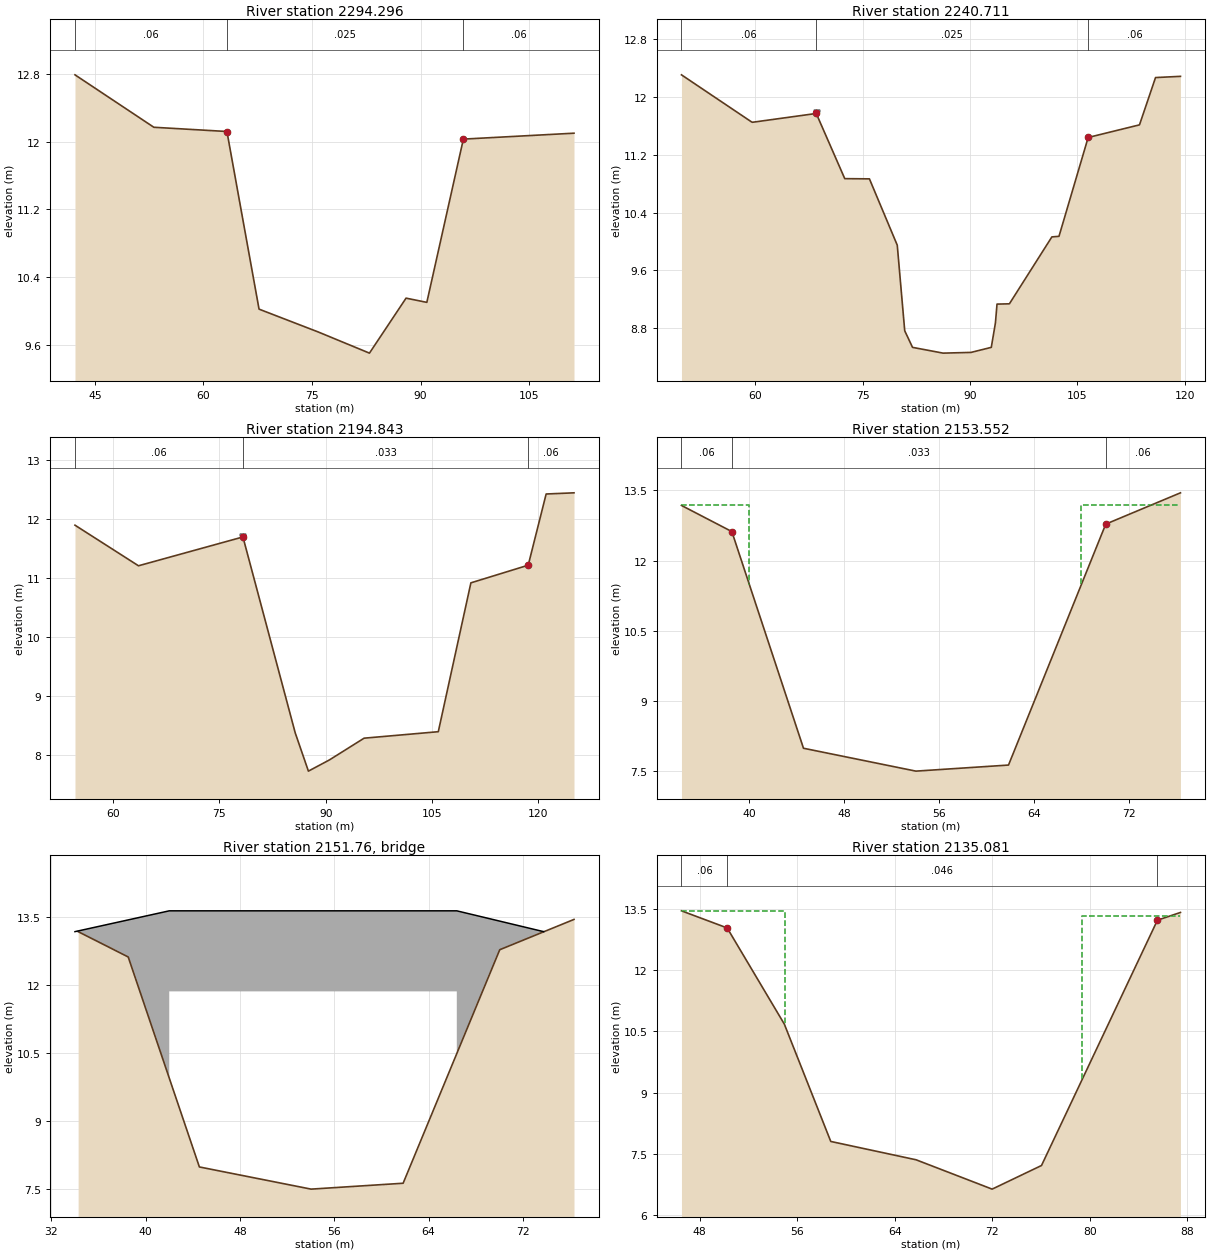
Type RM Length L Ch R = 1 ,2294.296,55.328,53.585,51.797
BEGIN DESCRIPTION:
2008 Survey Section
END DESCRIPTION:
Node Name=BB20
XS GIS Cut Line= 2
299475.8415631235379383.70187447299419.2919906735379344.21755761
#Sta/Elev= 10
  42.241   12.79  53.141   12.17  63.241   12.12  67.681   10.02  75.861    9.75
  82.941     9.5  88.001   10.15  90.871    10.1  95.921   12.03 111.211    12.1
#Mann= 3 , 0 , 0
  42.241     .06       0  63.241    .025       0  95.921     .06       0
Bank Sta=63.241,95.921
XS Rating Curve= 0 ,0
Exp/Cntr=0.3,0.1

Type RM Length L Ch R = 1 ,2240.711,47.275,45.868,43.163
BEGIN DESCRIPTION:
Interpolated Section
END DESCRIPTION:
Node Name=BB19a
XS GIS Cut Line= 2
299498.0517355245379324.77532383299432.6901053495379300.42003958
#Sta/Elev= 21
  49.661   12.31  59.442  11.658  59.595  11.652  68.504  11.774  72.488   10.87
  75.936  10.867  79.827   9.947   80.87    8.76   81.96    8.53   86.23    8.45
   90.14    8.46   92.97    8.53   93.55    8.87   93.77    9.13  95.502   9.134
 101.439  10.062 102.433   10.07 106.511  11.441 113.685  11.616 115.928  12.272
 119.413  12.289
#Mann= 3 , 0 , 0
  49.661     .06       0  68.504    .025       0 106.511     .06       0
Levee=-1,68.55,11.78,0,,,,
Bank Sta=68.504,106.511
XS Rating Curve= 0 ,0
Exp/Cntr=0.3,0.1

Type RM Length L Ch R = 1 ,2194.843,20.394,20.418,20.397
BEGIN DESCRIPTION:
2008 Survey Section
END DESCRIPTION:
Node Name=BB19
XS GIS Cut Line= 3
 299517.90990038 5379272.0366088299447.815151001  5379267.099045
  299447.66412915379267.08840682
#Sta/Elev= 12
  54.609    11.9  63.569   11.21  78.309    11.7  85.689    8.37  87.549    7.72
  90.509    7.91  95.409    8.28 105.879    8.39 110.479   10.92 118.569   11.22
 121.099   12.43 125.029   12.45
#Mann= 3 , 0 , 0
  54.609     .06       0  78.309    .033       0 118.569     .06       0
Levee=-1,78.33,11.7,0,,,,
Bank Sta=78.309,118.569
XS Rating Curve= 0 ,0
Exp/Cntr=0.3,0.1

Type RM Length L Ch R = 1 ,2153.552,17.891,18.471,17.928
BEGIN DESCRIPTION:
2008 Survey Section
END DESCRIPTION:
Node Name=BB18
XS GIS Cut Line= 2
299492.3074642465379231.14339987299450.9894636985379223.16975064
#Sta/Elev= 7
  34.266   13.18  38.516   12.62  44.556    7.98  54.036    7.49  61.846    7.62
  70.046   12.78  76.346   13.45
#Mann= 3 , 0 , 0
  34.266     .06       0  38.516    .033       0  70.046     .06       0
#XS Ineff= 2 , 0
       0      40   13.18      68       0   13.18
Permanent Ineff=
       F       F
Bank Sta=38.516,70.046
XS Rating Curve= 0 ,0
Exp/Cntr=0.5,0.3

Type RM Length L Ch R = 3 ,2151.76 ,,,
BEGIN DESCRIPTION:
Main Street Bridge
END DESCRIPTION:
Bridge Culvert--1,0,-1,-1, 0
Deck Dist Width WeirC Skew NumUp NumDn MinLoCord MaxHiCord MaxSubmerge Is_Ogee
1.79,16.52,1.6,0, 6, 6, , , 0.98, 0, 1,1,,
      34      42      42    66.4    66.4   73.77
   13.18   13.64   13.64   13.64   13.64   13.18
       0       0   11.86   11.86       0       0
      34      55      55    79.4    79.4      90
   13.64   13.64   13.64   13.64   13.64   13.18
       0       0   11.86   11.86       0       0
BR Coef=-1 , 0 , 0 ,, 0 ,,,0.8,-1,,0,
WSPro=,,,, 1 ,,,, 0 ,,,, 0 ,,,,-1 ,-1 ,-1 , 0 , 0 , 0 , 0 , 0
BC Design=,, 0 ,, 0 ,,,,,,
BC Use User HTab Curves=0
BC User HTab FreeFlow(D)= 0

Type RM Length L Ch R = 1 ,2135.081,15.08,16.997,18.315
BEGIN DESCRIPTION:
2008 Survey Section
END DESCRIPTION:
Node Name=BB17
XS GIS Cut Line= 3
299496.4254602915379214.64401857 299423.53082417 5379198.9436354
299423.4056953135379198.91668457
#Sta/Elev= 9
  46.502   13.46  50.252   13.04  54.942   10.68  58.752     7.8  65.752    7.35
  71.992    6.63  76.042    7.21  85.552   13.23  87.442   13.42
#Mann= 3 , 0 , 0
  46.502     .06       0  50.252    .046       0  85.552     .06       0
#XS Ineff= 2 , 0
       0      55   13.46    79.4       0   13.33
Permanent Ineff=
       F       F
Bank Sta=50.252,85.552
XS Rating Curve= 0 ,0
Exp/Cntr=0.5,0.3

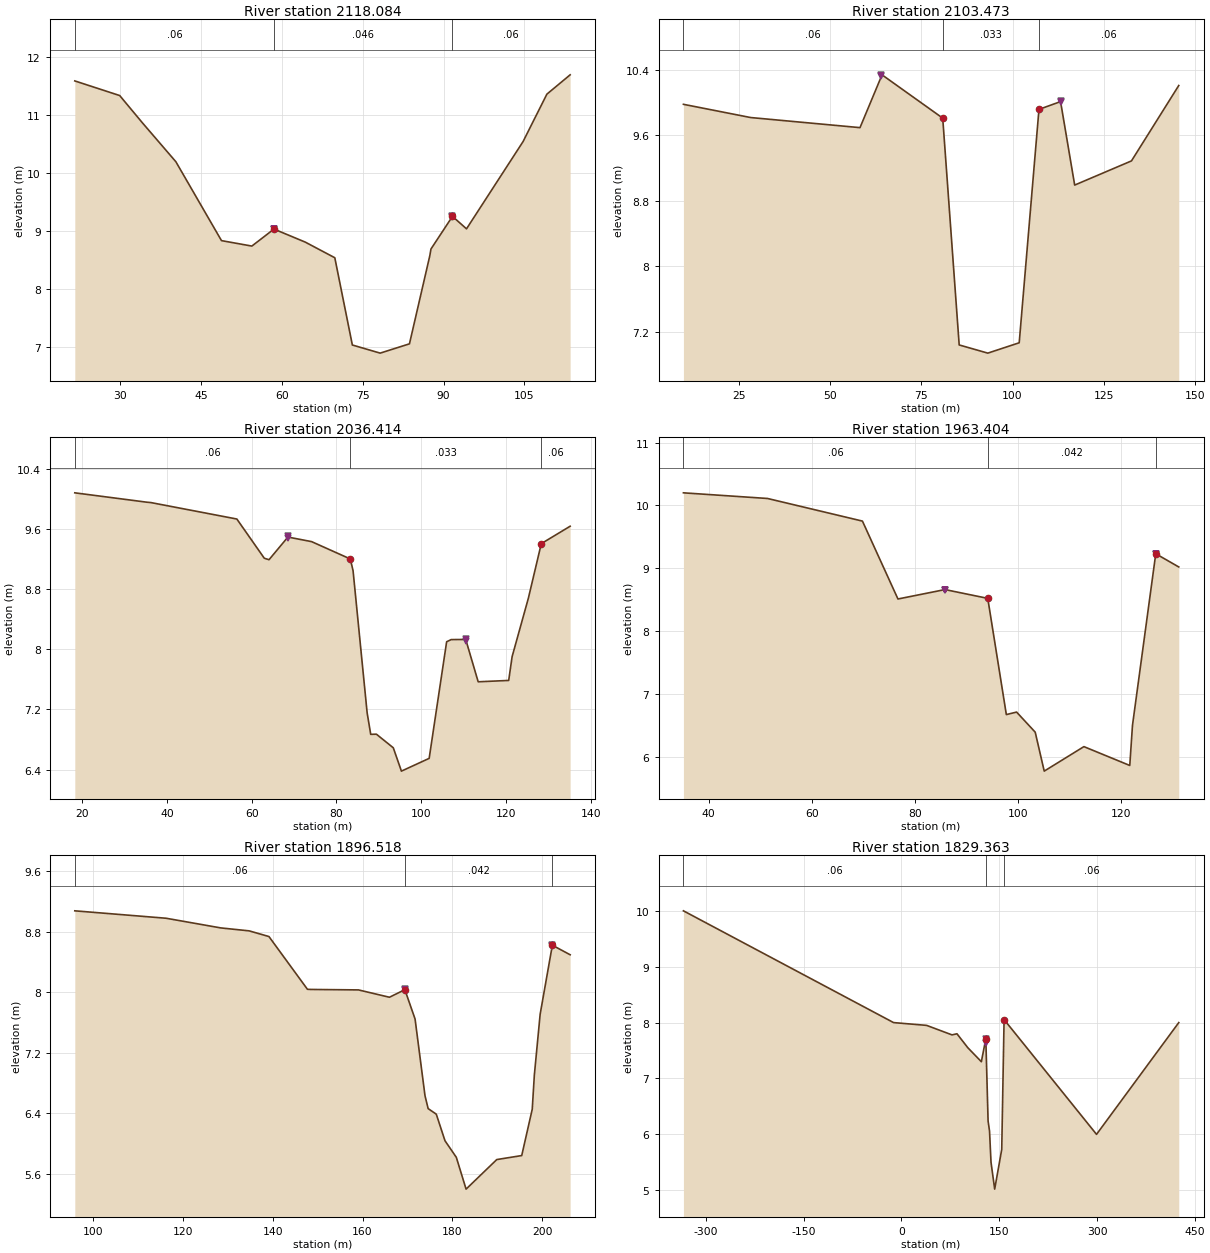
Type RM Length L Ch R = 1 ,2118.084,13.884,14.611,14.929
BEGIN DESCRIPTION:
Interpolated Section
END DESCRIPTION:
Node Name=BB16a
XS GIS Cut Line= 2
299534.9270052745379217.40501632299436.0913379175379177.61947227
#Sta/Elev= 19
  21.564  11.589  29.898  11.337  34.077  10.871  40.321  10.197  48.789   8.838
  54.427   8.744  58.529   9.037  64.346   8.812  69.824   8.543   73.08    7.04
   78.24     6.9   83.68    7.06  87.465   8.581   87.67   8.693  91.663   9.256
   94.27   9.041 104.767  10.544 109.188  11.361 113.505  11.694
#Mann= 3 , 0 , 0
  21.564     .06       0  58.529    .046       0  91.663     .06       0
Levee=-1,58.5,9.04,-1,91.63,9.26,,
Bank Sta=58.529,91.663
XS Rating Curve= 0 ,0
Exp/Cntr=0.3,0.1

Type RM Length L Ch R = 1 ,2103.473,62.135,67.06,69.219
BEGIN DESCRIPTION:
2008 Survey Section
END DESCRIPTION:
Node Name=BB16
XS GIS Cut Line= 2
299560.8505432135379219.22100146299431.1658399995379155.81049989
#Sta/Elev= 13
   9.798  9.9811  28.225  9.8193  58.194  9.6958  64.235 10.3417  80.869   9.812
  85.381  7.0383  93.224  6.9383  101.83  7.0648 107.248  9.9192  113.17 10.0143
 117.036  8.9934 132.605  9.2891 145.565 10.2111
#Mann= 3 , 0 , 0
   9.798     .06       0  80.869    .033       0 107.248     .06       0
Levee=-1,64.06,10.34,-1,113.2,10.02,,
Bank Sta=80.869,107.248
XS Rating Curve= 0 ,0
Exp/Cntr=0.3,0.1

Type RM Length L Ch R = 1 ,2036.414,63.11,73.01,76.529
BEGIN DESCRIPTION:
Interpolated Section
END DESCRIPTION:
Node Name=BB15a
XS GIS Cut Line= 3
299576.286576624 5379193.2462929299457.8118981535379056.50459352
 299446.734296345379043.71899143
#Sta/Elev= 25
  18.288  10.086  35.306   9.961  36.247   9.956  56.514   9.737  62.983   9.215
  64.098   9.195  68.562   9.497  74.144   9.436  83.277   9.205  83.924   9.049
  87.245   7.156  88.091   6.869  89.432   6.871  93.411    6.69  95.334   6.379
 101.878   6.549 105.997   8.102 107.072   8.131   110.5   8.133 113.439   7.569
 120.637   7.587 121.444   7.904 125.277   8.682 128.326   9.409 135.131   9.641
#Mann= 3 , 0 , 0
  18.288     .06       0  83.277    .033       0 128.326     .06       0
Levee=-1,68.46,9.51,-1,110.58,8.14,,
Bank Sta=83.277,128.326
XS Rating Curve= 0 ,0
Exp/Cntr=0.3,0.1

Type RM Length L Ch R = 1 ,1963.404,73.311,66.886,63.087
BEGIN DESCRIPTION:
2008 Survey Section
END DESCRIPTION:
Node Name=BB15
XS GIS Cut Line= 2
299607.3590964275379171.46521768 299574.641529385379050.81918919
#Sta/Elev= 15
  35.074    10.2  51.414   10.11  69.854    9.75  76.754    8.51  85.894    8.66
  94.204    8.52  97.814    6.67  99.804    6.71 103.424    6.39 105.174    5.77
 112.884    6.16 121.794    5.86 122.324     6.5 126.844    9.23 131.314    9.02
#Mann= 3 , 0 , 0
  35.074     .06       0  94.204    .042       0 126.844     .06       0
Levee=-1,85.97,8.66,-1,126.85,9.23,,
Bank Sta=94.204,126.844
XS Rating Curve= 0 ,0
Exp/Cntr=0.3,0.1

Type RM Length L Ch R = 1 ,1896.518,77.456,67.155,64.169
BEGIN DESCRIPTION:
Interpolated Section
END DESCRIPTION:
Node Name=BB14a
XS GIS Cut Line= 2
299683.0450958425379150.14230296299615.5339537075379011.49038739
#Sta/Elev= 25
  95.913   9.077 116.225   8.979 128.421   8.851  134.74   8.812 139.148   8.737
 147.726   8.039 148.666   8.037 159.088   8.031 165.986   7.934 169.418   8.034
 171.695   7.646 173.906   6.632 174.604   6.461 176.379   6.389 176.443   6.383
 178.357   6.036 180.879   5.817 183.055   5.396  189.89   5.787 195.446    5.84
  197.79   6.453  198.26   6.906 199.553    7.71 202.267   8.622  206.23   8.496
#Mann= 3 , 0 , 0
  95.913     .06       0 169.418    .042       0 202.267     .06       0
Levee=-1,169.43,8.04,-1,202.25,8.62,,
Bank Sta=169.418,202.267
XS Rating Curve= 0 ,0
Exp/Cntr=0.3,0.1

Type RM Length L Ch R = 1 ,1829.363,25.942,26.793,25.989
BEGIN DESCRIPTION:
2008 Survey Section
END DESCRIPTION:
Node Name=BB14
XS GIS Cut Line= 4
 300018.941218095379405.12798696299775.1360805385379123.25360864
299683.6317775725379017.46125836299512.3234784755378819.40382285
#Sta/Elev= 17
    -334      10     -12       8  38.685    7.95  77.575    7.78  85.135     7.8
 101.795    7.55 122.515     7.3 129.345    7.71 132.825    6.24 135.025    6.06
 137.315     5.5 142.935    5.02 153.735    5.73 157.315    8.04 163.135    7.97
     299       6     425       8
#Mann= 3 , 0 , 0
    -334     .06       0 129.345    .033       0 157.315     .06       0
Levee=-1,129.53,7.71,0,,,,
Bank Sta=129.345,157.315
XS Rating Curve= 0 ,0
Exp/Cntr=0.3,0.1

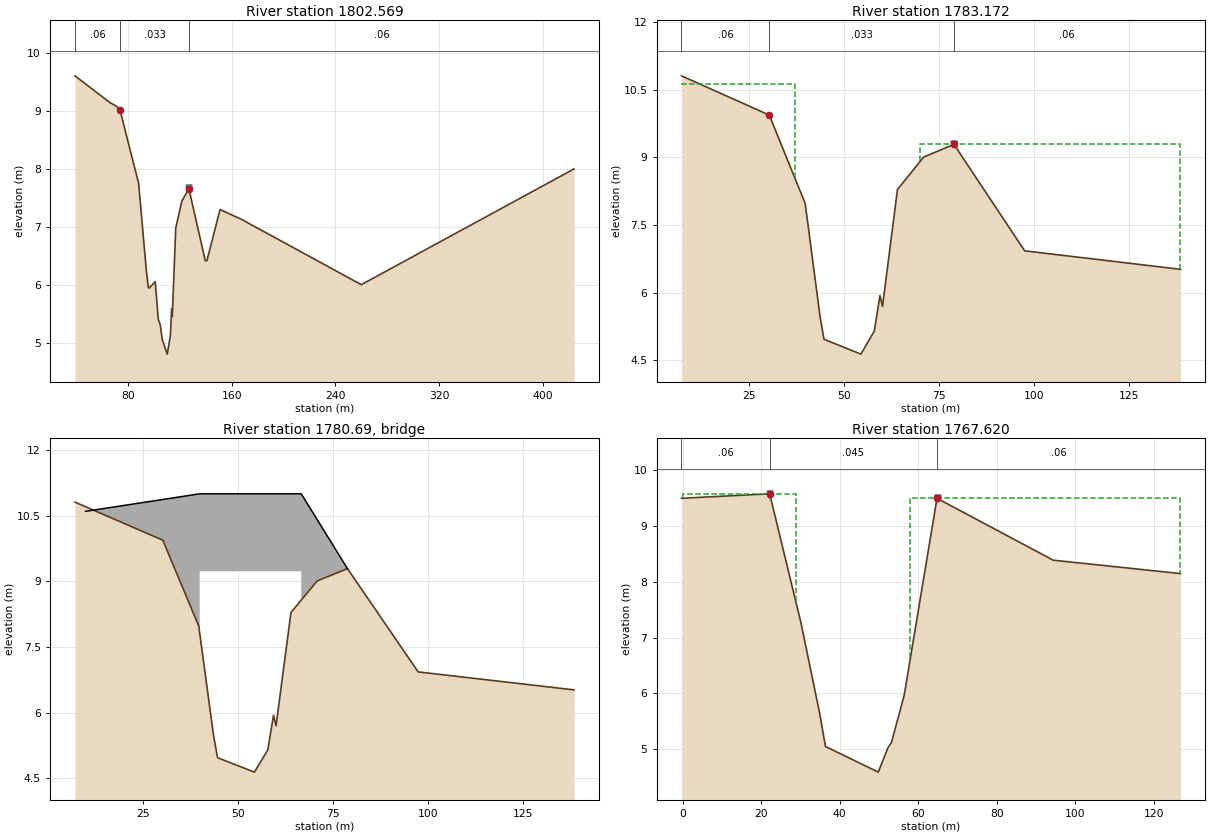
Type RM Length L Ch R = 1 ,1802.569,18.545,19.397,20.067
BEGIN DESCRIPTION:
Interpolated Section
END DESCRIPTION:
Node Name=BB13a
XS GIS Cut Line= 3
299770.3005188575379077.14364587 299647.980331885378938.98585892
299477.9950323325378746.99144345
#Sta/Elev= 26
   39.21   9.609   65.75   9.153  70.909   9.086  74.035   9.012  82.278   8.278
  88.273   7.755  94.125   6.267  95.724   5.954  96.418    5.94 101.079   6.051
 103.454   5.402 104.956   5.307 106.518   5.051 110.354     4.8 112.758   5.119
 113.772   5.587 114.228   5.452 116.905    6.98 121.603   7.444 127.017   7.659
 139.676   6.414 140.944   6.415 151.084   7.299 167.569   7.129     260       6
     424       8
#Mann= 3 , 0 , 0
   39.21     .06       0  74.035    .033       0 127.017     .06       0
Levee=0,,,-1,127.25,7.67,,
Bank Sta=74.035,127.017
XS Rating Curve= 0 ,0
Exp/Cntr=0.3,0.1

Type RM Length L Ch R = 1 ,1783.172,15.654,15.552,15.894
BEGIN DESCRIPTION:
2008 Survey Section
END DESCRIPTION:
Node Name=BB13
XS GIS Cut Line= 3
299767.7410278315379048.98009851299675.7161904865378932.64681357
299621.7735092465378864.45512219
#Sta/Elev= 14
    7.22   10.81   30.31    9.94   39.75    7.98   43.63    5.49   44.69    4.97
   54.39    4.64   57.92    5.15   59.41    5.94   60.08     5.7   64.01    8.29
   70.91    9.01   78.86    9.29   97.45    6.93  138.41    6.52
#Mann= 3 , 0 , 0
    7.22     .06       0   30.31    .033       0   78.86     .06       0
Levee=0,,,-1,78.94,9.29,,
#XS Ineff= 2 , 0
       0      37   10.63      70       0    9.29
Permanent Ineff=
       F       F
Bank Sta=30.31,78.86
XS Rating Curve= 0 ,0
Exp/Cntr=0.5,0.3

Type RM Length L Ch R = 3 ,1780.69 ,,,
BEGIN DESCRIPTION:
Minnesota Drive Bridge
END DESCRIPTION:
Bridge Culvert--1,0,-1,-1, 0
Deck Dist Width WeirC Skew NumUp NumDn MinLoCord MaxHiCord MaxSubmerge Is_Ogee
2.48,11.33,1.6,0, 6, 6, , , 0.98, 0, 1,1,,
      10      40      40    66.7    66.7   78.86
    10.6      11      11      11      11    9.29
       0       0    9.23    9.23       0       0
      10      30      30    56.7    56.7      78
    9.54      11      11      11      11    9.02
       0       0    9.23    9.23       0       0
BR Coef=-1 , 0 , 0 ,, 0 ,,,0.8,-1,,0,
WSPro=,,,, 1 ,,,, 0 ,,,, 0 ,,,,-1 ,-1 ,-1 , 0 , 0 , 0 , 0 , 0
BC Design=,, 0 ,, 0 ,,,,,,
BC Use User HTab Curves=0
BC User HTab FreeFlow(D)= 0

Type RM Length L Ch R = 1 ,1767.620,17.554,40.58,15.484
BEGIN DESCRIPTION:
2008 Survey Section
END DESCRIPTION:
Node Name=BB12
XS GIS Cut Line= 4
  299780.36883335379040.20944591   299780.192571  5379039.984218
299702.147574001  5378940.258348299702.0489681715378940.13234951
#Sta/Elev= 12
   -.286     9.5  22.184    9.58  30.134    7.27  34.894    5.65  36.384    5.05
  49.834    4.59  52.314    5.03  53.194    5.12  56.444    5.97  64.794     9.5
  94.384    8.39 126.794    8.15
#Mann= 3 , 0 , 0
   -.286     .06       0  22.184    .045       0  64.794     .06       0
Levee=-1,22.32,9.58,-1,64.93,9.5,,
#XS Ineff= 2 , 0
       0      29    9.58      58       0     9.5
Permanent Ineff=
       F       F
Bank Sta=22.184,64.794
XS Rating Curve= 0 ,0
Exp/Cntr=0.5,0.3

River Reach=Warm Creek      ,DS of Noels Pond

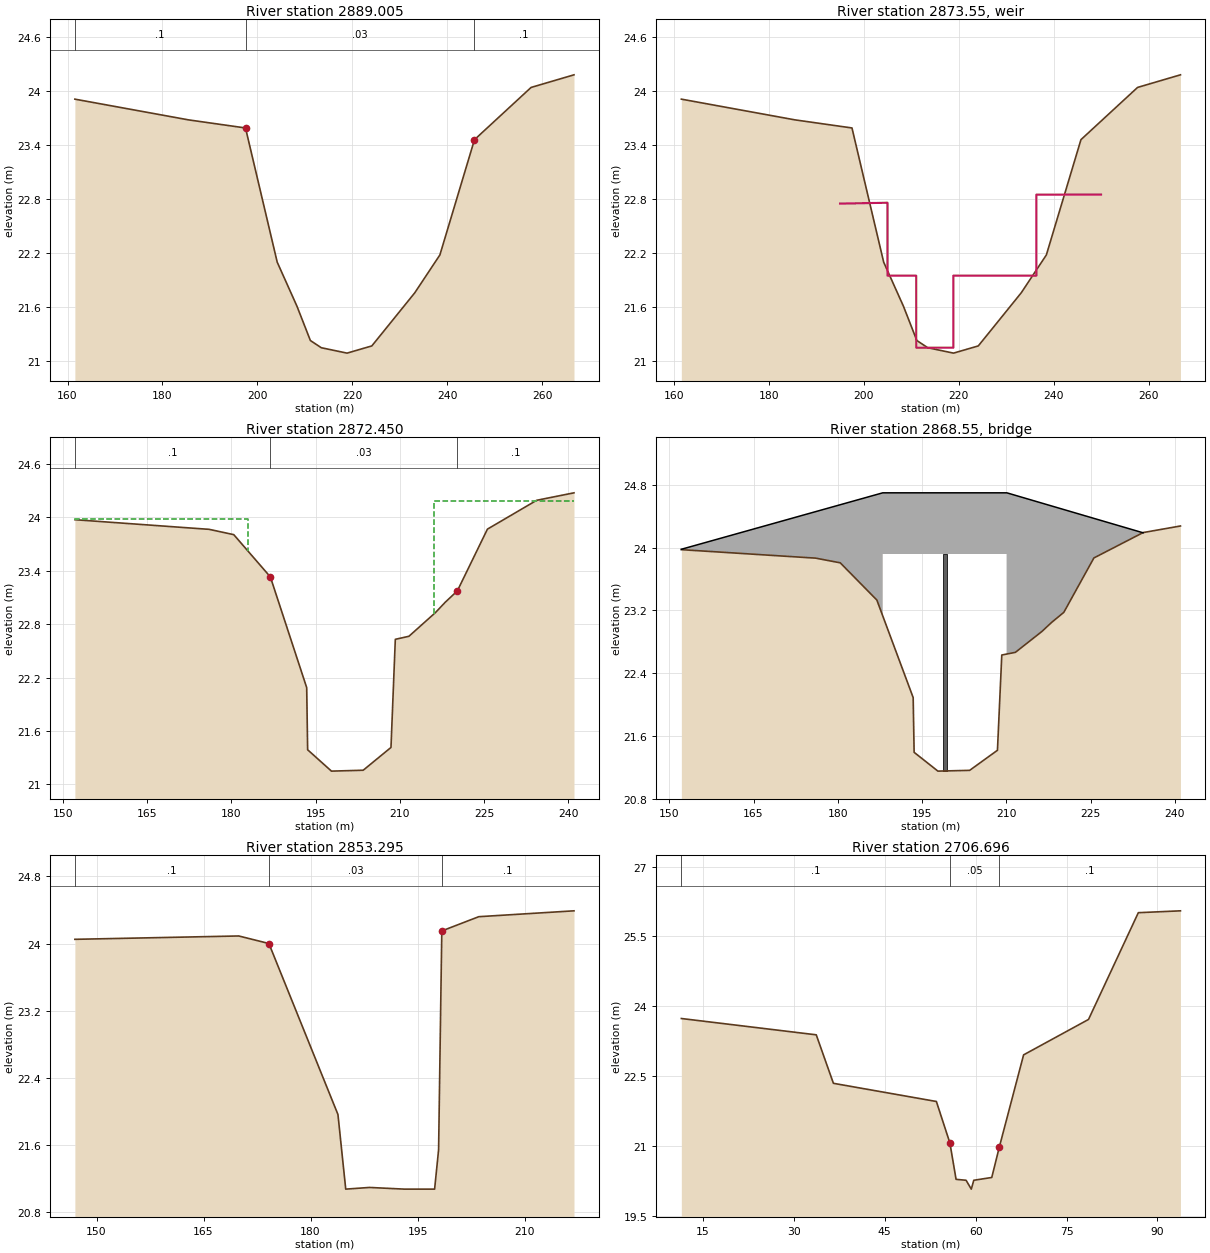
Type RM Length L Ch R = 1 ,2889.005,22.271,16.555,15.405
BEGIN DESCRIPTION:
2008 Survey Section
END DESCRIPTION:
Node Name=W23
XS GIS Cut Line= 2
301312.9991003265380088.10282464301266.6327960865380182.51132364
#Sta/Elev= 15
 161.553   23.91 185.483   23.68 197.513   23.59 204.193    22.1 208.363   21.61
 211.183   21.23  213.48   21.15  218.91   21.09  224.13   21.17 226.743   21.34
 233.183   21.76 238.473   22.18 245.763   23.46 257.693   24.04 266.733   24.18
#Mann= 3 , 0 , 0
 161.553      .1       0 197.513     .03       0 245.763      .1       0
Bank Sta=197.513,245.763
XS Rating Curve= 0 ,0
Exp/Cntr=0.3,0.1

Type RM Length L Ch R = 5 ,2873.55 ,,,
BEGIN DESCRIPTION:
Noel's Pond Outlet Weir
END DESCRIPTION:
IW Pilot Flow=0
#Inline Weir SE= 10
     195   22.75     205   22.76     205   21.95  211.05   21.95  211.05   21.15
  218.87   21.15  218.87   21.95  236.37   21.95  236.37   22.85     250   22.85
IW Dist,WD,Coef,Skew,MaxSub,Min_El,Is_Ogee,SpillHt,DesHd
15.46,0.5,1.7,0,0.98,, 0 ,,,0,1,

Type RM Length L Ch R = 1 ,2872.450,25.056,19.156,18.179
BEGIN DESCRIPTION:
Interpolated Section
END DESCRIPTION:
Node Name=W22a
XS GIS Cut Line= 2
301290.7424411895380089.00876538301256.8044458955380171.12447428
#Sta/Elev= 18
 152.153  23.975 175.314   23.87 176.041  23.867 180.439  23.807 186.957  23.332
 193.423  22.088  193.59   21.39  197.83   21.15  203.48   21.16 208.427  21.416
 209.199  22.631 211.621  22.665 216.353  22.932 218.091  23.048  220.24  23.175
 225.597  23.869 234.363  24.193 241.006  24.277
#Mann= 3 , 0 , 0
 152.153      .1       0 186.957     .03       0  220.24      .1       0
#XS Ineff= 2 , 0
       0     183   23.98     216       0   24.19
Permanent Ineff=
       F       F
Bank Sta=186.957,220.24
XS Rating Curve= 0 ,0
Exp/Cntr=0.5,0.3

Type RM Length L Ch R = 3 ,2868.55 ,,,
BEGIN DESCRIPTION:
Noel's Pond Outlet Bridge
END DESCRIPTION:
Bridge Culvert--1,0,-1,-1, 0
Deck Dist Width WeirC Skew NumUp NumDn MinLoCord MaxHiCord MaxSubmerge Is_Ogee
5,8.25,1.6,0, 6, 6, , , 0.98, 0, 1,1,,
  152.15     188     188   210.1   210.1  234.36
   23.98    24.7    24.7    24.7    24.7   24.19
       0       0   23.92   23.92       0       0
  146.96     176     176   198.1   198.1  216.93
   24.05    24.7    24.7    24.7    24.7   24.39
       0       0   23.92   23.92       0       0
Pier Skew, UpSta & Num, DnSta & Num=  ,199.07, 2 ,187.07, 2 , 0 , 0 , 0 ,,
     .74     .74
       0   23.92
     .74     .74
       0   23.92
BR Coef=-1 , 0 , 0 ,, 0 ,,,0.8,-1,,0,
WSPro=,,,, 1 ,,,, 0 ,,,, 0 ,,,,-1 ,-1 ,-1 , 0 , 0 , 0 , 0 , 0
BC Design=,, 0 ,, 0 ,,,,,,
BC Use User HTab Curves=0
BC User HTab FreeFlow(D)= 0

Type RM Length L Ch R = 1 ,2853.295,62.32,146.599,163.025
BEGIN DESCRIPTION:
2008 Survey Section
END DESCRIPTION:
Node Name=W22
XS GIS Cut Line= 2
 301265.992856035380090.46296967301244.8021192545380157.14710638
#Sta/Elev= 12
 146.959   24.05 169.929   24.09 174.159      24  183.84   21.96  184.93   21.07
  188.26   21.09 193.149   21.07  197.39   21.07 197.949   21.54 198.399   24.15
 203.579   24.32 216.929   24.39
#Mann= 3 , 0 , 0
 146.959      .1       0 174.159     .03       0 198.399      .1       0
Bank Sta=174.159,198.399
XS Rating Curve= 0 ,0
Exp/Cntr=0.5,0.3

Type RM Length L Ch R = 1 ,2706.696,280.29,270.077,227.593
BEGIN DESCRIPTION:
2008 Survey Section
END DESCRIPTION:
Node Name=W21
XS GIS Cut Line= 2
301240.8198410325380086.71513002301170.0227037365380044.65228316
#Sta/Elev= 15
  11.439   23.74  33.699   23.39  36.529   22.35  53.519   21.96  55.749   21.07
  56.768   20.29   58.42   20.27  59.279   20.08   59.69   20.27  62.658   20.33
  63.899   20.98  67.909   22.96  78.619   23.72  86.839   26.01  93.789   26.05
#Mann= 3 , 0 , 0
  11.439      .1       0  55.749     .05       0  63.899      .1       0
Bank Sta=55.749,63.899
XS Rating Curve= 0 ,0
Exp/Cntr=0.3,0.1

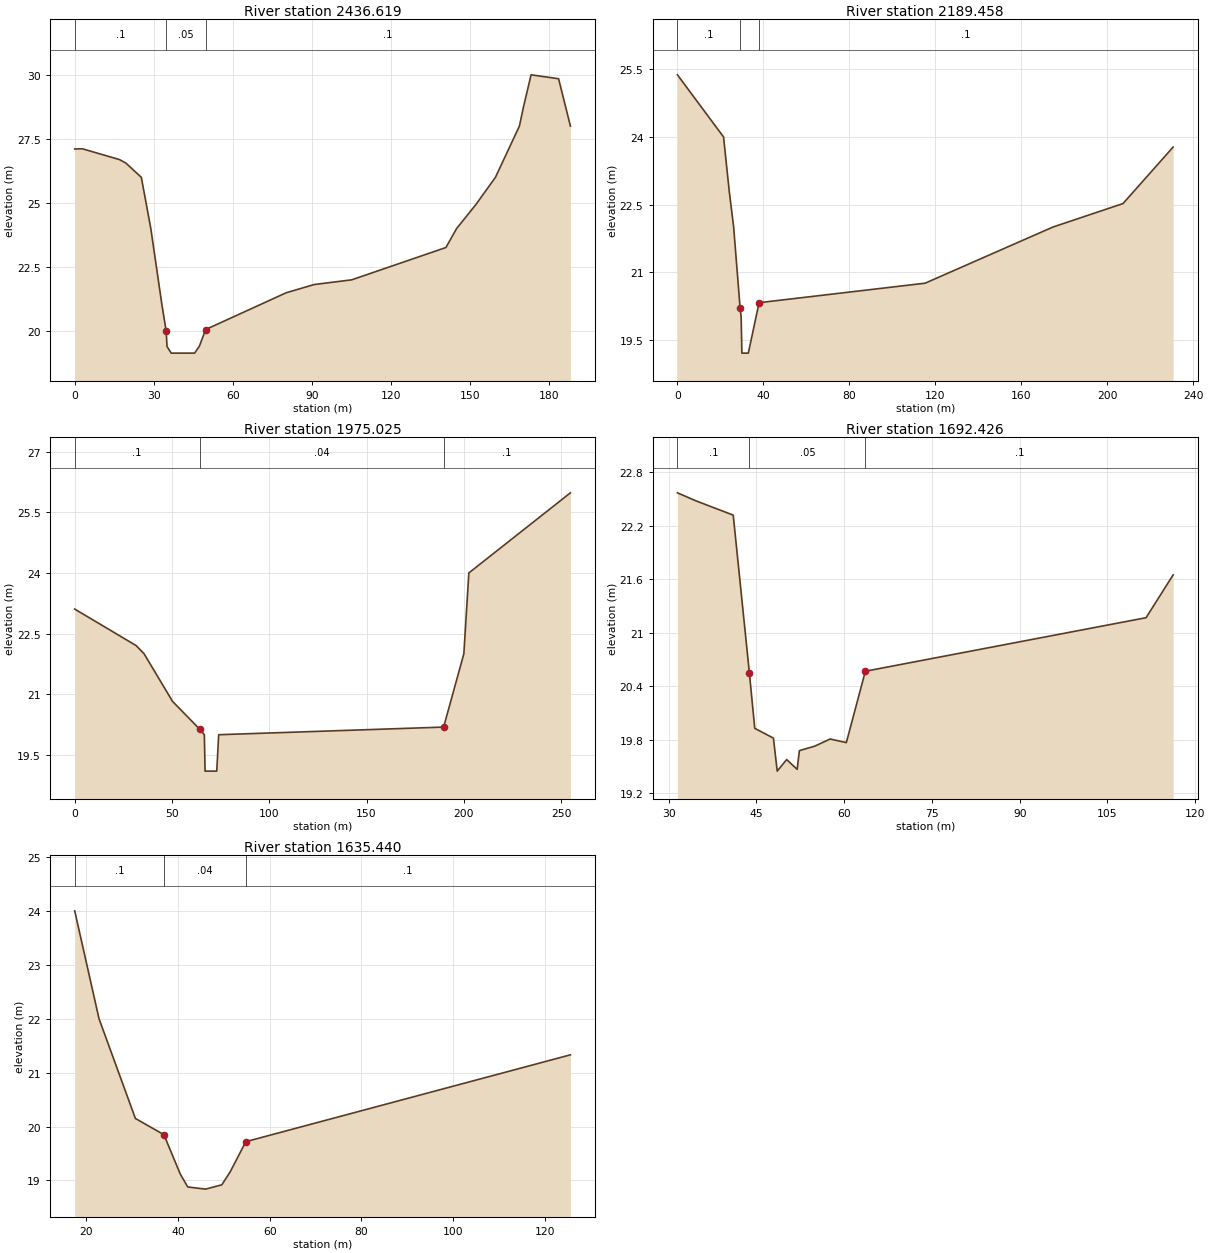
Type RM Length L Ch R = 1 ,2436.619,240.8,247.162,196.133
BEGIN DESCRIPTION:
1:2500 Community Mapping Section
END DESCRIPTION:
Node Name=W17d
XS GIS Cut Line= 5
301285.261793047 5379792.0819097301256.3901449445379808.20191322
301181.6138240435379849.95202573301164.1513104015379859.70192918
301101.3674640025379894.75624342
#Sta/Elev= 25
       0  27.104   2.885  27.115  16.972  26.693  19.403  26.557  25.264      26
  28.865      24  33.092  21.011  34.693      20      35    19.4   36.59   19.14
   45.47   19.14   47.28   19.41   49.64   20.06  80.203  21.496  90.826  21.817
 105.025      22 140.753  23.261 144.796      24 152.108  24.937 159.534      26
 168.622      28 170.209  28.767 173.052      30 183.477  29.848 187.963      28
#Mann= 3 , 0 , 0
       0      .1       0  34.693     .05       0   49.64      .1       0
Bank Sta=34.693,49.64
XS Rating Curve= 0 ,0
Exp/Cntr=0.3,0.1

Type RM Length L Ch R = 1 ,2189.458,205.74,214.433,169.067
BEGIN DESCRIPTION:
1:2500 Community Mapping Section
END DESCRIPTION:
Node Name=W17c
XS GIS Cut Line= 5
301110.5621804555379618.14852348301097.8412540975379641.72226813
 301065.276012115379702.07044384301058.1526354465379715.27110689
301000.991809398 5379821.1985118
#Sta/Elev= 13
       0   25.38  21.479      24  24.096  22.803  26.172      22   29.15  20.213
  29.661      20      30    19.2      33    19.2      38   20.32 115.294  20.753
 174.782      22 207.388  22.521 230.727  23.776
#Mann= 3 , 0 , 0
       0      .1       0   29.15     .04       0      38      .1       0
Bank Sta=29.15,38
XS Rating Curve= 0 ,0
Exp/Cntr=0.3,0.1

Type RM Length L Ch R = 1 ,1975.025,192.041,193.482,126.262
BEGIN DESCRIPTION:
1:2500 Community Mapping Section
END DESCRIPTION:
Node Name=W17b
XS GIS Cut Line= 4
300903.6810602775379507.81192605300900.2054420385379571.91777357
300895.6535312825379655.87523864  300889.88898565379762.19908123
#Sta/Elev= 13
       0  23.107   31.56  22.204  35.677      22  50.261  20.826    64.2  20.138
  66.628      20      67    19.1      73    19.1      74      20 189.606  20.189
 199.988      22 202.569      24 254.761   25.98
#Mann= 3 , 0 , 0
       0      .1       0    64.2     .04       0 189.606      .1       0
Bank Sta=64.2,189.606
XS Rating Curve= 0 ,0
Exp/Cntr=0.3,0.1

Type RM Length L Ch R = 1 ,1692.426,55.271,56.986,58.395
BEGIN DESCRIPTION:
2008 Survey Section
END DESCRIPTION:
Node Name=W17
XS GIS Cut Line= 2
300698.6916769585379734.14148137300700.3620475935379818.87482816
#Sta/Elev= 16
  31.486   22.57  34.656   22.48  41.026   22.32   43.79   20.55  44.706   19.93
    47.9   19.82  48.546   19.45   50.16   19.58  51.956   19.47   52.34   19.68
  54.966   19.73   57.59   19.81  60.366   19.77  63.616   20.57 111.606   21.17
 116.236   21.65
#Mann= 3 , 0 , 0
  31.486      .1       0   43.79     .05       0  63.616      .1       0
Bank Sta=43.79,63.616
XS Rating Curve= 0 ,0
Exp/Cntr=0.3,0.1

Type RM Length L Ch R = 1 ,1635.440,99.483,101.822,103.873
BEGIN DESCRIPTION:
2008 Survey Section
END DESCRIPTION:
Node Name=W16
XS GIS Cut Line= 3
300644.5963847925379723.98834471300643.7766037925379737.19592749
300637.9019106085379831.84376211
#Sta/Elev= 11
    17.5      24    22.8      22  30.733   20.15  36.943   19.85  40.513   19.12
  42.143   18.88  46.033   18.84   49.57   18.92  51.393   19.16  54.803   19.72
 125.563   21.33
#Mann= 3 , 0 , 0
    17.5      .1       0  36.943     .04       0  54.803      .1       0
Bank Sta=36.943,54.803
XS Rating Curve= 0 ,0
Exp/Cntr=0.3,0.1