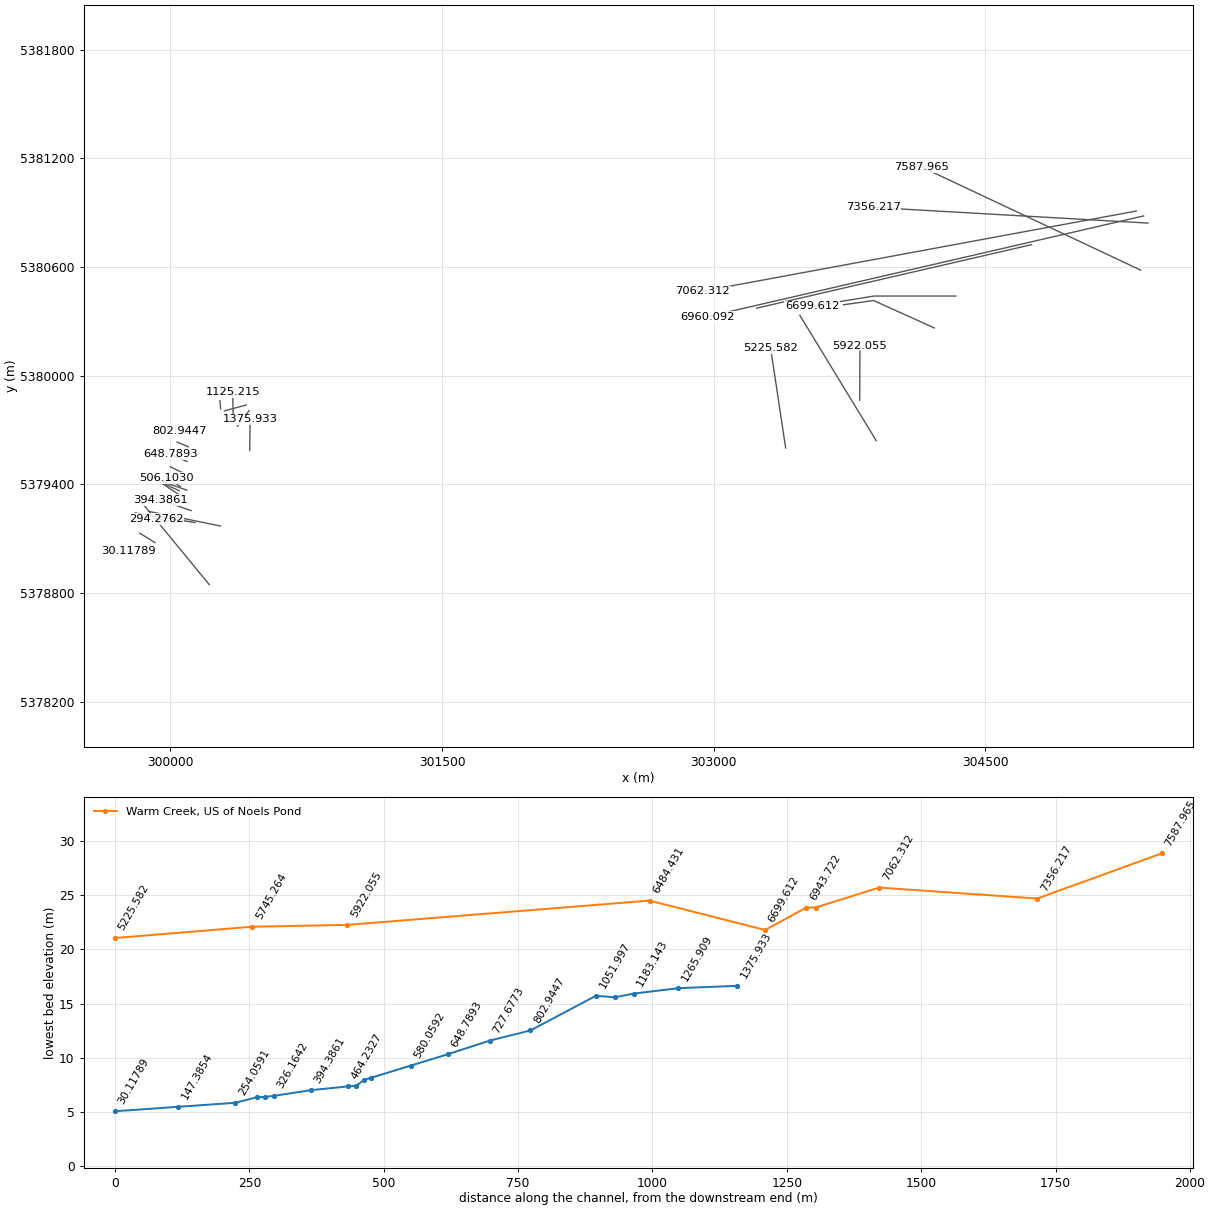
HEC-RAS study Blanche_Brook.prj: Stephenville Model

--- Blanche_Brook.g05 (geometry) --- (continued)

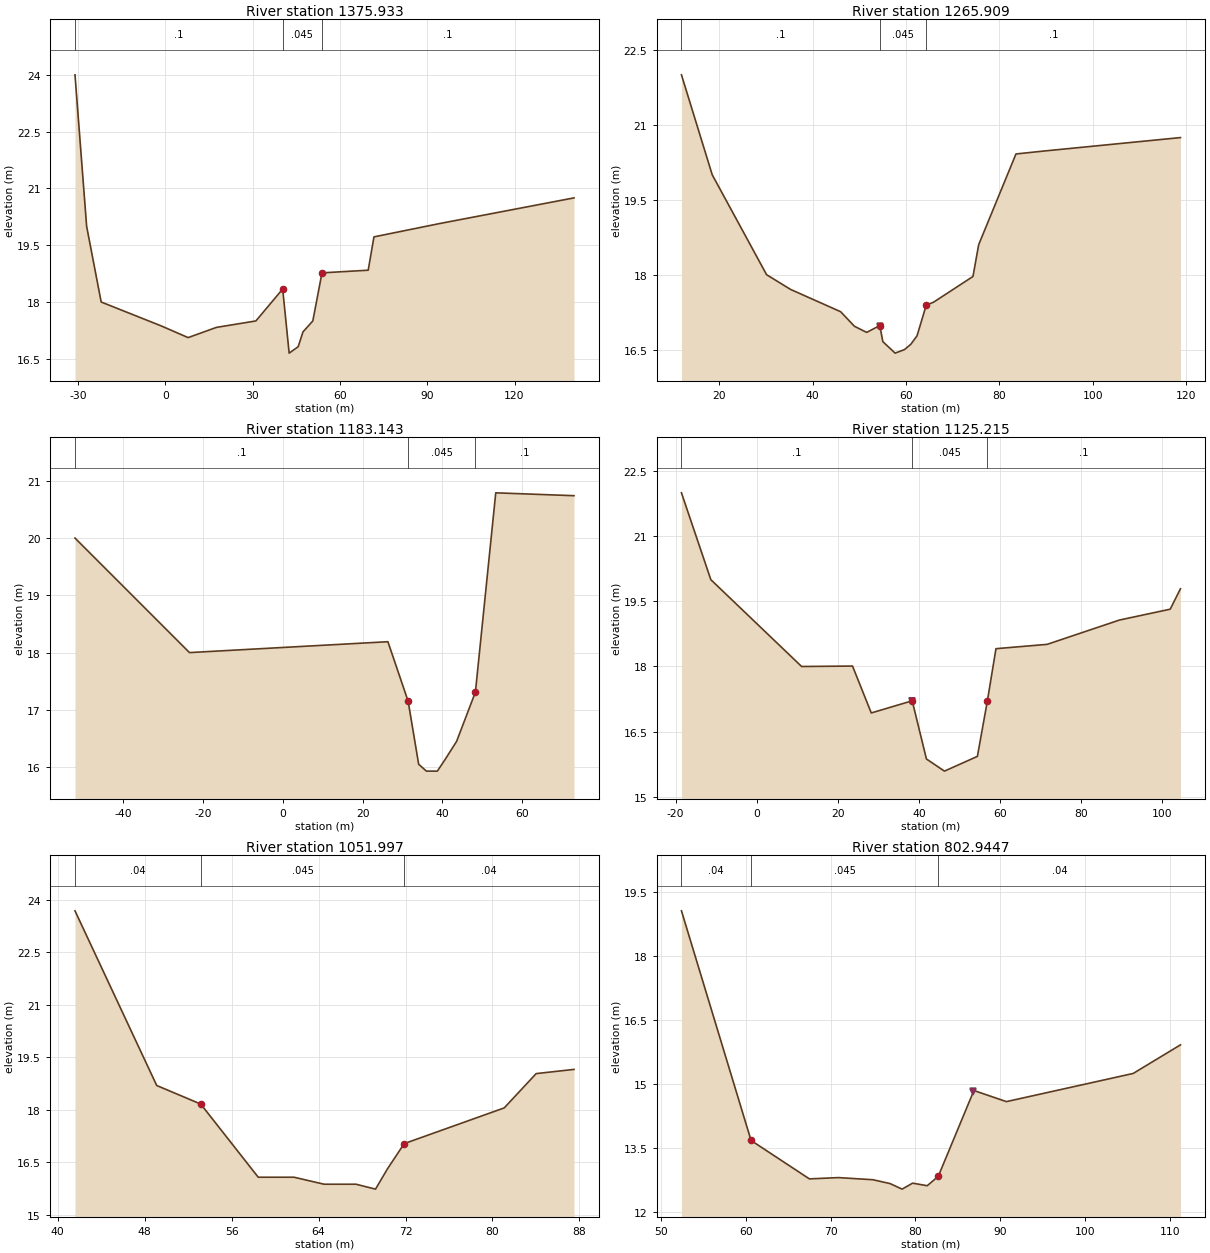
Type RM Length L Ch R = 1 ,1375.933,115.399,110.024,80.619
BEGIN DESCRIPTION:
2008 Survey Section
END DESCRIPTION:
Node Name=W15
XS GIS Cut Line= 4
300438.6961542185379587.56423744300439.2666163955379626.41905013
300439.5602225855379646.41689395300441.2129295155379758.98459923
#Sta/Elev= 19
     -31      24     -29      22     -27      20     -22      18   -1.41   17.37
   7.859   17.06   17.61   17.33  31.149    17.5   40.32   18.34  40.369   18.33
  42.579   16.65  45.689   16.82   47.32   17.21  50.709    17.5  53.859   18.77
  69.739   18.84  71.709   19.72  94.129   20.07 140.439   20.75
#Mann= 3 , 0 , 0
     -31      .1       0   40.32    .045       0  53.859      .1       0
Bank Sta=40.32,53.859
XS Rating Curve= 0 ,0
Exp/Cntr=0.3,0.1

Type RM Length L Ch R = 1 ,1265.909,88.883,82.766,73.503
BEGIN DESCRIPTION:
Interpolated Section
END DESCRIPTION:
Node Name=W14a
XS GIS Cut Line= 3
300370.6541418085379721.89731956300384.7266877325379740.56782603
300435.0195849435379807.29305599
#Sta/Elev= 21
    11.9      22   18.49      20   30.14      18   35.28  17.705  46.005  17.259
  48.973  16.967  51.589  16.845  54.394  16.982   55.05   16.66   57.68   16.43
   59.67    16.5  61.031  16.606  62.371  16.776  64.352  17.391  65.938  17.451
  74.342  17.963  74.403  17.986  75.581    18.6   83.57  20.416  89.684  20.476
 118.816  20.744
#Mann= 3 , 0 , 0
    11.9      .1       0  54.394    .045       0  64.352      .1       0
Levee=-1,54.46,16.97,0,,,,
Bank Sta=54.394,64.352
XS Rating Curve= 0 ,0
Exp/Cntr=0.3,0.1

Type RM Length L Ch R = 1 ,1183.143,20.173,34.556,39.04
BEGIN DESCRIPTION:
2008 Survey Section
END DESCRIPTION:
Node Name=W14
XS GIS Cut Line= 3
300298.9502244315379806.31093566300374.6881692135379826.69472821
300419.7251011965379838.81577904
#Sta/Elev= 12
   -52.1      20   -23.4      18  26.333   18.19  31.403   17.15  34.043   16.05
  35.983   15.93  38.723   15.93  40.823   16.15  43.553   16.45  48.263   17.31
  53.363   20.79  72.973   20.74
#Mann= 3 , 0 , 0
   -52.1      .1       0  31.403    .045       0  48.263      .1       0
Bank Sta=31.403,48.263
XS Rating Curve= 0 ,0
Exp/Cntr=0.3,0.1

Type RM Length L Ch R = 1 ,1125.215,33.473,35.913,35.28
BEGIN DESCRIPTION:
2008 Survey Section
END DESCRIPTION:
Node Name=W13
XS GIS Cut Line= 4
300347.5260179465379785.28417287 300347.485885715379786.86366303
300346.4538013975379827.48355279300344.3981726435379908.38722733
#Sta/Elev= 15
  -18.58      22  -11.33      20   11.07      18  23.633   18.01  28.263   16.93
  38.363   17.21  41.873   15.87  46.323   15.59  54.453   15.93   56.92   17.21
  59.033   18.41  71.663   18.51  89.513   19.07 102.033   19.32 104.563   19.79
#Mann= 3 , 0 , 0
  -18.58      .1       0  38.363    .045       0   56.92      .1       0
Levee=-1,38.24,17.21,0,,,,
Bank Sta=38.363,56.92
XS Rating Curve= 0 ,0
Exp/Cntr=0.3,0.1

Type RM Length L Ch R = 1 ,1051.997,119.597,121.94,125.44
BEGIN DESCRIPTION:
2008 Survey Section
END DESCRIPTION:
Node Name=W12
XS GIS Cut Line= 2
300278.1797119045379817.14976326300273.9853621615379862.86817545
#Sta/Elev= 13
  41.591   23.68  49.111   18.69  53.161   18.16  58.451   16.07   61.74   16.07
  64.511   15.87   67.45   15.87  69.241   15.73   70.34   16.31  71.881   17.03
  81.081   18.05  84.021   19.03  87.501   19.15
#Mann= 3 , 0 , 0
  41.591     .04       0  53.161    .045       0  71.881     .04       0
Bank Sta=53.161,71.881
XS Rating Curve= 0 ,0
Exp/Cntr=0.3,0.1

Type RM Length L Ch R = 1 ,802.9447,71.609,75.267,71.522
BEGIN DESCRIPTION:
2008 Survey Section
END DESCRIPTION:
Node Name=W11
XS GIS Cut Line= 2
 300109.024391465379677.44797171300053.624571032 5379697.0932981
#Sta/Elev= 14
  52.439   19.05  60.639   13.67  67.509   12.77   70.92    12.8  74.999   12.75
   77.01   12.66  78.429   12.53   79.67   12.67  81.389   12.61  82.689   12.83
  86.889   14.84  90.719   14.58 105.649   15.24 111.219   15.91
#Mann= 3 , 0 , 0
  52.439     .04       0  60.639    .045       0  82.689     .04       0
Levee=0,,,-1,86.82,14.83,,
Bank Sta=60.639,82.689
XS Rating Curve= 0 ,0
Exp/Cntr=0.3,0.1

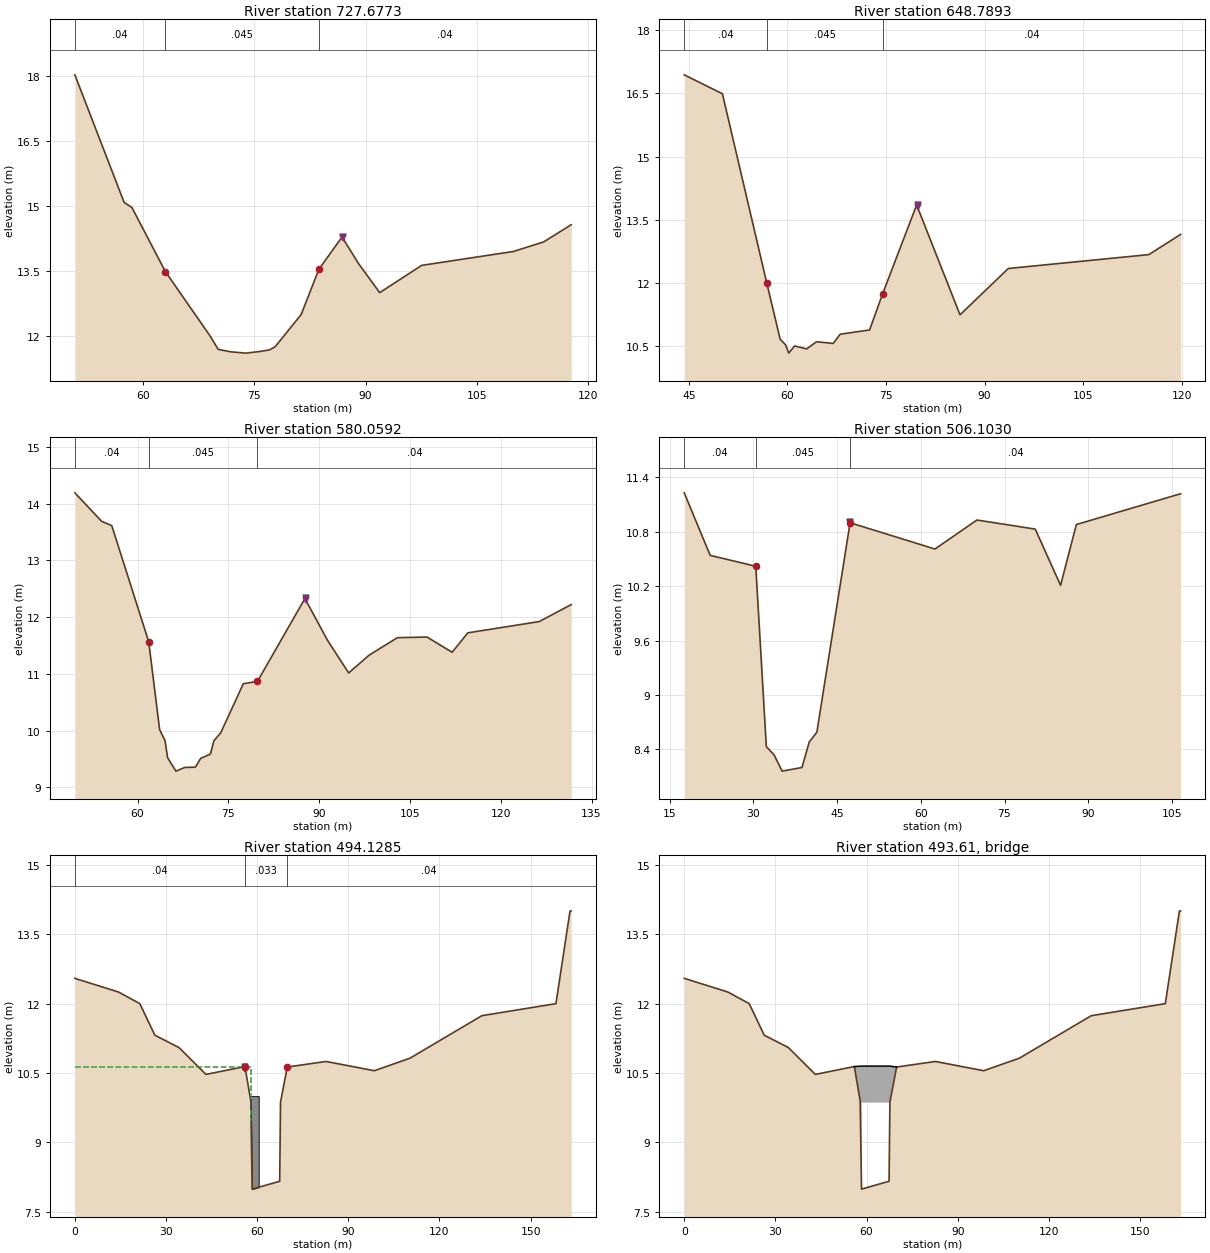
Type RM Length L Ch R = 1 ,727.6773,79.11,78.888,80.462
BEGIN DESCRIPTION:
Interpolated Section
END DESCRIPTION:
Node Name=W10a
XS GIS Cut Line= 2
300099.889136565 5379608.0488858300038.2185467355379634.14028919
#Sta/Elev= 20
  50.773   18.02   57.42  15.077  58.467   14.96  62.989   13.48  69.061  11.985
  70.106  11.687   71.81   11.63   73.84    11.6   75.81   11.64  77.044  11.675
  77.804  11.749  81.308  12.491  83.682  13.531  86.819  14.279  89.043  13.666
  91.899  12.995  97.556  13.624  109.94  13.945 114.019  14.165 117.736  14.562
#Mann= 3 , 0 , 0
  50.773     .04       0  62.989    .045       0  83.682     .04       0
Levee=0,,,-1,86.88,14.29,,
Bank Sta=62.989,83.682
XS Rating Curve= 0 ,0
Exp/Cntr=0.3,0.1

Type RM Length L Ch R = 1 ,648.7893,69.05,68.73,68.507
BEGIN DESCRIPTION:
2008 Survey Section
END DESCRIPTION:
Node Name=W10
XS GIS Cut Line= 2
300092.3868587025379526.86943979300002.014689702   5379565.73747
#Sta/Elev= 18
  44.297   16.94  50.107   16.49   56.85      12  58.897   10.66   59.71   10.53
  60.207   10.33   61.09    10.5  62.927   10.43   64.42    10.6  66.967   10.56
   68.04   10.78  72.507   10.88   74.47   11.73  79.667   13.85  86.267   11.24
  93.617   12.34 115.007   12.67 119.837   13.15
#Mann= 3 , 0 , 0
  44.297     .04       0   56.85    .045       0   74.47     .04       0
Levee=0,,,-1,79.82,13.84,,
Bank Sta=56.85,74.47
XS Rating Curve= 0 ,0
Exp/Cntr=0.3,0.1

Type RM Length L Ch R = 1 ,580.0592,74.519,73.956,72.988
BEGIN DESCRIPTION:
Interpolated Section
END DESCRIPTION:
Node Name=W9a
XS GIS Cut Line= 2
300073.6423346195379462.06826613299999.8798686985379497.88561736
#Sta/Elev= 27
  49.643   14.19  54.069  13.688  55.739  13.612  61.845  11.566  63.644  10.018
   64.55    9.82  64.963   9.522  66.338   9.285   67.81    9.35  69.317   9.354
  69.594    9.36   70.43    9.51  72.035   9.585   72.61    9.82  73.741    9.96
  77.476  10.826  79.808  10.866   87.65  12.327  91.386   11.59  94.878  11.015
  98.263   11.33 102.927  11.637 107.819  11.648 111.971   11.38 114.559  11.722
 126.353  11.921 131.642   12.22
#Mann= 3 , 0 , 0
  49.643     .04       0  61.845    .045       0  79.808     .04       0
Levee=0,,,-1,87.75,12.34,,
Ice Thickness=0.15,0.15,0.15
Ice Mann=0.04,0.04,0.04
Ice Specific Gravity=0.916
Ice Is Channel=-1
Ice Is OB= 0
Ice Friction Angle=45
Ice Porosity=0
Ice K1=0.33
Ice Max Mean Vel=1.524
Ice Cohesion=0
Ice Fixed Mann=-1
Bank Sta=61.845,79.808
XS Rating Curve= 0 ,0
Exp/Cntr=0.3,0.1

Type RM Length L Ch R = 1 ,506.1030,11.553,11.974,12.929
BEGIN DESCRIPTION:
2008 Survey Section
END DESCRIPTION:
Node Name=W9
XS GIS Cut Line= 2
300056.1398469045379388.59785433299980.8645969775379435.98704577
#Sta/Elev= 16
  17.605   11.23  22.255   10.54  30.425   10.42  32.315    8.43    33.7    8.34
  35.145    8.16  38.705     8.2      40    8.48  41.375    8.59  47.325    10.9
  62.535   10.61  70.055   10.93  80.505   10.83  85.045   10.21  87.875   10.88
 106.555   11.22
#Mann= 3 , 0 , 0
  17.605     .04       0  30.425    .045       0  47.325     .04       0
Levee=0,,,-1,47.37,10.91,,
Ice Thickness=0.15,0.15,0.15
Ice Mann=0.04,0.04,0.04
Ice Specific Gravity=0.916
Ice Is Channel=-1
Ice Is OB= 0
Ice Friction Angle=45
Ice Porosity=0
Ice K1=0.33
Ice Max Mean Vel=1.524
Ice Cohesion=0
Ice Fixed Mann=-1
Bank Sta=30.425,47.325
XS Rating Curve= 0 ,0
Exp/Cntr=0.3,0.1

Type RM Length L Ch R = 1 ,494.1285,15.27,14.846,14.427
BEGIN DESCRIPTION:
2008 Survey Section
END DESCRIPTION:
Node Name=W8
XS GIS Cut Line= 4
300090.8916212315379368.46471498300058.5959418035379379.98234975
299964.7175778395379413.46226807299937.0287000835379423.33697537
#Sta/Elev= 19
       0  12.547  14.348  12.252  21.386      12  26.323  11.318  34.288   11.05
  43.138   10.47  55.978   10.64  57.898     9.9  58.348    7.99  67.408    8.16
  67.688    9.87  69.908   10.63  82.668   10.75  98.548   10.55 110.268   10.82
 133.958   11.74  158.33      12 162.957      14 163.355  14.007
#Mann= 3 , 0 , 0
       0     .04       0  55.978    .033       0  69.908     .04       0
Levee=-1,56.09,10.64,0,,,,
#XS Ineff= 2 , 0
       0      58   10.64               0
Permanent Ineff=
       F       F
#Block Obstruct= 2 , 0
       0    60.5      10    65.5       0      10
Ice Thickness=0.15,0.15,0.15
Ice Mann=0.04,0.04,0.04
Ice Specific Gravity=0.916
Ice Is Channel=-1
Ice Is OB= 0
Ice Friction Angle=45
Ice Porosity=0
Ice K1=0.33
Ice Max Mean Vel=1.524
Ice Cohesion=0
Ice Fixed Mann=-1
Bank Sta=55.978,69.908
XS Rating Curve= 0 ,0
Exp/Cntr=0.5,0.3

Type RM Length L Ch R = 3 ,493.61  ,,,
BEGIN DESCRIPTION:
Miss Drive Bridge
END DESCRIPTION:
Bridge Culvert--1,0,-1,-1, 0
Deck Dist Width WeirC Skew NumUp NumDn MinLoCord MaxHiCord MaxSubmerge Is_Ogee
0.52,12.87,1.6,0, 6, 6, , , 0.98, 0, 1,1,,
   55.98    58.4    58.4    67.6    67.6   69.91
   10.64   10.65   10.65   10.65   10.65   10.63
       0       0    9.86    9.86       0       0
   31.34    41.1    41.1    50.3    50.3   57.72
   10.63   10.65   10.65   10.65   10.65   10.63
       0       0    9.86    9.86       0       0
BR Coef=-1 , 0 , 0 ,, 0 ,,,0.8,-1,,0,
WSPro=,,,, 1 ,,,, 0 ,,,, 0 ,,,,-1 ,-1 ,-1 , 0 , 0 , 0 , 0 , 0
BC Design=,, 0 ,, 0 ,,,,,,
BC Use User HTab Curves=0
BC User HTab FreeFlow(D)= 0

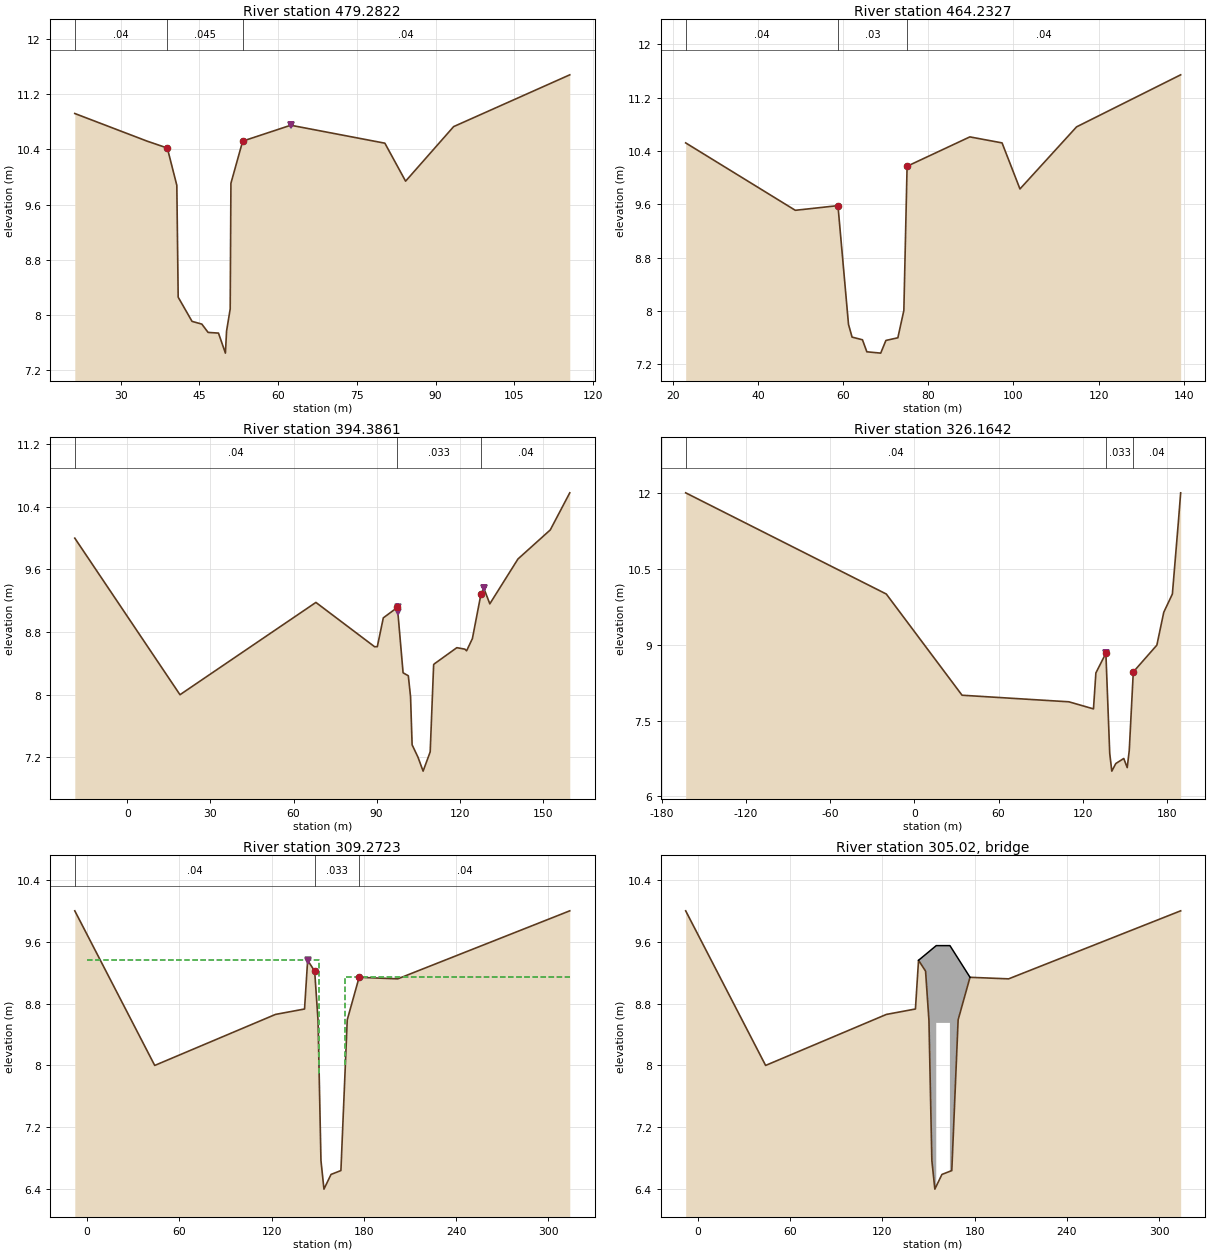
Type RM Length L Ch R = 1 ,479.2822,18.024,15.05,14.12
BEGIN DESCRIPTION:
2008 Survey Section
END DESCRIPTION:
Node Name=W7
XS GIS Cut Line= 2
 300049.926581165379364.90465646299964.7605915165379405.41502764
#Sta/Elev= 19
  21.241   10.92  35.011   10.52  38.871   10.42  40.681    9.88  40.941    8.26
  43.581    7.91   45.45    7.87  46.641    7.75   48.62    7.74  49.941    7.45
   50.16    7.77  50.851    8.09  50.991    9.91  53.231   10.52  62.391   10.75
  80.321   10.49  84.271    9.94  93.421   10.73 115.551   11.48
#Mann= 3 , 0 , 0
  21.241     .04       0  38.871    .045       0  53.231     .04       0
Levee=0,,,-1,62.47,10.76,,
Bank Sta=38.871,53.231
XS Rating Curve= 0 ,0
Exp/Cntr=0.5,0.3

Type RM Length L Ch R = 1 ,464.2327,69.028,69.847,71.832
BEGIN DESCRIPTION:
2008 Survey Section
END DESCRIPTION:
Node Name=W6
XS GIS Cut Line= 2
300055.7657332375379338.69292146299958.817893427 5379403.0048548
#Sta/Elev= 17
   22.96   10.52   48.73    9.51   58.75    9.58   61.23     7.8   62.07    7.61
   64.51    7.57   65.54    7.39    68.8    7.37   70.02    7.56   72.83     7.6
   74.24    8.01      75   10.17   89.75   10.61   97.32   10.52  101.53    9.83
  114.83   10.76   139.3   11.54
#Mann= 3 , 0 , 0
   22.96     .04       0   58.75     .03       0      75     .04       0
Bank Sta=58.75,75
XS Rating Curve= 0 ,0
Exp/Cntr=0.3,0.1

Type RM Length L Ch R = 1 ,394.3861,63.972,68.222,69.71
BEGIN DESCRIPTION:
Interpolated Section
END DESCRIPTION:
Node Name=W5a
XS GIS Cut Line= 3
300115.5698633285379255.65033573300033.2517324575379284.08258489
299946.5794008885379314.01875205
#Sta/Elev= 26
     -19      10      19       8   68.09   9.179  89.294   8.613  90.275   8.614
   92.44   8.982  97.539   9.115   99.58    8.28 101.469   8.242 102.279   7.974
  102.84    7.36 104.951   7.203 106.812   7.024  109.37    7.27  110.62   8.384
 110.902   8.395 118.994   8.601 121.899   8.582 122.526   8.561 124.614   8.717
 127.687   9.281  128.75    9.36 130.906   9.161 141.076   9.734 152.738  10.105
 159.787  10.579
#Mann= 3 , 0 , 0
     -19     .04       0  97.539    .033       0 127.687     .04       0
Levee=-1,97.68,9.12,-1,128.75,9.36,,
Bank Sta=97.539,127.687
XS Rating Curve= 0 ,0
Exp/Cntr=0.3,0.1

Type RM Length L Ch R = 1 ,326.1642,14.443,16.892,18.313
BEGIN DESCRIPTION:
2008 Survey Section
END DESCRIPTION:
Node Name=W5
XS GIS Cut Line= 5
300276.8093800145379170.68468354300136.6980384355379199.28209533
300009.1614444545379225.31293948299892.9600124975379249.03022148
299881.1651905175379251.43760248
#Sta/Elev= 19
    -163      12     -20      10      34       8 110.166    7.87 127.686    7.73
 129.396    8.44 136.526    8.83 139.276    6.85 140.746     6.5 143.606    6.65
 149.266    6.75 151.736    6.57 153.196    6.91 156.066    8.46 172.866    8.99
 177.796    9.64  183.93      10 188.262  11.446 189.834      12
#Mann= 3 , 0 , 0
    -163     .04       0 136.526    .033       0 156.066     .04       0
Levee=-1,136.5,8.84,0,,,,
Bank Sta=136.526,156.066
XS Rating Curve= 0 ,0
Exp/Cntr=0.3,0.1

Type RM Length L Ch R = 1 ,309.2723,15.642,14.996,14.953
BEGIN DESCRIPTION:
2008 Survey Section
END DESCRIPTION:
Node Name=W4
XS GIS Cut Line= 4
300136.303502507 5379189.7286179300007.384630526  5379210.427634
 299915.888196465379225.11816094299805.3834867285379242.86062743
#Sta/Elev= 15
      -8      10      44       8  122.57    8.66  141.46    8.73  143.48    9.36
  148.05    9.22  150.25    8.58  152.14    6.77  154.09     6.4  158.69    6.59
  165.12    6.64  169.24    8.59  176.97    9.14  202.08    9.12     314      10
#Mann= 3 , 0 , 0
      -8     .04       0  148.05    .033       0  176.97     .04       0
Levee=-1,143.55,9.35,0,,,,
#XS Ineff= 2 , 0
       0     151    9.36     168       0    9.14
Permanent Ineff=
       F       F
Bank Sta=148.05,176.97
XS Rating Curve= 0 ,0
Exp/Cntr=0.5,0.3

Type RM Length L Ch R = 3 ,305.02  ,,,
BEGIN DESCRIPTION:
Carolina Ave Bridge
END DESCRIPTION:
Bridge Culvert--1,0,-1,-1, 0
Deck Dist Width WeirC Skew NumUp NumDn MinLoCord MaxHiCord MaxSubmerge Is_Ogee
4.25,8.94,1.6,0, 6, 6, , , 0.98, 0, 1,1,,
  143.48     155     155   163.9   163.9  176.97
    9.36    9.55    9.55    9.55    9.55    9.14
       0       0    8.55    8.55       0       0
  214.21     234     234   242.9   242.9  251.75
     9.3    9.55    9.55    9.55    9.55    9.29
       0       0    8.55    8.55       0       0
BR Coef=-1 , 0 , 0 ,, 0 ,,,0.8,-1,,0,
WSPro=,,,, 1 ,,,, 0 ,,,, 0 ,,,,-1 ,-1 ,-1 , 0 , 0 , 0 , 0 , 0
BC Design=,, 0 ,, 0 ,,,,,,
BC Use User HTab Curves=0
BC User HTab FreeFlow(D)= 0

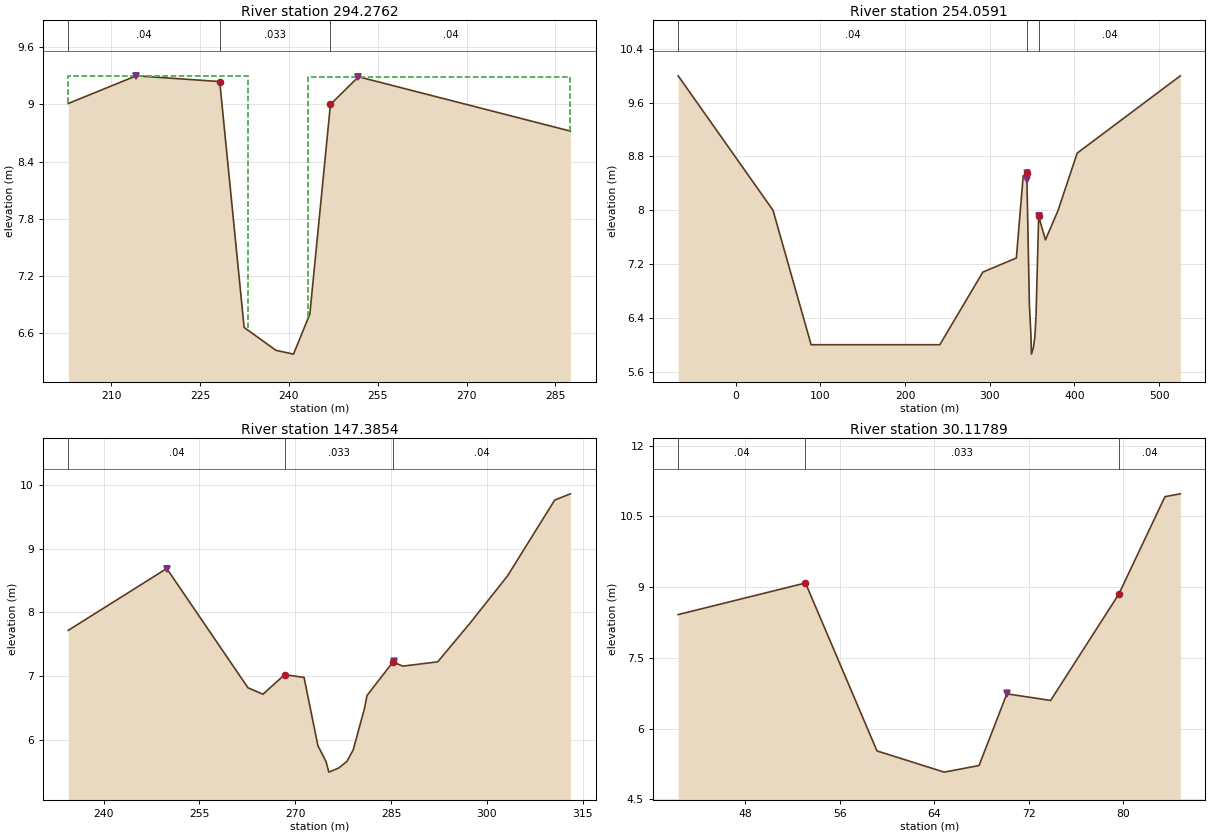
Type RM Length L Ch R = 1 ,294.2762,85.792,40.217,25.479
BEGIN DESCRIPTION:
2008 Survey Section
END DESCRIPTION:
Node Name=W3
XS GIS Cut Line= 2
300028.4277358875379191.25291856299923.975984997 5379209.3649225
#Sta/Elev= 10
 202.728    9.01 214.208     9.3 228.308    9.24 232.428    6.66 237.808    6.42
 240.768    6.38 243.528     6.8 247.008       9 251.748    9.29 287.538    8.72
#Mann= 3 , 0 , 0
 202.728     .04       0 228.308    .033       0 247.008     .04       0
Levee=-1,214.22,9.3,-1,251.63,9.29,,
#XS Ineff= 2 , 0
       0     233     9.3   243.3       0    9.29
Permanent Ineff=
       F       F
Bank Sta=228.308,247.008
XS Rating Curve= 0 ,0
Exp/Cntr=0.5,0.3

Type RM Length L Ch R = 1 ,254.0591,74.46,106.674,110.065
BEGIN DESCRIPTION:
2008 Survey Section
END DESCRIPTION:
Node Name=W2
XS GIS Cut Line= 6
300215.3837418395378846.99193121299986.9183204945379124.95448985
299918.8401838145379207.78178576299916.7070083875379210.37711461
299916.1888667195379211.00751191 299838.846335575379305.10633824
#Sta/Elev= 19
     -68      10      44       8      89       6     241       6 291.805    7.08
 331.375    7.29 339.445    8.51 343.725    8.55 346.775    6.59 348.565    6.16
 349.185    5.86 351.425    5.95 353.245    6.12 354.635    6.44 357.715    7.91
 365.735    7.56 380.705       8 403.195    8.85     525      10
#Mann= 3 , 0 , 0
     -68     .04       0 343.725    .033       0 357.715     .04       0
Levee=-1,343.89,8.55,-1,357.71,7.92,,
Bank Sta=343.725,357.715
XS Rating Curve= 0 ,0
Exp/Cntr=0.3,0.1

Type RM Length L Ch R = 1 ,147.3854,137.703,117.268,115.163
BEGIN DESCRIPTION:
Interpolated Section
END DESCRIPTION:
Node Name=W1a
XS GIS Cut Line= 2
299915.6107996985379079.12916934299831.1880560285379131.14722352
#Sta/Elev= 22
 234.475   7.718  249.89    8.69 262.604   6.815 264.954   6.713  268.34    7.02
  268.37    7.02 271.383   6.978 273.551   5.906 274.823   5.655 275.264   5.488
 276.833   5.554 278.107   5.659  279.08   5.838 280.839   6.487 281.236   6.693
 285.299    7.22 286.852   7.155  292.31   7.223 297.333   7.827 303.214   8.571
 310.622   9.767 313.079   9.865
#Mann= 3 , 0 , 0
 234.475     .04       0  268.34    .033       0 285.299     .04       0
Levee=-1,249.89,8.69,-1,285.46,7.23,,
Bank Sta=268.34,285.299
XS Rating Curve= 0 ,0
Exp/Cntr=0.3,0.1

Type RM Length L Ch R = 1 ,30.11789,11.075,30.118,12.748
BEGIN DESCRIPTION:
2008 Survey Section
END DESCRIPTION:
Node Name=W1
XS GIS Cut Line= 3
299804.6222780285379008.73655182299776.3362714195379031.30821366
299771.3556696555379035.28263325
#Sta/Elev= 10
  42.295    8.42  53.085    9.09  59.145    5.53  64.845    5.08  67.795    5.22
  70.155    6.74  73.865     6.6  79.635    8.85  83.555   10.92  84.855   10.98
#Mann= 3 , 0 , 0
  42.295     .04       0  53.085    .033       0  79.635     .04       0
Levee=0,,,-1,70.16,6.76,,
Bank Sta=53.085,79.635
XS Rating Curve= 0 ,0
Exp/Cntr=0.3,0.1

River Reach=Warm Creek      ,US of Noels Pond

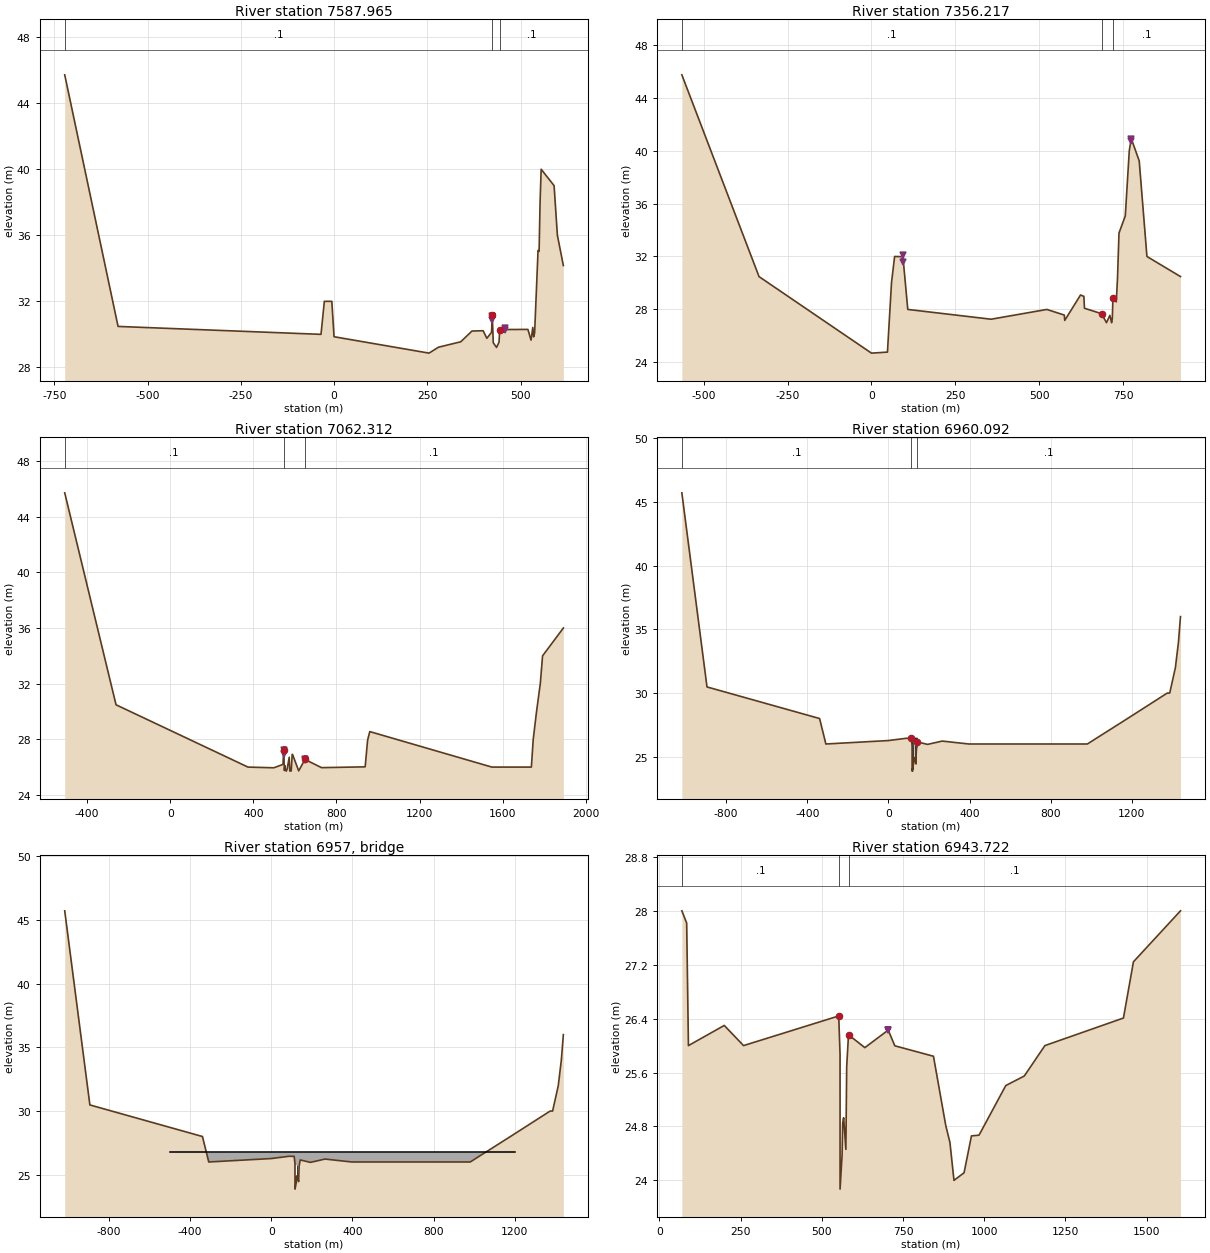
Type RM Length L Ch R = 1 ,7587.965,139.047,231.748,232.266
BEGIN DESCRIPTION:
1996 Survey Section (636.00)
END DESCRIPTION:
Node Name=W35
XS GIS Cut Line= 6
305358.2821172365380582.91070243 304705.023525735380890.37974579
304533.4119525235380971.15211821304474.6228942855380998.82234824
304207.6876949385381124.46066585304148.8500944915381152.15374324
#Sta/Elev= 30
    -722   45.72    -579   30.48     -35      30     -26      32      -6      32
       0  29.856  254.6728.86302  279.67   29.22  339.67   29.55  369.67    30.2
  399.67   30.22  409.57   29.76  422.17   30.12  424.17   31.15  426.77   29.49
  435.57   29.21  442.27   29.53  444.07   30.29  519.67    30.3  528.07   29.65
  532.77   30.42  535.07   29.85  537.67   30.09  546.87   35.08  549.67   35.03
 552.282      38 555.226      40 589.872  39.008 598.738      36 614.699  34.171
#Mann= 3 , 0 , 0
    -722      .1       0  424.17    .035       0  444.07      .1       0
Levee=-1,424.64,31.14,-1,459.42,30.39,,
Bank Sta=424.17,444.07
XS Rating Curve= 0 ,0
Exp/Cntr=0.3,0.1

Type RM Length L Ch R = 1 ,7356.217,152.634,293.905,226.352
BEGIN DESCRIPTION:
1996 Survey Section (635.00)
END DESCRIPTION:
Node Name=W34
XS GIS Cut Line= 6
305398.0686642065380842.93253036304833.9876987025380875.14532837
304212.0330069615380910.66310345304158.571973963 5380913.7160862
304063.5318289745380919.14351449303880.6168932825380929.58918139
#Sta/Elev= 30
    -565   45.72    -335   30.48       0    24.7  47.689  24.776  59.693      30
  69.034      32  93.784  31.986 108.302      28 356.614  27.261 522.707      28
  574.66  27.575 576.039  27.172 622.968   29.09 632.968   28.99 634.768   28.09
 685.668   27.68 700.368      27 710.468   27.55 715.668      27 717.668   27.29
 719.568   28.84 729.568   28.57 733.168   30.32 737.668   33.77 756.423  35.066
 768.363      40 774.245  40.898 797.903  39.222 820.931      32 920.881  30.482
#Mann= 3 , 0 , 0
    -565      .1       0 685.668    .035       0 719.568      .1       0
Levee=-1,95.24,32.1,-1,773.18,40.87,,
Bank Sta=685.668,719.568
XS Rating Curve= 0 ,0
Exp/Cntr=0.3,0.1

Type RM Length L Ch R = 1 ,7062.312,98.8,118.591,118.374
BEGIN DESCRIPTION:
1996 Survey Section (634.00)
END DESCRIPTION:
Node Name=W33
XS GIS Cut Line= 6
305333.0438583175380909.52089663304696.3669127075380791.82047857
304662.8587991295380785.62594144303897.0440186815380644.05222747
303855.7319983815380636.41500722 302939.523546065380467.03849911
#Sta/Elev= 30
    -508   45.72    -261   30.48 374.176      26 498.255   25.95 540.255   26.18
 542.855   26.23 545.455   27.22 549.455   25.75 551.955    26.1 553.655   25.87
 558.255   25.71 562.755   25.87 572.555   26.71 575.455   25.72 582.155   25.72
 586.855    26.9 588.255   26.92 618.255   25.73 648.255   26.55 728.255   25.96
 938.044  26.018 949.793  27.934 960.267  28.553    1548      26    1738      26
    1747      28    1763      30    1781      32    1792      34    1892      36
#Mann= 3 , 0 , 0
    -508      .1       0 545.455    .035       0 648.255      .1       0
Levee=-1,546.2,27.22,-1,649.46,26.55,,
Ice Thickness=0.15,0.15,0.15
Ice Mann=0.04,0.04,0.04
Ice Specific Gravity=0.916
Ice Is Channel=-1
Ice Is OB= 0
Ice Friction Angle=45
Ice Porosity=0
Ice K1=0.33
Ice Max Mean Vel=1.524
Ice Cohesion=0
Ice Fixed Mann=-1
Bank Sta=545.455,648.255
XS Rating Curve= 0 ,0
Exp/Cntr=0.3,0.1

Type RM Length L Ch R = 1 ,6960.092,20,17,20
BEGIN DESCRIPTION:
Interpolated Section
END DESCRIPTION:
Node Name=W32a
XS GIS Cut Line= 6
305373.6559004795380882.48947054304712.074591214 5380729.6785703
304119.1947861295380592.73622402303220.1484616945380385.07606707
302975.5874770035380328.58779601302965.8440114775380326.33726728
#Sta/Elev= 27
   -1018   45.72    -894   30.48    -339      28    -308      26       0   26.27
   88.67   26.45  113.04   26.44  117.06   25.87  117.14   23.87  123.31   24.37
  125.17   24.85  128.11   24.93  135.03   24.46  137.54   25.69   143.1   26.16
  193.36   25.97  265.38   26.23     397      26     898      26     953      26
     981      26    1179      28    1375      30    1387      30    1415      32
    1430      34    1440      36
#Mann= 3 , 0 , 0
   -1018      .1       0  113.04    .035       0   143.1      .1       0
#Block Obstruct= 2 ,-1
     112     120    26.5     130     140    26.5
Ice Thickness=0.15,0.15,0.15
Ice Mann=0.04,0.04,0.04
Ice Specific Gravity=0.916
Ice Is Channel=-1
Ice Is OB= 0
Ice Friction Angle=45
Ice Porosity=0
Ice K1=0.33
Ice Max Mean Vel=1.524
Ice Cohesion=0
Ice Fixed Mann=-1
Bank Sta=113.04,143.1
XS Rating Curve= 0 ,0
Exp/Cntr=0.5,0.3

Type RM Length L Ch R = 3 ,6957    ,,,
BEGIN DESCRIPTION:
Route 460 Bridge
END DESCRIPTION:
Bridge Culvert--1,0,-1,-1, 0
Deck Dist Width WeirC Skew NumUp NumDn MinLoCord MaxHiCord MaxSubmerge Is_Ogee
3,8,1.6,0, 6, 6, , , 0.98, 0, 1,1,,
    -500  117.93  117.93  135.33  135.33    1200
   26.75   26.75   26.75   26.75   26.75   26.75
       0       0   25.74   25.74       0       0
       0     557     557   574.4   574.4    1500
   26.75   26.75   26.75   26.75   26.75   26.75
       0       0   25.74   25.74       0       0
Pier Skew, UpSta & Num, DnSta & Num=  ,126.63, 2 ,565.7, 2 , 0 , 0 , 0 ,,
       1       1
       0   25.74
       1       1
       0   25.74
BR Coef=-1 , 0 , 0 ,, 0 ,,,0.8,-1,,0,
WSPro=,,,, 1 ,,,, 0 ,,,, 0 ,,,,-1 ,-1 ,-1 , 0 , 0 , 0 , 0 , 0
BC Design=,, 0 ,, 0 ,,,,,,
BC Use User HTab Curves=0
BC User HTab FreeFlow(D)= 0

Type RM Length L Ch R = 1 ,6943.722,123.195,76.783,97.272
BEGIN DESCRIPTION:
2008 Survey Section
END DESCRIPTION:
Node Name=W32
XS GIS Cut Line= 5
304755.0624568345380723.86703864304394.7057797725380640.62571343
304113.6268121875380575.69730433303378.2603340355380405.82982565
303237.1540776855380373.23469832
#Sta/Elev= 30
  69.221      28  84.092  27.819  89.477      26 199.772  26.299 259.117      26
 552.107   26.44 556.127   25.87 556.207   23.87 562.377   24.37 564.237   24.85
 567.177   24.93 574.097   24.46 576.607   25.69 582.167   26.16 632.427   25.97
 704.447   26.23 724.712  25.997 843.703  25.842   881.5  24.815 894.381  24.563
 906.814      24 937.905  24.113 960.636   24.66 983.982  24.6711066.262  25.407
1123.327  25.5491186.665      261428.444  26.4091459.178  27.243    1604      28
#Mann= 3 , 0 , 0
  69.221      .1       0 552.107    .035       0 582.167      .1       0
Levee=0,,,-1,704.35,26.23,,
Bank Sta=552.107,582.167
XS Rating Curve= 0 ,0
Exp/Cntr=0.5,0.3

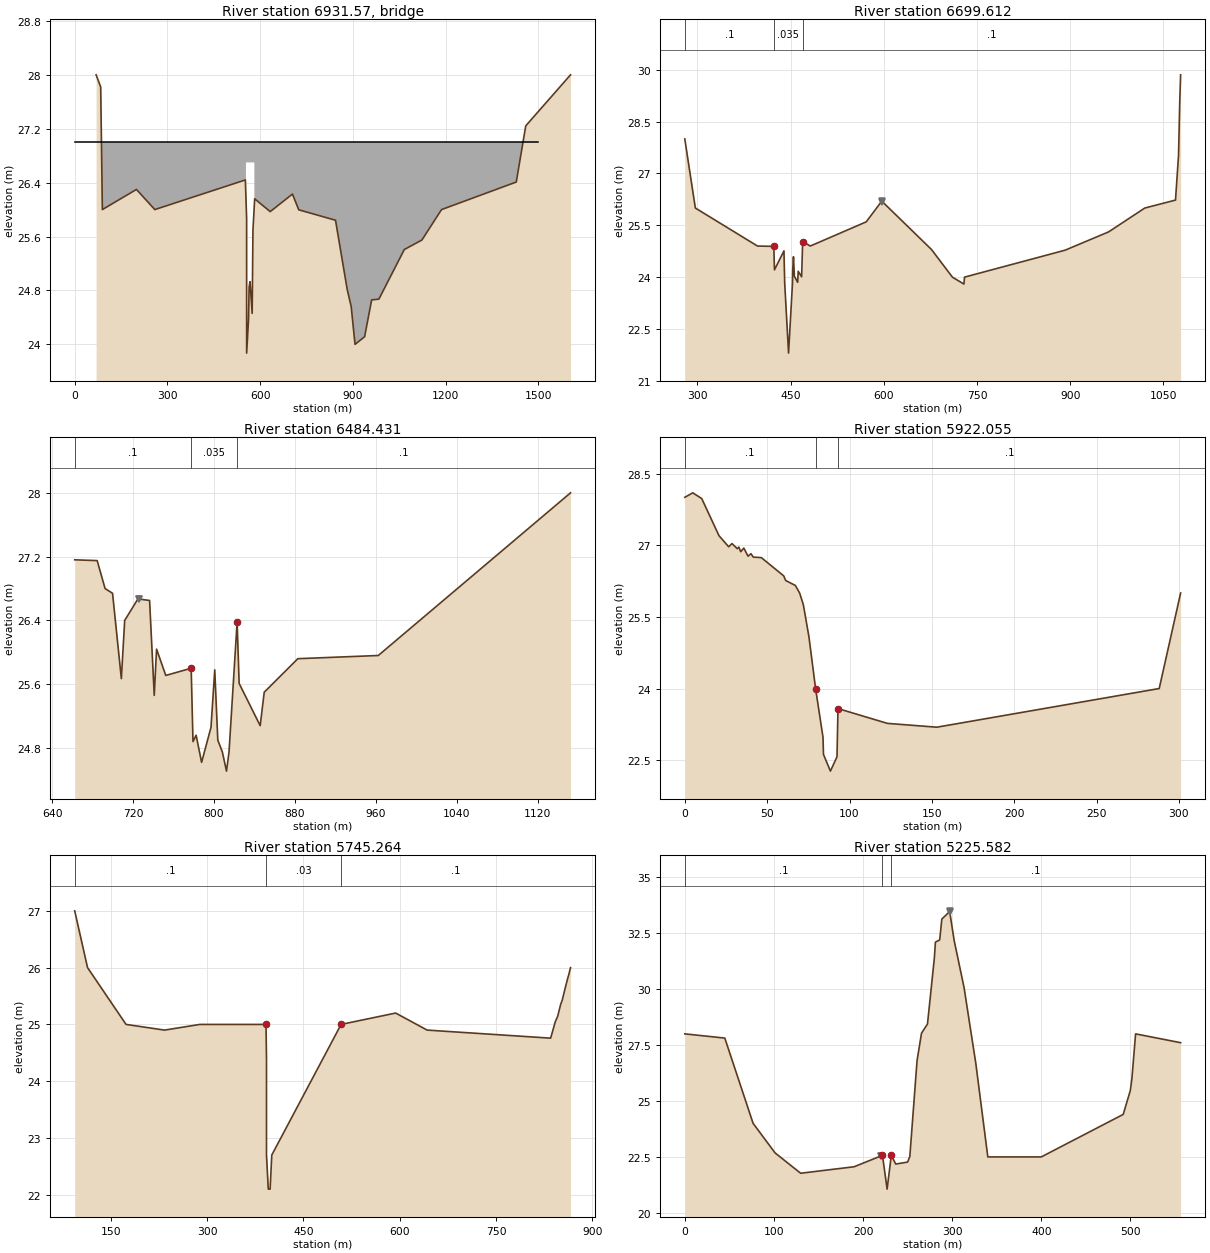
Type RM Length L Ch R = 3 ,6931.57 ,,,
BEGIN DESCRIPTION:
Route 460 Railway Trestle
END DESCRIPTION:
Bridge Culvert--1,0,-1,-1, 0
Deck Dist Width WeirC Skew NumUp NumDn MinLoCord MaxHiCord MaxSubmerge Is_Ogee
12.15,3.65,1.6,0, 6, 6, , , 0.98, 0, 1,1,,
       0     554     554  581.15  581.15    1500
      27      27      27      27      27      27
       0       0    26.7    26.7       0       0
  423.11     560     560  587.15  587.15    1300
      27      27      27      27      27      27
       0       0    26.7    26.7       0       0
BR Coef=-1 , 0 , 0 ,, 0 ,,,0.8,-1,,0,
WSPro=,,,, 1 ,,,, 0 ,,,, 0 ,,,,-1 ,-1 ,-1 , 0 , 0 , 0 , 0 , 0
BC Design=,, 0 ,, 0 ,,,,,,
BC Use User HTab Curves=0
BC User HTab FreeFlow(D)= 0

Type RM Length L Ch R = 1 ,6699.612,174.266,215.182,71.29
BEGIN DESCRIPTION:
1996 Survey Section (631.00)
END DESCRIPTION:
Node Name=W30
XS GIS Cut Line= 4
  304337.34655055380440.25391269303885.2392684315380440.25533154
303835.9968712245380432.22324907303543.9179118895380384.58133028
#Sta/Elev= 30
  279.74      28  296.74      26  396.74    24.9  423.04   24.89  424.04   24.21
  439.34   24.76  440.54   23.82  446.74    21.8  453.04   23.82  453.44   24.21
  454.64   24.59  456.14   24.02  461.44   23.85  462.24   24.17  467.74   24.01
  469.44   25.03  481.74    24.9  571.74    25.6  596.74    26.2  676.74    24.8
 710.405      24 728.945  23.799 729.943      24 891.661  24.779 961.754  25.309
1020.043      261069.432   26.231074.301  27.5211076.224  29.0361077.679  29.856
#Mann= 3 , 0 , 0
  279.74      .1       0  423.04    .035       0  469.44      .1       0
Levee=0,,,-1,597.64,26.19,,
Bank Sta=423.04,469.44
XS Rating Curve= 0 ,0
Exp/Cntr=0.3,0.1

Type RM Length L Ch R = 1 ,6484.431,616.58,562.375,435.815
BEGIN DESCRIPTION:
1996 Survey Section (633.00)
END DESCRIPTION:
Node Name=W29
XS GIS Cut Line= 6
304218.8051609775380263.84443487303882.7370809715380415.61423989
303815.8542459355380406.09868082303776.2530289295380400.46453389
303736.6518119225380394.83038696303716.851203419 5380392.0133135
#Sta/Elev= 28
 662.342   27.16 684.542   27.15 692.342    26.8 699.742   26.74 708.442   25.67
 711.742    26.4 724.842   26.67 736.342   26.65 740.942   25.46 743.242   26.04
 752.342   25.71 777.442    25.8 779.242   24.88 782.342   24.96 787.742   24.62
 797.042   25.06 800.742   25.78 803.742    24.9 808.242   24.75 812.342   24.51
 814.842   24.75 822.842   26.38 824.842   25.61 845.642   25.08 849.642    25.5
 882.842   25.92 962.342   25.961152.342      28
#Mann= 3 , 0 , 0
 662.342      .1       0 777.442    .035       0 822.842      .1       0
Levee=-1,725.54,26.67,0,,,,
Bank Sta=777.442,822.842
XS Rating Curve= 0 ,0
Exp/Cntr=0.3,0.1

Type RM Length L Ch R = 1 ,5922.055,190,176.792,190
BEGIN DESCRIPTION:
1996 Survey Section (629.00)
END DESCRIPTION:
Node Name=W28
XS GIS Cut Line= 4
303806.3940636145379865.06548458303806.3940636145379865.06548459
303807.1977242375380045.09012081303807.7377673825380166.06291441
#Sta/Elev= 30
       0  28.005    4.84  28.099  10.284  27.979  20.749  27.202  26.643  26.969
  28.642  27.036  31.852  26.929  32.783  26.964  33.969  26.865  35.824  26.942
  38.408  26.772  40.159  26.824  41.584  26.752  46.464  26.742  60.071  26.359
   61.26  26.262  67.129  26.159  69.717      26  71.974  25.755  75.361  25.085
  79.394      24    83.9   22.98    84.2   22.62    88.4   22.27    92.4   22.57
      93   23.58     123   23.27     153   23.19     288      24     301      26
#Mann= 3 , 0 , 0
       0      .1       0  79.394    .035       0      93      .1       0
Bank Sta=79.394,93
XS Rating Curve= 0 ,0
Exp/Cntr=0.3,0.1

Type RM Length L Ch R = 1 ,5745.264,259.064,255.295,179.874
BEGIN DESCRIPTION:
1996 Survey Section (629.10)
END DESCRIPTION:
Node Name=W27
XS GIS Cut Line= 6
303897.5228163715379641.80152513303866.3019902455379693.03880746
 303855.895046885379710.11790374303587.1544735345380151.15481206
 303562.709615165380191.27188343303475.6024384215380334.22566015
#Sta/Elev= 25
  93.678      27 113.678      26 173.678      25 233.678    24.9 288.678      25
 391.678      25 392.438    24.4 392.448    22.7  395.22    22.1  398.07    22.1
 400.668    22.7 508.678      25 593.678    25.2 642.678    24.9 835.075  24.758
 842.339  25.047 843.953   25.09 846.085  25.144  850.64  25.351 851.731  25.385
 853.006  25.422 858.585  25.677 862.203  25.834 863.076  25.865  866.08      26
#Mann= 3 , 0 , 0
  93.678      .1       0 391.678     .03       0 508.678      .1       0
Bank Sta=391.678,508.678
XS Rating Curve= 0 ,0
Exp/Cntr=0.3,0.1

Type RM Length L Ch R = 1 ,5225.582,86.513,147.307,158.26
BEGIN DESCRIPTION:
1996 Survey Section (627.00)
END DESCRIPTION:
Node Name=W25
XS GIS Cut Line= 3
303397.6071004285379601.05336699303332.0186180245380036.13714577
303314.6786496865380151.16250803
#Sta/Elev= 30
       0      28  44.896  27.812  76.636      24 101.349  22.678     130   21.77
     190   22.06   221.8   22.57     227   21.06   231.7   22.57   236.7   22.18
     250   22.27   252.5   22.52   260.6    26.8   265.6   28.03   272.3   28.44
     280   31.38   281.2    32.1     286    32.2   288.4   33.13   297.2   33.47
   302.2   32.18   313.3   30.08   326.5   26.69     340    22.5     400    22.5
 491.924    24.4 499.908  25.472 501.669      26 505.808      28 556.325  27.606
#Mann= 3 , 0 , 0
       0      .1       0   221.8     .03       0   231.7      .1       0
Levee=-1,220.56,22.52,-1,297.36,33.5,,
Bank Sta=221.8,231.7
XS Rating Curve= 0 ,0
Exp/Cntr=0.3,0.1