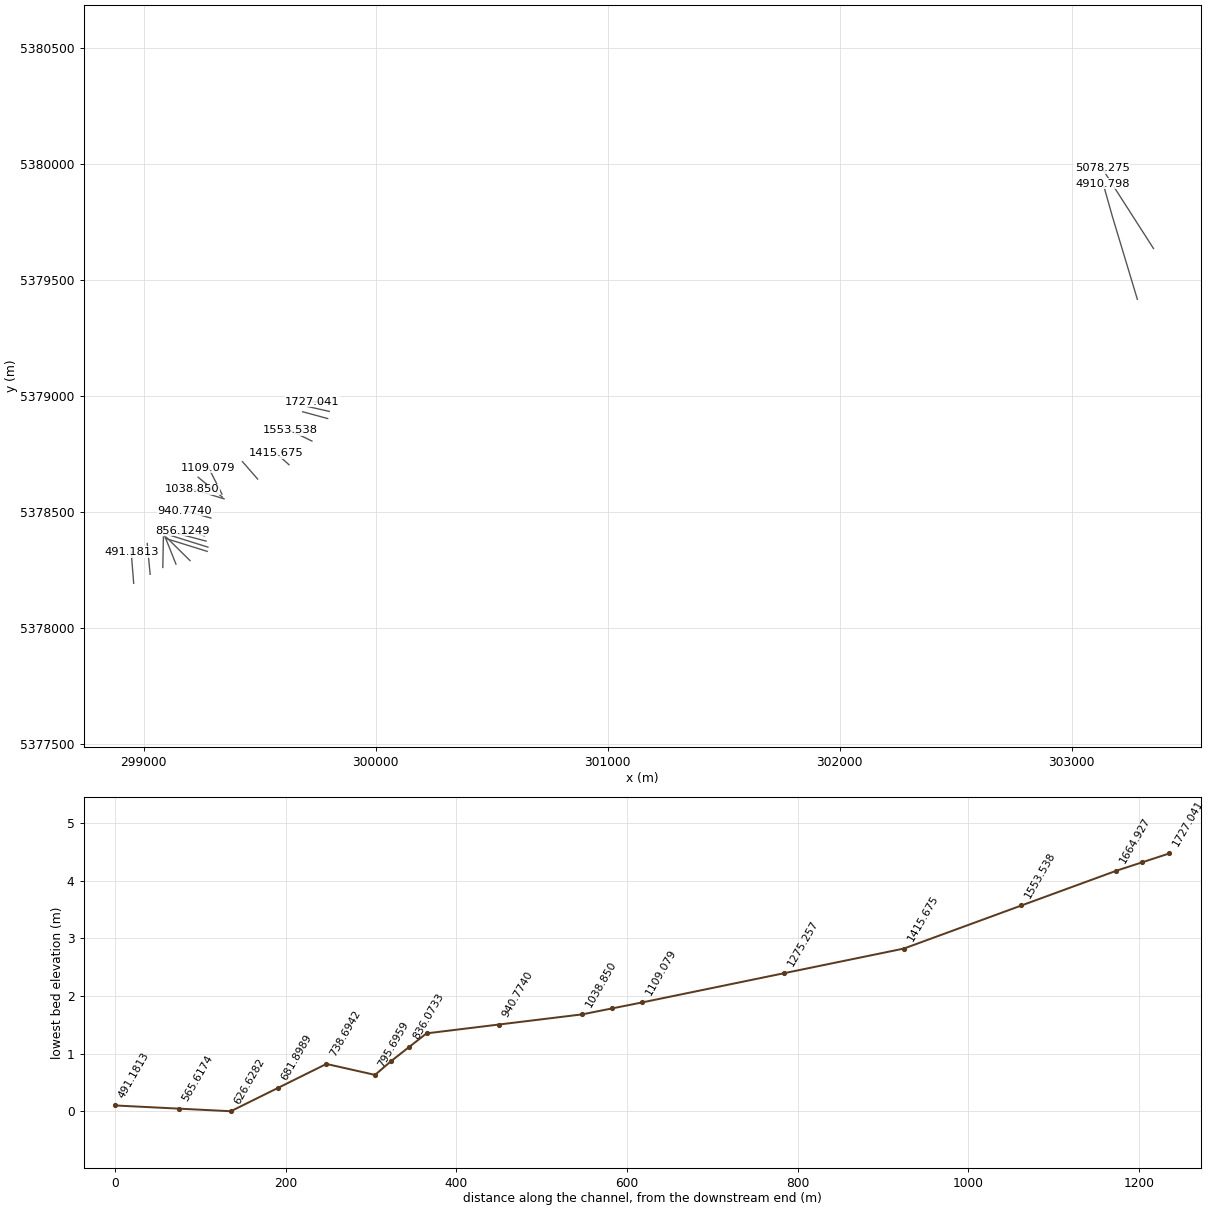
HEC-RAS study Blanche_Brook.prj: Stephenville Model

--- Blanche_Brook.g05 (geometry) --- (continued)

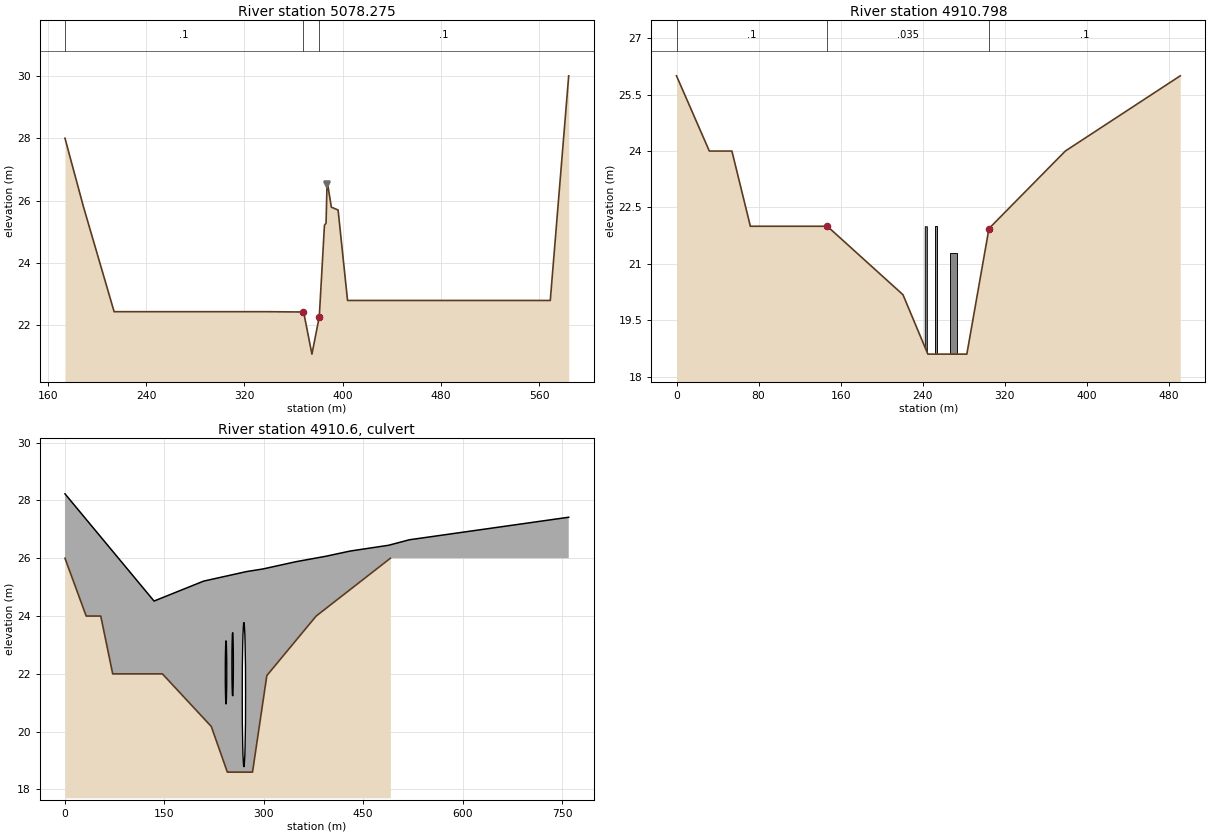
Type RM Length L Ch R = 1 ,5078.275,131.874,182.721,103.016
BEGIN DESCRIPTION:
1996 Survey Section (626.00)
END DESCRIPTION:
Node Name=W24
XS GIS Cut Line= 2
 303352.251843395379637.18626122303130.9721827245379982.34539722
#Sta/Elev= 17
 173.918      28 188.918   25.81 213.918   22.44 338.818   22.44 367.918   22.43
 368.918   22.28 374.918   21.08 380.918   22.28 385.118   25.21 386.418   25.28
  387.22   26.53 387.618   26.56 390.718   25.79 396.218    25.7 403.918    22.8
 568.918    22.8 583.918      30
#Mann= 3 , 0 , 0
 173.918      .1       0 367.918     .03       0 380.918      .1       0
Levee=0,,,-1,387.22,26.51,,
Ice Thickness=0.15,0.15,0.15
Ice Mann=0.04,0.04,0.04
Ice Specific Gravity=0.916
Ice Is Channel=-1
Ice Is OB= 0
Ice Friction Angle=45
Ice Porosity=0
Ice K1=0.33
Ice Max Mean Vel=1.524
Ice Cohesion=0
Ice Fixed Mann=-1
Bank Sta=367.918,380.918
XS Rating Curve= 0 ,0
Exp/Cntr=0.3,0.1

Type RM Length L Ch R = 1 ,4910.798,35,30.793,35
BEGIN DESCRIPTION:
1:2500 Community Mapping Section
END DESCRIPTION:
Node Name=490us
XS GIS Cut Line= 4
 303282.70595662 5379418.2374223303233.2754357335379582.20207694
303174.4464749665379777.34204437303135.1536623475379916.66644125
#Sta/Elev= 11
       0      26      32      24      54      24      72      22     147      22
  220.75   20.18     245    18.6     283    18.6  304.58   21.94     379      24
     491      26
#Mann= 3 , 0 , 0
       0      .1       0     147    .035       0  304.58      .1       0
#Block Obstruct= 3 ,-1
     242     244      22     252     254      22     267     273    21.3
Ice Thickness=0.15,0.15,0.15
Ice Mann=0.04,0.04,0.04
Ice Specific Gravity=0.916
Ice Is Channel=-1
Ice Is OB= 0
Ice Friction Angle=45
Ice Porosity=0
Ice K1=0.33
Ice Max Mean Vel=1.524
Ice Cohesion=0
Ice Fixed Mann=-1
Bank Sta=147,304.58
XS Rating Curve= 0 ,0
Exp/Cntr=0.5,0.3

Type RM Length L Ch R = 2 ,4910.6  ,,,
BEGIN DESCRIPTION:
Route 490 Culverts
END DESCRIPTION:
Bridge Culvert--1,0,-1,-1, 0
Deck Dist Width WeirC Skew NumUp NumDn MinLoCord MaxHiCord MaxSubmerge Is_Ogee
1,20,1.6,0, 11, 11, , , 0.98, 0, 1,1,,
       0  134.37  209.24  274.03  298.69  348.17  393.74  430.23  488.38  519.55
  760.07
   28.23   24.52   25.21   25.54   25.63   25.88   26.07   26.25   26.45   26.64
   27.42
       0       0       0       0       0       0       0       0       0       0
       0
       0  134.37  209.24  274.03  298.69  348.17  393.74  430.23  488.38  519.55
  760.07
   28.23   24.52   25.21   25.54   25.63   25.88   26.07   26.25   26.45   26.64
   27.42
       0       0       0       0       0       0       0       0       0       0
       0
BR Coef=-1 , 0 , 0 ,, 0 ,,,0.8,-1,,0,
WSPro=,,,, 1 ,,,, 0 ,,,, 0 ,,,,-1 ,-1 ,-1 , 0 , 0 , 0 , 0 , 0
Culvert=1,2.2,,30.01,0.024,0.9,1,2,3,20.95,243,20.84,243,Culvert #2  , 0 ,0.5
Culvert Bottom n=0.024
Culvert=1,2.2,,29.76,0.024,0.9,1,2,3,21.23,253,20.8,253,Culvert #3  , 0 ,0.5
Culvert Bottom n=0.024
Culvert=1,5,,25.57,0.024,0.9,1,2,3,18.78,270,18.9,270,Culvert #1  , 0 ,0.5
Culvert Bottom n=0.024
BC Design=,, 0 ,, 0 ,,,,,,
BC Use User HTab Curves=0
BC User HTab FreeFlow(D)= 0

River Reach=Blanche Brook   ,DS of Confluence

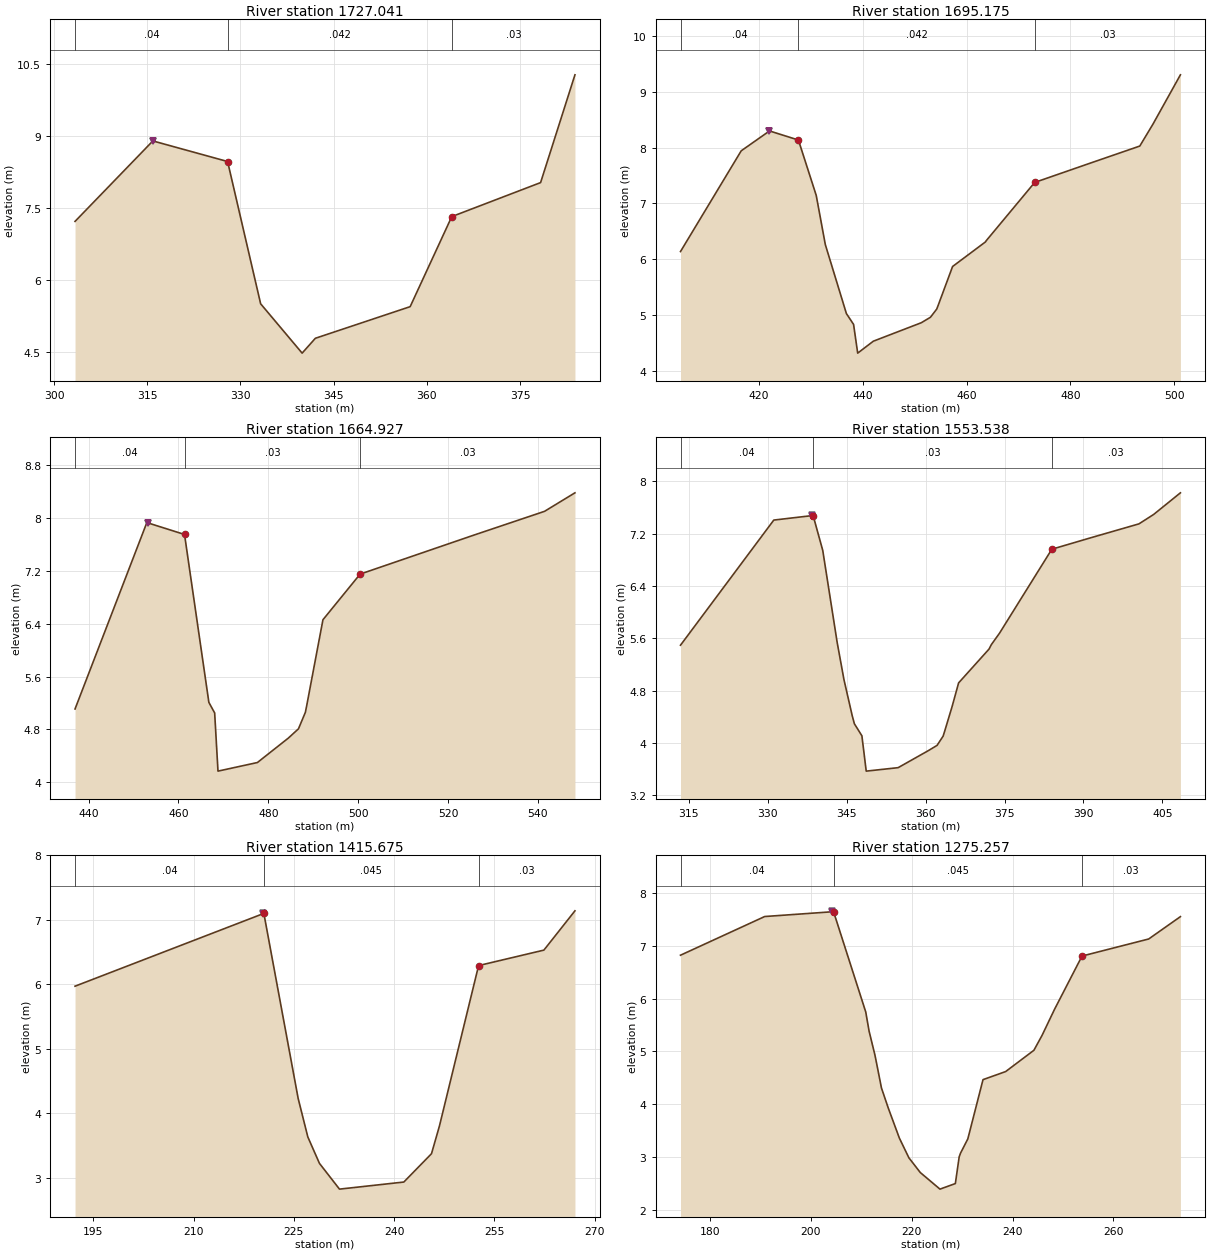
Type RM Length L Ch R = 1 ,1727.041,38.425,31.866,27.978
BEGIN DESCRIPTION:
2008 Survey Section
END DESCRIPTION:
Node Name=BB11
XS GIS Cut Line= 3
299807.7864269475378971.57526448299733.2779646595378976.35237414
299727.4708878445378976.72469484
#Sta/Elev= 10
 303.369    7.22 315.899     8.9  327.93    8.47 333.249     5.5 339.929    4.47
 342.059    4.78 357.319    5.44 364.019    7.32 378.319    8.03 383.849   10.28
#Mann= 3 , 0 , 0
 303.369     .04       0  327.93    .042       0 364.019     .03       0
Levee=-1,315.94,8.9,0,,,,
Bank Sta=327.93,364.019
XS Rating Curve= 0 ,0
Exp/Cntr=0.3,0.1

Type RM Length L Ch R = 1 ,1695.175,33,30.247,29.947
BEGIN DESCRIPTION:
Interpolated Section
END DESCRIPTION:
Node Name=BB10a
XS GIS Cut Line= 3
299799.994839391 5378935.1190029299718.8196115125378953.47964996
299706.0696942955378956.36349441
#Sta/Elev= 22
 404.903   6.137 416.601   7.943  422.05   8.299 427.618   8.136 431.047   7.144
 432.799   6.262 436.859   5.025 438.242   4.831 439.036   4.316 442.051    4.53
 451.292   4.861 453.052   4.959 454.256   5.105 454.507   5.165 457.315   5.869
  463.65    6.31 463.783    6.33 473.133   7.376 483.587   7.714 493.374   8.028
 495.906    8.42 501.201   9.305
#Mann= 3 , 0 , 0
 404.903     .04       0 427.618    .042       0 473.133     .03       0
Levee=-1,421.96,8.29,0,,,,
Bank Sta=427.618,473.133
XS Rating Curve= 0 ,0
Exp/Cntr=0.3,0.1

Type RM Length L Ch R = 1 ,1664.927,121.636,111.389,102.212
BEGIN DESCRIPTION:
2008 Survey Section
END DESCRIPTION:
Node Name=BB10
XS GIS Cut Line= 2
299792.9686280485378904.34813455299685.5516430365378933.52707675
#Sta/Elev= 16
 436.966    5.11 452.956    7.93 461.346    7.75 466.766    5.21 468.056    5.05
 468.796    4.17  477.57     4.3 484.466    4.67 486.716    4.81 488.256    5.06
 488.576    5.17 492.166    6.46 500.436    7.15 525.756    7.74 541.506     8.1
 548.276    8.38
#Mann= 3 , 0 , 0
 436.966     .04       0 461.346     .03       0 500.436     .03       0
Levee=-1,453.22,7.93,0,,,,
Bank Sta=461.346,500.436
XS Rating Curve= 0 ,0
Exp/Cntr=0.3,0.1

Type RM Length L Ch R = 1 ,1553.538,157.692,137.863,125.752
BEGIN DESCRIPTION:
Interpolated Section
END DESCRIPTION:
Node Name=BB9a
XS GIS Cut Line= 2
299725.3013170545378807.32741864299630.6613077975378853.32246314
#Sta/Elev= 25
 313.423   5.494 331.152   7.409 338.622   7.479 340.455   6.945 343.196   5.536
 344.489   4.966 346.041    4.42 346.465   4.292 347.895   4.108 348.716   3.567
  354.78    3.62 360.488   3.879 362.178   3.961 363.335   4.103 363.576   4.165
 365.033   4.554 366.273   4.917 372.047   5.434 372.486   5.502 374.064    5.68
 383.993   6.963 391.507   7.141 400.547   7.351 403.339   7.495 408.425   7.826
#Mann= 3 , 0 , 0
 313.423     .04       0 338.622     .03       0 383.993     .03       0
Levee=-1,338.37,7.48,0,,,,
Bank Sta=338.622,383.993
XS Rating Curve= 0 ,0
Exp/Cntr=0.3,0.1

Type RM Length L Ch R = 1 ,1415.675,158.169,140.419,140.146
BEGIN DESCRIPTION:
2008 Survey Section
END DESCRIPTION:
Node Name=BB9
XS GIS Cut Line= 2
299626.2413460285378705.45654513  299570.34668825378755.19468992
#Sta/Elev= 12
 192.244    5.97 220.504     7.1 225.634    4.23 227.084    3.63 228.824    3.22
 231.824    2.82 241.454    2.93 245.594    3.37 246.784     3.8 252.644    6.29
 262.414    6.53 267.064    7.14
#Mann= 3 , 0 , 0
 192.244     .04       0 220.504    .045       0 252.644     .03       0
Levee=-1,220.36,7.1,0,,,,
Bank Sta=220.504,252.644
XS Rating Curve= 0 ,0
Exp/Cntr=0.3,0.1

Type RM Length L Ch R = 1 ,1275.257,168.064,166.177,163.118
BEGIN DESCRIPTION:
Interpolated Section
END DESCRIPTION:
Node Name=BB8a
XS GIS Cut Line= 2
299491.2122140655378643.65235928299425.9659520055378718.40909343
#Sta/Elev= 25
 174.101    6.82 190.812   7.552 204.481   7.644 210.871   5.745 211.531   5.384
 212.689   4.932 212.969     4.8 213.987   4.308  215.33    3.93 217.546   3.358
 219.432   2.986 221.696   2.707   225.6   2.393 228.654   2.498 229.417   3.005
 229.684   3.074 231.131   3.344 234.144   4.465 238.642   4.618 244.249   5.021
  245.86   5.302 248.325   5.793 253.797   6.804 267.029   7.127 273.326    7.55
#Mann= 3 , 0 , 0
 174.101     .04       0 204.481    .045       0 253.797     .03       0
Levee=-1,204.13,7.66,0,,,,
Bank Sta=204.481,253.797
XS Rating Curve= 0 ,0
Exp/Cntr=0.3,0.1

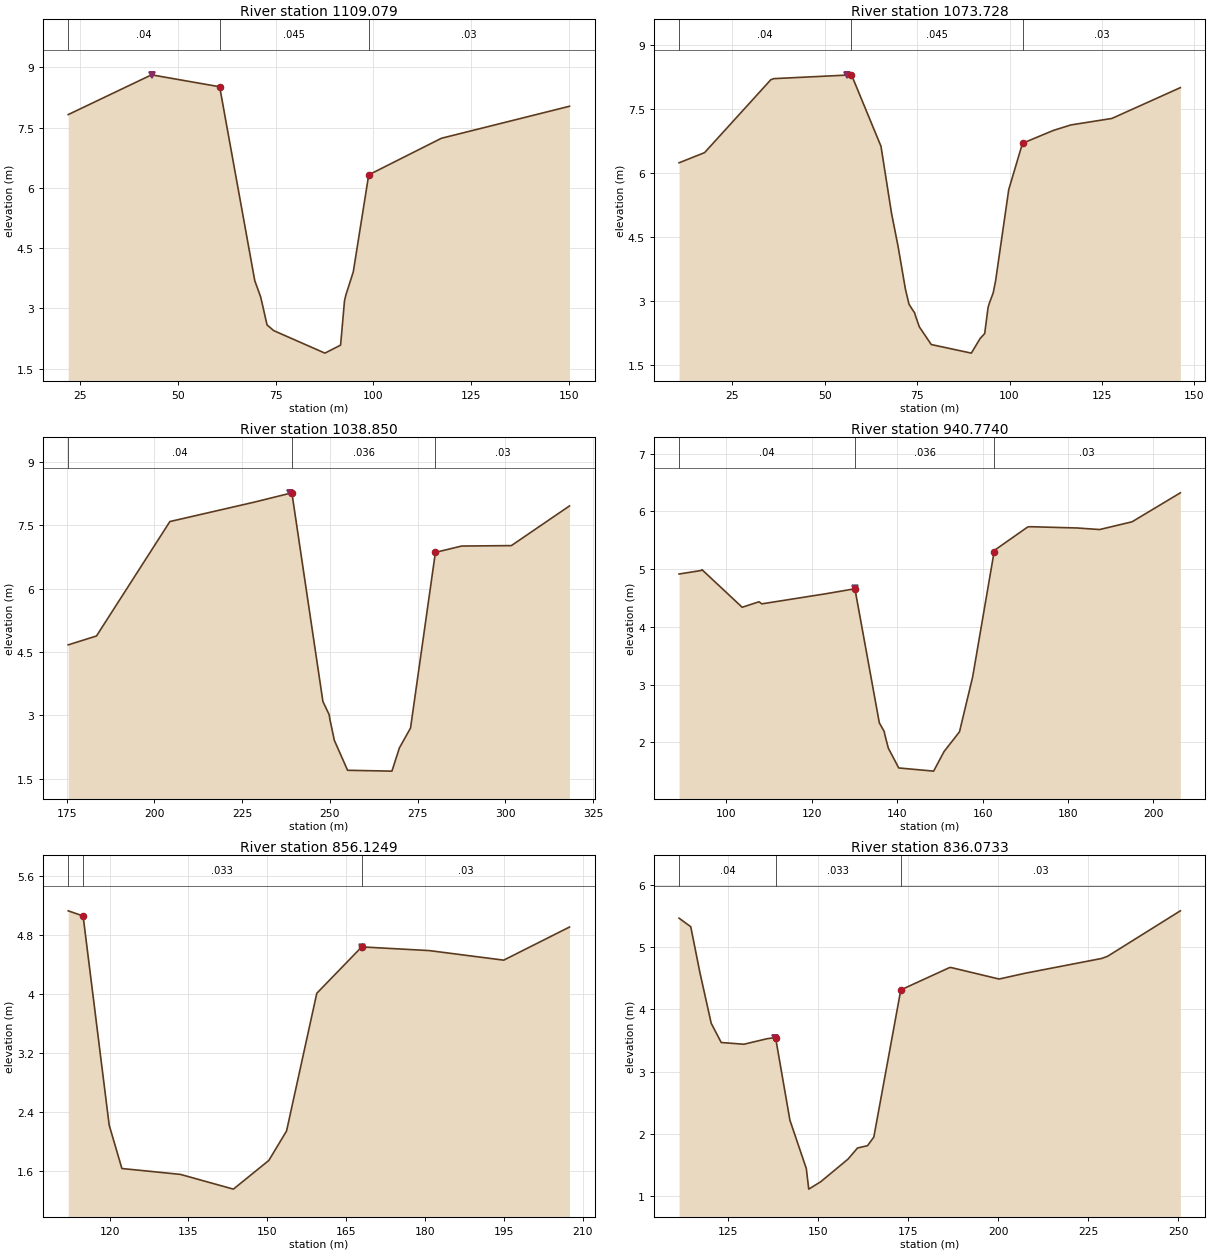
Type RM Length L Ch R = 1 ,1109.079,14.535,35.351,37.238
BEGIN DESCRIPTION:
2008 Survey Section
END DESCRIPTION:
Node Name=BB8
XS GIS Cut Line= 2
299337.5536422835378578.67410541299279.4347148645378692.83831755
#Sta/Elev= 16
      22  7.8266  43.288  8.8167  60.701  8.5196  69.681  3.6886  71.157  3.2922
  71.513  3.1466   72.81  2.5897  74.521   2.447  87.603   1.887  91.603   2.086
  92.603  3.1863  92.952  3.3331  94.847  3.9095  98.793  6.3259 117.365  7.2368
 150.107  8.0342
#Mann= 3 , 0 , 0
      22     .04       0  60.701    .045       0  98.793     .03       0
Levee=-1,43.46,8.8,0,,,,
Bank Sta=60.701,98.793
XS Rating Curve= 0 ,0
Exp/Cntr=0.3,0.1

Type RM Length L Ch R = 1 ,1073.728,15.434,34.878,36.514
BEGIN DESCRIPTION:
Interpolated Section
END DESCRIPTION:
Node Name=BB7a
XS GIS Cut Line= 2
299339.5825045725378565.28433151299234.883828444 5378651.3353084
#Sta/Elev= 30
  10.653   6.238  17.548   6.476  35.468   8.183  36.292   8.208  56.095   8.291
  57.264   8.297  65.243   6.624  68.079   5.063  69.857   4.283  70.285    4.07
  71.847    3.28  72.815   2.929  73.908   2.779  74.331   2.728  74.537   2.664
  75.607   2.398  78.837   1.984  89.664   1.783  92.043   2.125   93.28   2.241
  94.184   2.848    94.5   2.942  95.583   3.195  96.213   3.467  99.781   5.611
 103.502   6.695 111.867   6.996 116.573   7.124  127.67   7.276 146.176   7.997
#Mann= 3 , 0 , 0
  10.653     .04       0  57.264    .045       0 103.502     .03       0
Levee=-1,56.09,8.29,0,,,,
Bank Sta=57.264,103.502
XS Rating Curve= 0 ,0
Exp/Cntr=0.3,0.1

Type RM Length L Ch R = 1 ,1038.850,97.122,98.076,97.578
BEGIN DESCRIPTION:
2008 Survey Section
END DESCRIPTION:
Node Name=BB7
XS GIS Cut Line= 2
299346.6748915995378558.28651821299210.1001466295378600.12819631
#Sta/Elev= 17
 175.444    4.67 183.494    4.88 204.414    7.59 228.494    8.05 239.174    8.27
 248.014    3.33 249.784    3.02 250.024     2.9 251.274    2.41 255.044     1.7
 267.684    1.68 269.814    2.23 272.984     2.7 280.074    6.86 287.564    7.01
 301.714    7.02 318.284    7.96
#Mann= 3 , 0 , 0
 175.444     .04       0 239.174    .036       0 280.074     .03       0
Levee=-1,238.7,8.26,0,,,,
Bank Sta=239.174,280.074
XS Rating Curve= 0 ,0
Exp/Cntr=0.3,0.1

Type RM Length L Ch R = 1 ,940.7740,81.937,84.649,84.827
BEGIN DESCRIPTION:
Interpolated Section
END DESCRIPTION:
Node Name=BB6a
XS GIS Cut Line= 2
299289.5190004735378475.50399297  299176.63230175378507.59647093
#Sta/Elev= 27
   88.93   4.917  94.131   4.978  94.298   4.992 103.705   4.341 107.647   4.436
 108.295     4.4 123.204   4.574 129.424   4.653 130.104   4.659 135.816   2.339
 136.959   2.189 137.114   2.132 137.922   1.901 140.358   1.558 148.524   1.503
 150.956   1.841 154.575   2.183 154.621   2.196 157.665   3.135 162.669   5.293
 162.859   5.332 170.583   5.733 171.219   5.736 182.172   5.714 187.373   5.687
  194.98   5.821  206.29   6.323
#Mann= 3 , 0 , 0
   88.93     .04       0 130.104    .036       0 162.669     .03       0
Levee=-1,130.08,4.68,0,,,,
Bank Sta=130.104,162.669
XS Rating Curve= 0 ,0
Exp/Cntr=0.3,0.1

Type RM Length L Ch R = 1 ,856.1249,20.593,20.052,19.351
BEGIN DESCRIPTION:
2008 Survey Section
END DESCRIPTION:
Node Name=BB6
XS GIS Cut Line= 2
299262.0412684325378398.81673008 299169.088876585378420.15556043
#Sta/Elev= 13
 112.121    5.13 114.951    5.06 119.911    2.22 122.331    1.63 133.471    1.55
 143.541    1.35 150.291    1.74 153.661    2.14 159.411    4.01 167.961    4.64
 180.791    4.59 194.971    4.46 207.491    4.91
#Mann= 3 , 0 , 0
 112.121     .04       0 114.951    .033       0 167.961     .03       0
Levee=0,,,-1,167.98,4.63,,
Bank Sta=114.951,167.961
XS Rating Curve= 0 ,0
Exp/Cntr=0.3,0.1

Type RM Length L Ch R = 1 ,836.0733,22.384,21.424,19.965
BEGIN DESCRIPTION:
Interpolated Section
END DESCRIPTION:
Node Name=BB5a
XS GIS Cut Line= 2
299268.8219511995378376.18757931299134.3559988055378411.67550076
#Sta/Elev= 25
  111.46   5.464   114.7   5.327 117.229   4.595  120.38   3.778 123.151    3.47
 129.445   3.442 135.907   3.531 138.226    3.55 142.215   2.223  146.76   1.448
 147.438   1.118 150.789   1.238  158.32   1.599 160.976   1.778 163.752   1.815
 165.493   1.954 172.955   4.308 173.022   4.315   186.4   4.669 186.805   4.674
  200.25   4.488 207.488   4.581 228.713   4.818 230.347   4.853  250.53   5.582
#Mann= 3 , 0 , 0
  111.46     .04       0 138.226    .033       0 173.022     .03       0
Levee=-1,138.2,3.55,0,,,,
Bank Sta=138.226,173.022
XS Rating Curve= 0 ,0
Exp/Cntr=0.3,0.1

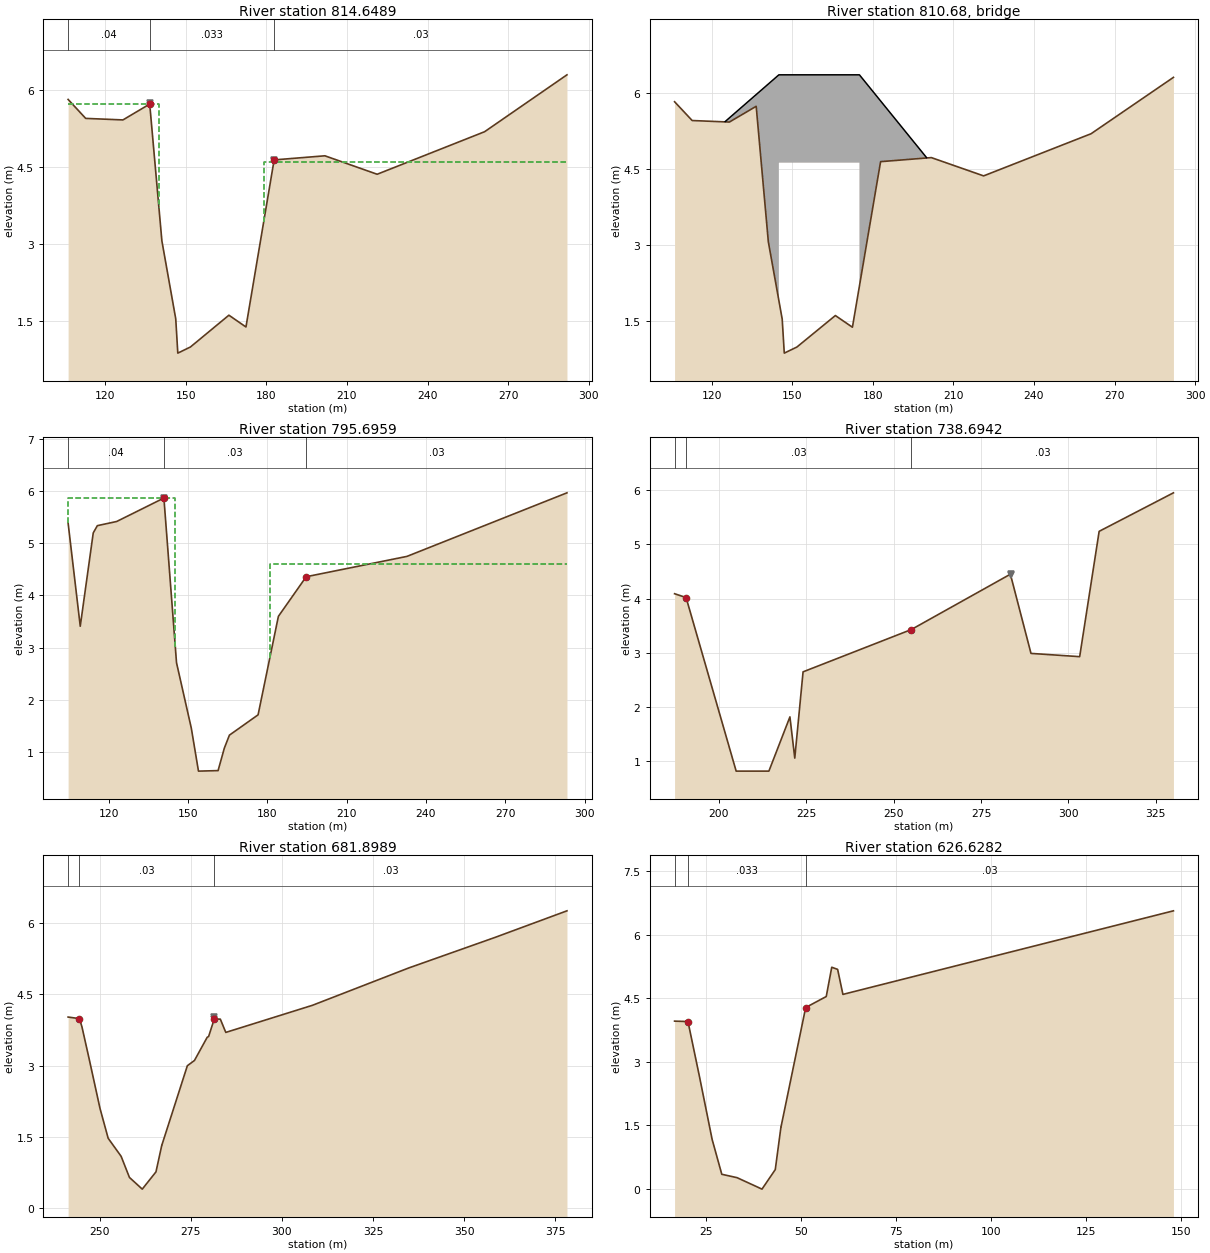
Type RM Length L Ch R = 1 ,814.6489,18.459,18.953,19.95
BEGIN DESCRIPTION:
2008 Survey Section
END DESCRIPTION:
Node Name=BB5
XS GIS Cut Line= 2
299276.9551404685378350.11388619  299099.7180702 5378405.7680387
#Sta/Elev= 15
 106.164    5.82 112.714    5.45 126.584    5.42 136.554    5.73 141.084    3.06
 146.244    1.54 147.014     .87 151.724     .99 166.044    1.61 172.394    1.38
 182.884    4.64 201.784    4.72 221.254    4.36 261.264    5.19 291.934     6.3
#Mann= 3 , 0 , 0
 106.164     .04       0 136.554    .033       0 182.884     .03       0
Levee=-1,136.59,5.75,-1,182.82,4.63,,
#XS Ineff= 2 , 0
       0     140    5.73     179       0     4.6
Permanent Ineff=
       F       F
Bank Sta=136.554,182.884
XS Rating Curve= 0 ,0
Exp/Cntr=0.5,0.3

Type RM Length L Ch R = 3 ,810.68  ,,,
BEGIN DESCRIPTION:
West Street Bridge
END DESCRIPTION:
Bridge Culvert--1,0,-1,-1, 0
Deck Dist Width WeirC Skew NumUp NumDn MinLoCord MaxHiCord MaxSubmerge Is_Ogee
3.97,11.06,1.6,0, 6, 6, , , 0.98, 0, 1,1,,
     125     145     145     175     175     200
    5.43    6.35    6.35    6.35    6.35    4.72
       0       0    4.62    4.62       0       0
  123.09     148     148     178     178   210.5
    5.42    6.35    6.35    6.35    6.35    4.52
       0       0    4.62    4.62       0       0
BR Coef=-1 , 0 , 0 ,, 0 ,,,0.8,-1,,0,
WSPro=,,,, 1 ,,,, 0 ,,,, 0 ,,,,-1 ,-1 ,-1 , 0 , 0 , 0 , 0 , 0
BC Design=,, 0 ,, 0 ,,,,,,
BC Use User HTab Curves=0
BC User HTab FreeFlow(D)= 0

Type RM Length L Ch R = 1 ,795.6959,71.29,57.002,36.886
BEGIN DESCRIPTION:
2008 Survey Section
END DESCRIPTION:
Node Name=BB4
XS GIS Cut Line= 3
299273.9015670265378331.84785611299103.7365074265378384.85630912
299093.8644150325378387.93158407
#Sta/Elev= 17
  104.72    5.39  109.31    3.41  114.22     5.2  115.77    5.34  123.09    5.42
  140.93    5.87   145.7    2.71  151.31    1.45     154     .63  161.41     .64
  163.77    1.07  165.69    1.32  176.53    1.71  184.21     3.6  194.72    4.36
  232.79    4.75  293.29    5.97
#Mann= 3 , 0 , 0
  104.72     .04       0  140.93     .03       0  194.72     .03       0
Levee=-1,140.88,5.86,0,,,,
#XS Ineff= 2 , 0
       0   145.3    5.87     181       0     4.6
Permanent Ineff=
       F       F
Bank Sta=140.93,194.72
XS Rating Curve= 0 ,0
Exp/Cntr=0.5,0.3

Type RM Length L Ch R = 1 ,738.6942,67.074,56.795,41.781
BEGIN DESCRIPTION:
2008 Survey Section
END DESCRIPTION:
Node Name=BB3
XS GIS Cut Line= 3
299199.8787955965378292.15458574299107.6693190495378383.02553655
299098.282487735 5378392.2761073
#Sta/Elev= 13
  187.38    4.09  190.67    4.02  204.99     .82  214.35     .82  220.36    1.82
  221.75    1.06  224.12    2.65  255.08    3.43   283.4    4.45  289.29    2.99
  303.21    2.93  308.78    5.24  330.02    5.95
#Mann= 3 , 0 , 0
  187.38     .04       0  190.67     .03       0  255.08     .03       0
Levee=0,,,-1,283.48,4.45,,
Bank Sta=190.67,255.08
XS Rating Curve= 0 ,0
Exp/Cntr=0.3,0.1

Type RM Length L Ch R = 1 ,681.8989,63.606,55.271,49.993
BEGIN DESCRIPTION:
Interpolated Section
END DESCRIPTION:
Node Name=BB2a
XS GIS Cut Line= 3
299139.2552421285378276.84543925299090.8326266115378398.15095988
299088.4799503045378404.04474776
#Sta/Elev= 23
 241.292   4.024 244.413   3.991 245.096   3.817 247.056   3.149 250.043   2.104
 252.289   1.474 255.851   1.094  258.13     .65 261.649    .404 265.414    .767
 267.017   1.329 267.028   1.329  274.03       3 275.983   3.111  279.49     3.6
  279.86   3.613  281.42   3.983 283.087    3.98 284.582   3.701 308.363   4.271
 334.773   5.056 358.443   5.698 378.251   6.259
#Mann= 3 , 0 , 0
 241.292     .04       0 244.413     .03       0  281.42     .03       0
Levee=0,,,-1,281.4,4.03,,
Bank Sta=244.413,281.42
XS Rating Curve= 0 ,0
Exp/Cntr=0.3,0.1

Type RM Length L Ch R = 1 ,626.6282,58.72,61.011,61.078
BEGIN DESCRIPTION:
2008 Survey Section
END DESCRIPTION:
Node Name=BB2
XS GIS Cut Line= 2
299082.5492337485378262.56919484299085.0328686995378393.97606229
#Sta/Elev= 16
  16.645    3.96  20.175    3.95  23.165    2.67  26.545    1.17  29.085     .35
  33.115     .27  39.675       0  43.175     .46  44.665    1.46  44.675    1.46
  51.185    4.28  56.605    4.54  58.055    5.23  59.605    5.18  60.995    4.59
 148.075    6.56
#Mann= 3 , 0 , 0
  16.645     .04       0  20.175    .033       0  51.185     .03       0
Bank Sta=20.175,51.185
XS Rating Curve= 0 ,0
Exp/Cntr=0.3,0.1

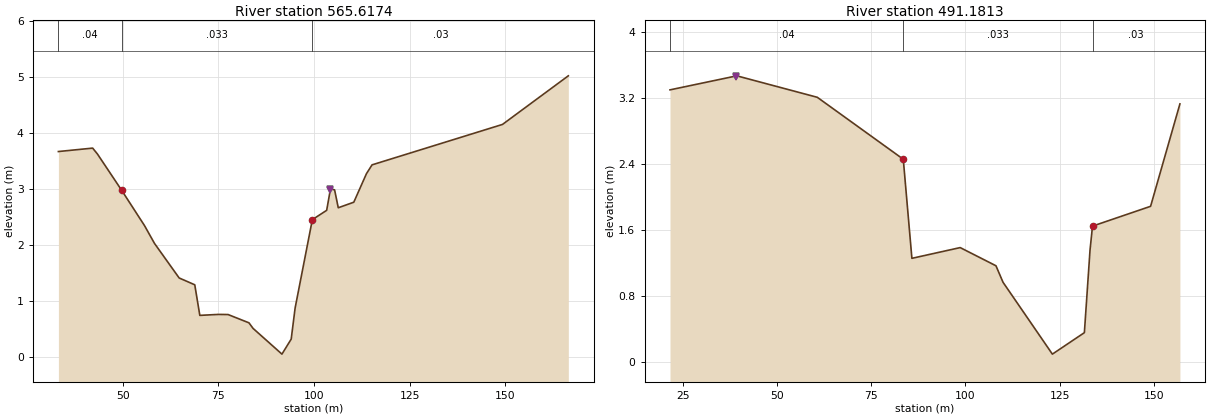
Type RM Length L Ch R = 1 ,565.6174,73.909,74.436,75.815
BEGIN DESCRIPTION:
Interpolated Section
END DESCRIPTION:
Node Name=BB1a
XS GIS Cut Line= 2
299027.9215376945378232.95440991 299015.484348895378365.61775714
#Sta/Elev= 26
  33.236   3.663  42.189   3.724  43.443   3.618  49.773    2.97  55.737    2.34
  58.345   2.022  64.788   1.405   68.87   1.283  70.187    .737  75.009    .754
  77.565    .752  83.028    .604  84.109    .504  91.647    .045  94.064    .313
  95.092    .869  99.593   2.447 103.335   2.613 104.336   2.998 105.406   2.978
 106.366   2.659 110.422   2.758 113.735   3.268 115.193   3.425 149.275   4.147
 166.481   5.015
#Mann= 3 , 0 , 0
  33.236     .04       0  49.773    .033       0  99.593     .03       0
Levee=0,,,-1,104.3,3,,
Bank Sta=49.773,99.593
XS Rating Curve= 0 ,0
Exp/Cntr=0.3,0.1

Type RM Length L Ch R = 1 ,491.1813,180,200,230
BEGIN DESCRIPTION:
2008 Survey Section
END DESCRIPTION:
Node Name=BB1
XS GIS Cut Line= 2
298957.0029866265378194.29174627298946.2925461565378329.32729963
#Sta/Elev= 14
  21.503     3.3  39.253    3.47  60.633    3.21  83.473    2.46  85.763    1.26
  98.593    1.39 108.093    1.17 109.973     .97 123.083      .1 131.583     .36
 133.083    1.36 133.743    1.65 149.173    1.89 156.963    3.13
#Mann= 3 , 0 , 0
  21.503     .04       0  83.473    .033       0 133.743     .03       0
Levee=-1,39.15,3.46,0,,,,
Bank Sta=83.473,133.743
XS Rating Curve= 0 ,0
Exp/Cntr=0.3,0.1

--- Blanche_Brook.g07 (geometry) ---

Geom Title=Base Case - 20% n
Program Version=4.00

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
River Reach=Blanche Brook   ,US of Confluence

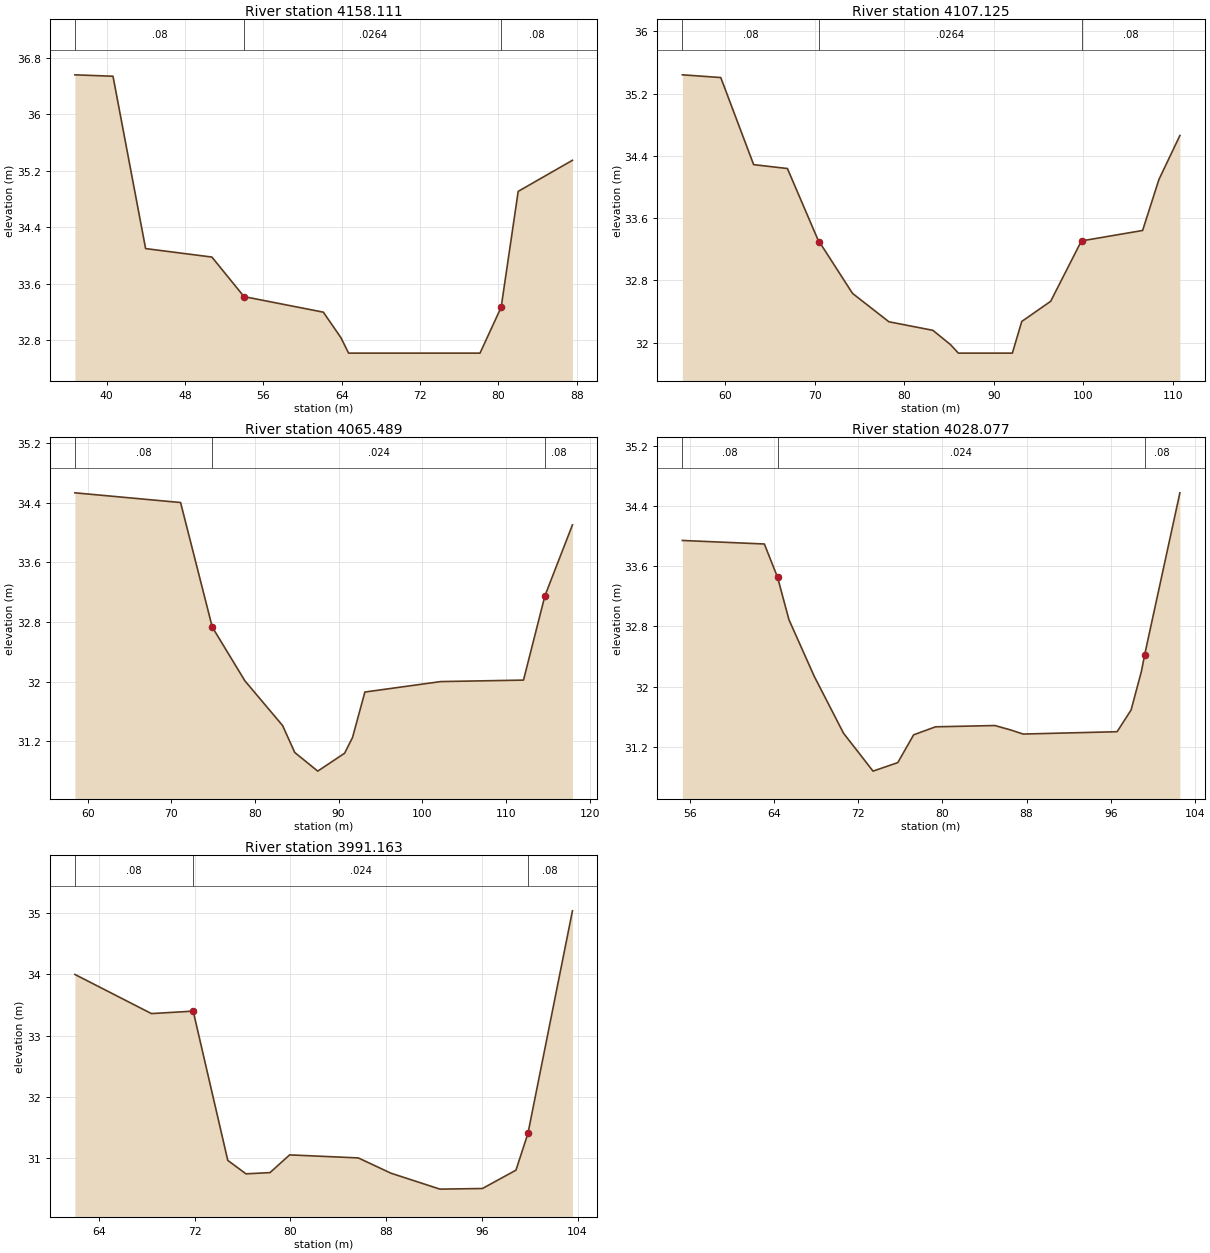
Type RM Length L Ch R = 1 ,4158.111,56.608,50.986,38.986
BEGIN DESCRIPTION:
2008 Survey Section
END DESCRIPTION:
Node Name=BB39
XS GIS Cut Line= 2
298673.7152083715380853.34084345 298671.076662985380802.59958592
#Sta/Elev= 12
  36.751   36.56  40.641   36.54  43.971    34.1  50.741   33.98  54.021   33.42
  62.121    33.2  63.911   32.84  64.701   32.62  78.121   32.62  80.281   33.27
  82.021   34.91  87.561   35.35
#Mann= 3 , 0 , 0
  36.751     .08       0  54.021   .0264       0  80.281     .08       0
Bank Sta=54.021,80.281
XS Rating Curve= 0 ,0
Exp/Cntr=0.3,0.1

Type RM Length L Ch R = 1 ,4107.125,48.237,41.636,33.727
BEGIN DESCRIPTION:
Interpolated Section
END DESCRIPTION:
Node Name=BB38a
XS GIS Cut Line= 2
298722.5515181345380829.68306117298690.4697829215380784.29914307
#Sta/Elev= 20
  55.202  35.442  59.493  35.407  63.166  34.288  66.938  34.238  70.459  33.293
  70.634  33.273  74.083  32.656  74.251   32.63  78.273  32.269  83.186  32.159
   85.16  31.975  86.032  31.866  92.064  31.866  93.117  32.273  96.346  32.532
   99.56  33.258  99.796  33.308 106.615  33.442 108.438  34.097  110.78  34.662
#Mann= 3 , 0 , 0
  55.202     .08       0  70.459   .0264       0  99.796     .08       0
Bank Sta=70.459,99.796
XS Rating Curve= 0 ,0
Exp/Cntr=0.3,0.1

Type RM Length L Ch R = 1 ,4065.489,38.598,37.412,37.41
BEGIN DESCRIPTION:
2008 Survey Section
END DESCRIPTION:
Node Name=BB38
XS GIS Cut Line= 2
298755.4837313625380786.51361197 298700.593541525380763.62888025
#Sta/Elev= 14
  58.474   34.53  71.104    34.4  74.894   32.73  78.794   32.01  83.304   31.41
   84.75   31.05    87.5    30.8   90.71   31.04  91.654   31.25  93.134   31.86
 102.184      32 112.094   32.02 114.654   33.15 117.944    34.1
#Mann= 3 , 0 , 0
  58.474     .08       0  74.894    .024       0 114.654     .08       0
Bank Sta=74.894,114.654
XS Rating Curve= 0 ,0
Exp/Cntr=0.3,0.1

Type RM Length L Ch R = 1 ,4028.077,36.768,36.914,37.219
BEGIN DESCRIPTION:
Interpolated Section
END DESCRIPTION:
Node Name=BB37a
XS GIS Cut Line= 2
298751.6701636045380744.77469999298708.0944586265380726.52001277
#Sta/Elev= 19
  55.314  33.941  63.101  33.894  64.351  33.453  65.438  32.889  67.842  32.137
  70.622  31.382  71.835  31.165   73.42   30.88   75.77  30.993  77.278  31.362
  79.355  31.468  84.991  31.485    86.5  31.426  87.672  31.372  96.598  31.403
  97.924  31.691  98.906  32.204  99.206   32.42 102.559  34.573
#Mann= 3 , 0 , 0
  55.314     .08       0  64.351    .024       0  99.206     .08       0
Bank Sta=64.351,99.206
XS Rating Curve= 0 ,0
Exp/Cntr=0.3,0.1

Type RM Length L Ch R = 1 ,3991.163,44.678,43.318,41.969
BEGIN DESCRIPTION:
2008 Survey Section
END DESCRIPTION:
Node Name=BB37
XS GIS Cut Line= 3
298764.9254170855380712.09629316298759.2073460725380709.23725765
298727.7416325775380693.50440091
#Sta/Elev= 14
      62      34  68.393   33.36  71.883    33.4  74.773   30.96  76.293   30.74
    78.3   30.76  79.943   31.05  85.683      31  88.413   30.75    92.5   30.49
   96.05    30.5  98.853    30.8  99.853    31.4 103.573   35.04
#Mann= 3 , 0 , 0
      62     .08       0  71.883    .024       0  99.853     .08       0
Bank Sta=71.883,99.853
XS Rating Curve= 0 ,0
Exp/Cntr=0.3,0.1