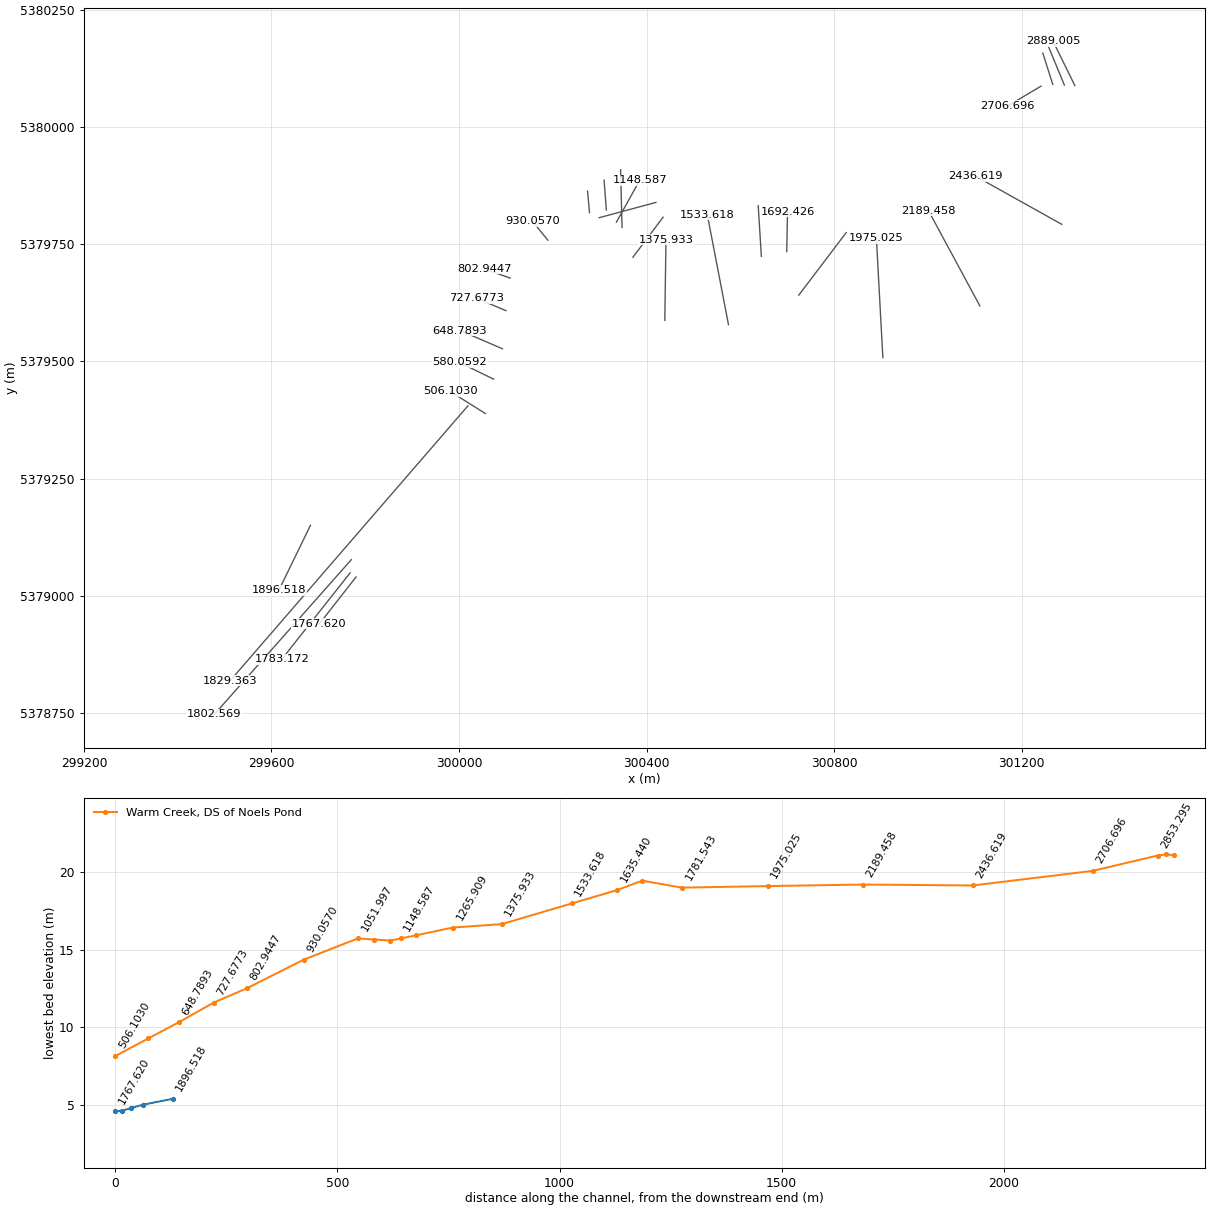
HEC-RAS study Blanche_Brook.prj: Stephenville Model

--- Blanche_Brook.g07 (geometry) --- (continued)

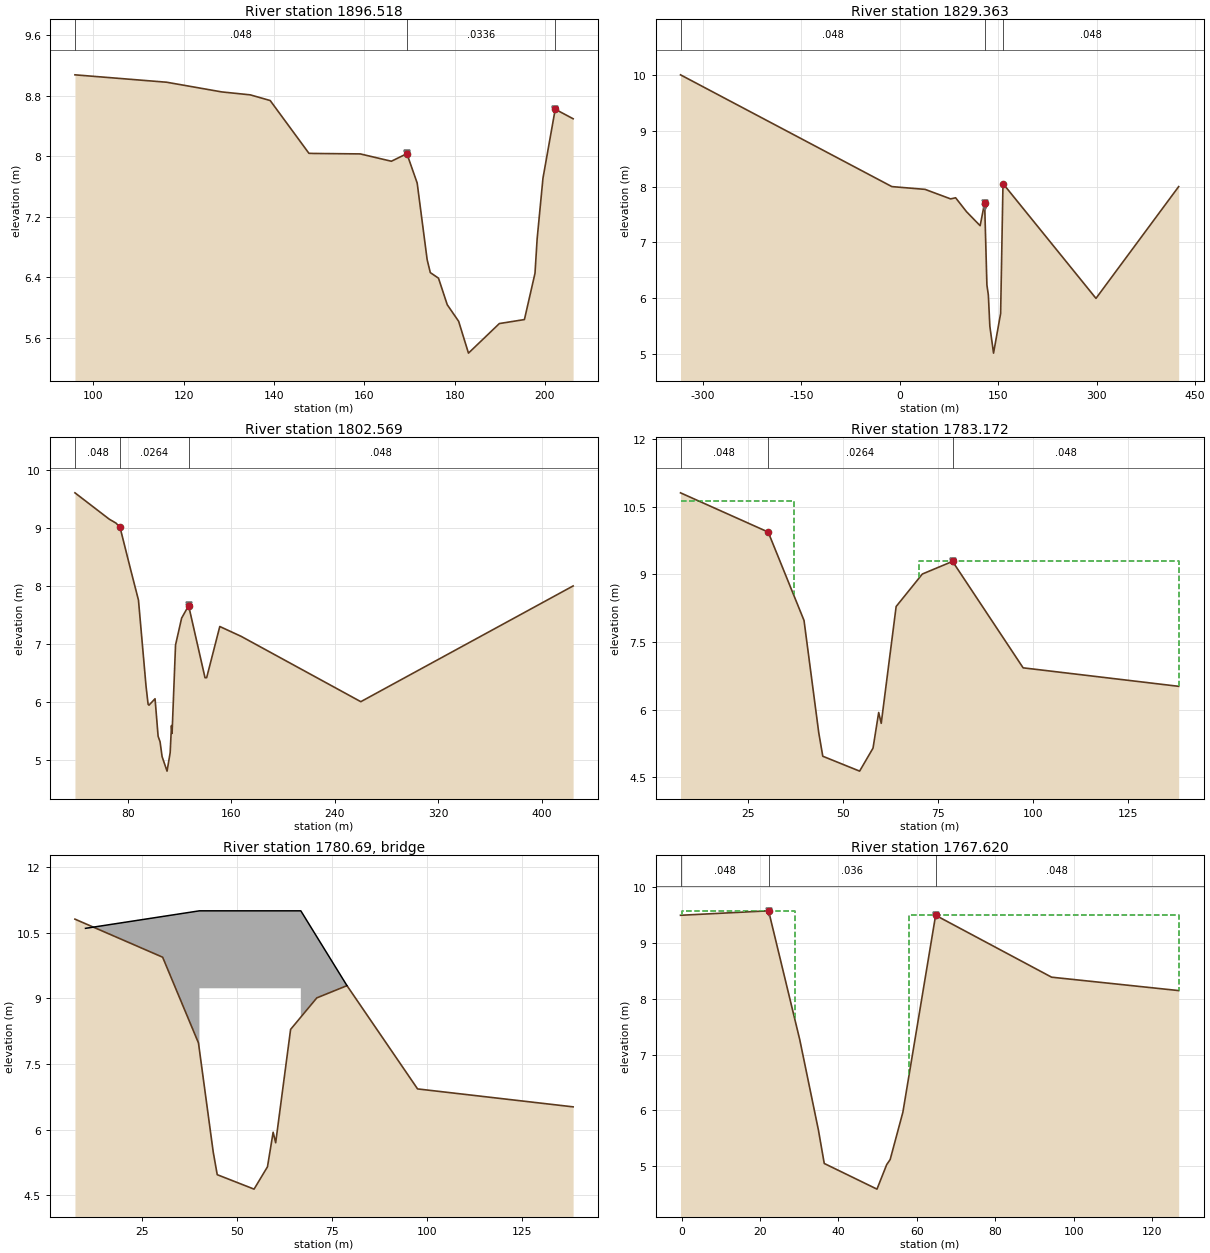
Type RM Length L Ch R = 1 ,1896.518,77.456,67.155,64.169
BEGIN DESCRIPTION:
Interpolated Section
END DESCRIPTION:
Node Name=BB14a
XS GIS Cut Line= 2
299683.0450958425379150.14230296299615.5339537075379011.49038739
#Sta/Elev= 25
  95.913   9.077 116.225   8.979 128.421   8.851  134.74   8.812 139.148   8.737
 147.726   8.039 148.666   8.037 159.088   8.031 165.986   7.934 169.418   8.034
 171.695   7.646 173.906   6.632 174.604   6.461 176.379   6.389 176.443   6.383
 178.357   6.036 180.879   5.817 183.055   5.396  189.89   5.787 195.446    5.84
  197.79   6.453  198.26   6.906 199.553    7.71 202.267   8.622  206.23   8.496
#Mann= 3 , 0 , 0
  95.913    .048       0 169.418   .0336       0 202.267    .048       0
Levee=-1,169.43,8.04,-1,202.25,8.62,,
Bank Sta=169.418,202.267
XS Rating Curve= 0 ,0
Exp/Cntr=0.3,0.1

Type RM Length L Ch R = 1 ,1829.363,25.942,26.793,25.989
BEGIN DESCRIPTION:
2008 Survey Section
END DESCRIPTION:
Node Name=BB14
XS GIS Cut Line= 4
 300018.941218095379405.12798696299775.1360805385379123.25360864
299683.6317775725379017.46125836299512.3234784755378819.40382285
#Sta/Elev= 17
    -334      10     -12       8  38.685    7.95  77.575    7.78  85.135     7.8
 101.795    7.55 122.515     7.3 129.345    7.71 132.825    6.24 135.025    6.06
 137.315     5.5 142.935    5.02 153.735    5.73 157.315    8.04 163.135    7.97
     299       6     425       8
#Mann= 3 , 0 , 0
    -334    .048       0 129.345   .0264       0 157.315    .048       0
Levee=-1,129.53,7.71,0,,,,
Bank Sta=129.345,157.315
XS Rating Curve= 0 ,0
Exp/Cntr=0.3,0.1

Type RM Length L Ch R = 1 ,1802.569,18.545,19.397,20.067
BEGIN DESCRIPTION:
Interpolated Section
END DESCRIPTION:
Node Name=BB13a
XS GIS Cut Line= 3
299770.3005188575379077.14364587 299647.980331885378938.98585892
299477.9950323325378746.99144345
#Sta/Elev= 26
   39.21   9.609   65.75   9.153  70.909   9.086  74.035   9.012  82.278   8.278
  88.273   7.755  94.125   6.267  95.724   5.954  96.418    5.94 101.079   6.051
 103.454   5.402 104.956   5.307 106.518   5.051 110.354     4.8 112.758   5.119
 113.772   5.587 114.228   5.452 116.905    6.98 121.603   7.444 127.017   7.659
 139.676   6.414 140.944   6.415 151.084   7.299 167.569   7.129     260       6
     424       8
#Mann= 3 , 0 , 0
   39.21    .048       0  74.035   .0264       0 127.017    .048       0
Levee=0,,,-1,127.25,7.67,,
Bank Sta=74.035,127.017
XS Rating Curve= 0 ,0
Exp/Cntr=0.3,0.1

Type RM Length L Ch R = 1 ,1783.172,15.654,15.552,15.894
BEGIN DESCRIPTION:
2008 Survey Section
END DESCRIPTION:
Node Name=BB13
XS GIS Cut Line= 3
299767.7410278315379048.98009851299675.7161904865378932.64681357
299621.7735092465378864.45512219
#Sta/Elev= 14
    7.22   10.81   30.31    9.94   39.75    7.98   43.63    5.49   44.69    4.97
   54.39    4.64   57.92    5.15   59.41    5.94   60.08     5.7   64.01    8.29
   70.91    9.01   78.86    9.29   97.45    6.93  138.41    6.52
#Mann= 3 , 0 , 0
    7.22    .048       0   30.31   .0264       0   78.86    .048       0
Levee=0,,,-1,78.94,9.29,,
#XS Ineff= 2 , 0
       0      37   10.63      70       0    9.29
Permanent Ineff=
       F       F
Bank Sta=30.31,78.86
XS Rating Curve= 0 ,0
Exp/Cntr=0.5,0.3

Type RM Length L Ch R = 3 ,1780.69 ,,,
BEGIN DESCRIPTION:
Minnesota Drive Bridge
END DESCRIPTION:
Bridge Culvert--1,0,-1,-1, 0
Deck Dist Width WeirC Skew NumUp NumDn MinLoCord MaxHiCord MaxSubmerge Is_Ogee
2.48,11.33,1.6,0, 6, 6, , , 0.98, 0, 1,1,,
      10      40      40    66.7    66.7   78.86
    10.6      11      11      11      11    9.29
       0       0    9.23    9.23       0       0
      10      30      30    56.7    56.7      78
    9.54      11      11      11      11    9.02
       0       0    9.23    9.23       0       0
BR Coef=-1 , 0 , 0 ,, 0 ,,,0.8,-1,,0,
WSPro=,,,, 1 ,,,, 0 ,,,, 0 ,,,,-1 ,-1 ,-1 , 0 , 0 , 0 , 0 , 0
BC Design=,, 0 ,, 0 ,,,,,,
BC Use User HTab Curves=0
BC User HTab FreeFlow(D)= 0

Type RM Length L Ch R = 1 ,1767.620,17.554,40.58,15.484
BEGIN DESCRIPTION:
2008 Survey Section
END DESCRIPTION:
Node Name=BB12
XS GIS Cut Line= 4
  299780.36883335379040.20944591   299780.192571  5379039.984218
299702.147574001  5378940.258348299702.0489681715378940.13234951
#Sta/Elev= 12
   -.286     9.5  22.184    9.58  30.134    7.27  34.894    5.65  36.384    5.05
  49.834    4.59  52.314    5.03  53.194    5.12  56.444    5.97  64.794     9.5
  94.384    8.39 126.794    8.15
#Mann= 3 , 0 , 0
   -.286    .048       0  22.184    .036       0  64.794    .048       0
Levee=-1,22.32,9.58,-1,64.93,9.5,,
#XS Ineff= 2 , 0
       0      29    9.58      58       0     9.5
Permanent Ineff=
       F       F
Bank Sta=22.184,64.794
XS Rating Curve= 0 ,0
Exp/Cntr=0.5,0.3

River Reach=Warm Creek      ,DS of Noels Pond

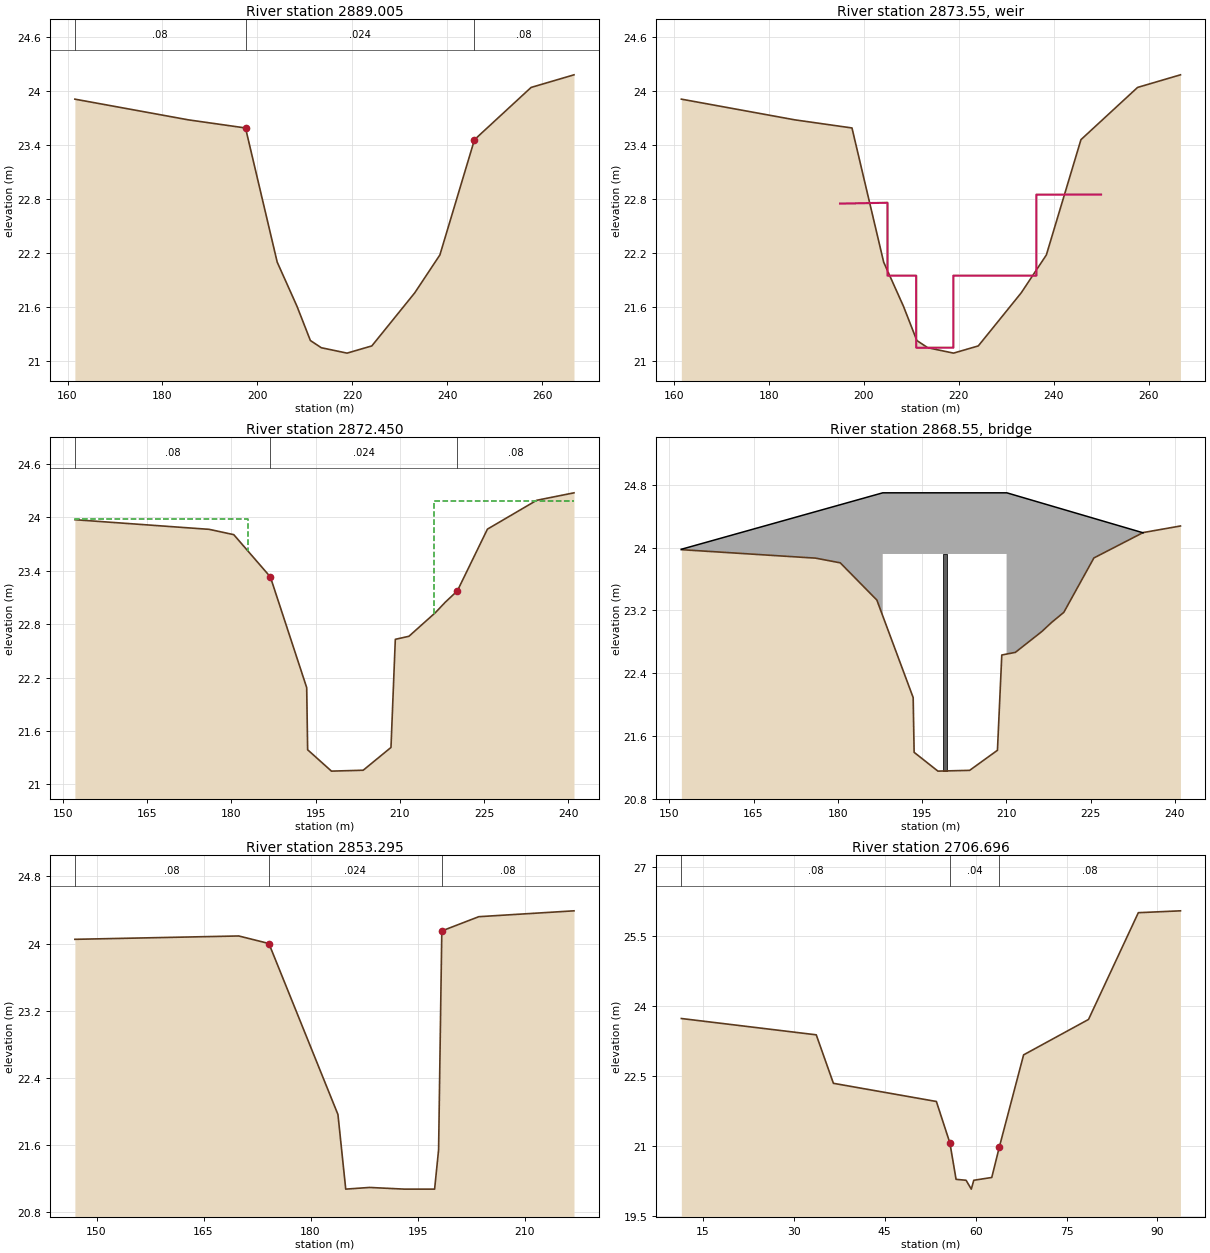
Type RM Length L Ch R = 1 ,2889.005,22.271,16.555,15.405
BEGIN DESCRIPTION:
2008 Survey Section
END DESCRIPTION:
Node Name=W23
XS GIS Cut Line= 2
301312.9991003265380088.10282464301266.6327960865380182.51132364
#Sta/Elev= 15
 161.553   23.91 185.483   23.68 197.513   23.59 204.193    22.1 208.363   21.61
 211.183   21.23  213.48   21.15  218.91   21.09  224.13   21.17 226.743   21.34
 233.183   21.76 238.473   22.18 245.763   23.46 257.693   24.04 266.733   24.18
#Mann= 3 , 0 , 0
 161.553     .08       0 197.513    .024       0 245.763     .08       0
Bank Sta=197.513,245.763
XS Rating Curve= 0 ,0
Exp/Cntr=0.3,0.1

Type RM Length L Ch R = 5 ,2873.55 ,,,
BEGIN DESCRIPTION:
Noel's Pond Outlet Weir
END DESCRIPTION:
IW Pilot Flow=0
#Inline Weir SE= 10
     195   22.75     205   22.76     205   21.95  211.05   21.95  211.05   21.15
  218.87   21.15  218.87   21.95  236.37   21.95  236.37   22.85     250   22.85
IW Dist,WD,Coef,Skew,MaxSub,Min_El,Is_Ogee,SpillHt,DesHd
15.46,0.5,1.7,0,0.98,, 0 ,,,0,1,

Type RM Length L Ch R = 1 ,2872.450,25.056,19.156,18.179
BEGIN DESCRIPTION:
Interpolated Section
END DESCRIPTION:
Node Name=W22a
XS GIS Cut Line= 2
301290.7424411895380089.00876538301256.8044458955380171.12447428
#Sta/Elev= 18
 152.153  23.975 175.314   23.87 176.041  23.867 180.439  23.807 186.957  23.332
 193.423  22.088  193.59   21.39  197.83   21.15  203.48   21.16 208.427  21.416
 209.199  22.631 211.621  22.665 216.353  22.932 218.091  23.048  220.24  23.175
 225.597  23.869 234.363  24.193 241.006  24.277
#Mann= 3 , 0 , 0
 152.153     .08       0 186.957    .024       0  220.24     .08       0
#XS Ineff= 2 , 0
       0     183   23.98     216       0   24.19
Permanent Ineff=
       F       F
Bank Sta=186.957,220.24
XS Rating Curve= 0 ,0
Exp/Cntr=0.5,0.3

Type RM Length L Ch R = 3 ,2868.55 ,,,
BEGIN DESCRIPTION:
Noel's Pond Outlet Bridge
END DESCRIPTION:
Bridge Culvert--1,0,-1,-1, 0
Deck Dist Width WeirC Skew NumUp NumDn MinLoCord MaxHiCord MaxSubmerge Is_Ogee
5,8.25,1.6,0, 6, 6, , , 0.98, 0, 1,1,,
  152.15     188     188   210.1   210.1  234.36
   23.98    24.7    24.7    24.7    24.7   24.19
       0       0   23.92   23.92       0       0
  146.96     176     176   198.1   198.1  216.93
   24.05    24.7    24.7    24.7    24.7   24.39
       0       0   23.92   23.92       0       0
Pier Skew, UpSta & Num, DnSta & Num=  ,199.07, 2 ,187.07, 2 , 0 , 0 , 0 ,,
     .74     .74
       0   23.92
     .74     .74
       0   23.92
BR Coef=-1 , 0 , 0 ,, 0 ,,,0.8,-1,,0,
WSPro=,,,, 1 ,,,, 0 ,,,, 0 ,,,,-1 ,-1 ,-1 , 0 , 0 , 0 , 0 , 0
BC Design=,, 0 ,, 0 ,,,,,,
BC Use User HTab Curves=0
BC User HTab FreeFlow(D)= 0

Type RM Length L Ch R = 1 ,2853.295,62.32,146.599,163.025
BEGIN DESCRIPTION:
2008 Survey Section
END DESCRIPTION:
Node Name=W22
XS GIS Cut Line= 2
 301265.992856035380090.46296967301244.8021192545380157.14710638
#Sta/Elev= 12
 146.959   24.05 169.929   24.09 174.159      24  183.84   21.96  184.93   21.07
  188.26   21.09 193.149   21.07  197.39   21.07 197.949   21.54 198.399   24.15
 203.579   24.32 216.929   24.39
#Mann= 3 , 0 , 0
 146.959     .08       0 174.159    .024       0 198.399     .08       0
Bank Sta=174.159,198.399
XS Rating Curve= 0 ,0
Exp/Cntr=0.5,0.3

Type RM Length L Ch R = 1 ,2706.696,280.29,270.077,227.593
BEGIN DESCRIPTION:
2008 Survey Section
END DESCRIPTION:
Node Name=W21
XS GIS Cut Line= 2
301240.8198410325380086.71513002301170.0227037365380044.65228316
#Sta/Elev= 15
  11.439   23.74  33.699   23.39  36.529   22.35  53.519   21.96  55.749   21.07
  56.768   20.29   58.42   20.27  59.279   20.08   59.69   20.27  62.658   20.33
  63.899   20.98  67.909   22.96  78.619   23.72  86.839   26.01  93.789   26.05
#Mann= 3 , 0 , 0
  11.439     .08       0  55.749     .04       0  63.899     .08       0
Bank Sta=55.749,63.899
XS Rating Curve= 0 ,0
Exp/Cntr=0.3,0.1

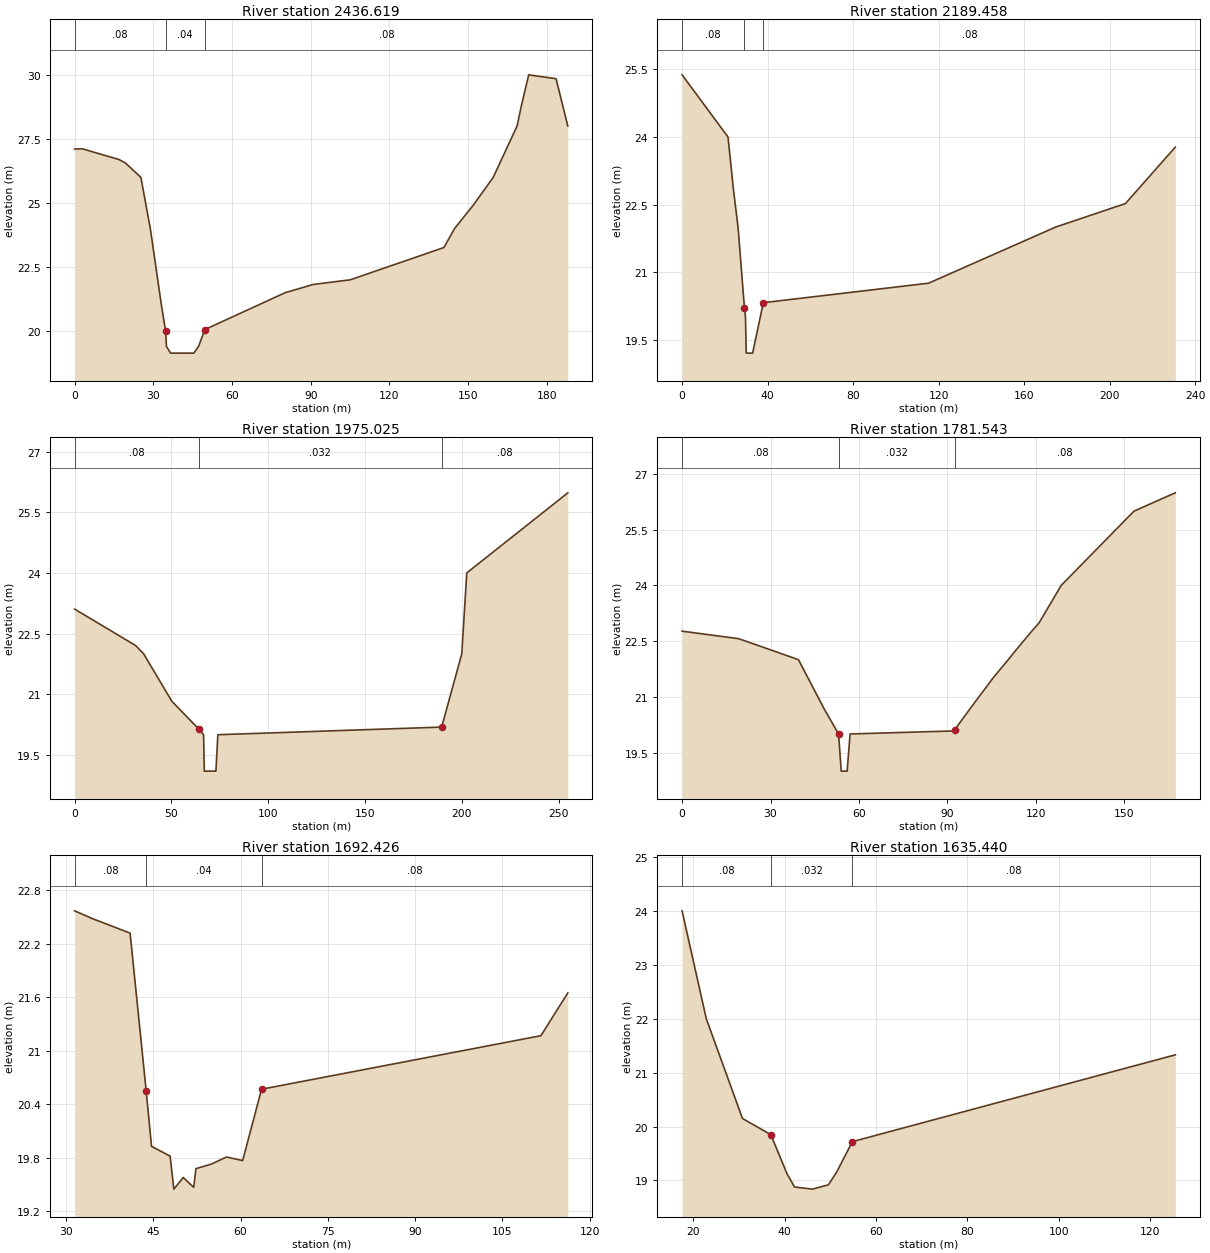
Type RM Length L Ch R = 1 ,2436.619,240.8,247.162,196.133
BEGIN DESCRIPTION:
1:2500 Community Mapping Section
END DESCRIPTION:
Node Name=W17d
XS GIS Cut Line= 5
301285.261793047 5379792.0819097301256.3901449445379808.20191322
301181.6138240435379849.95202573301164.1513104015379859.70192918
301101.3674640025379894.75624342
#Sta/Elev= 25
       0  27.104   2.885  27.115  16.972  26.693  19.403  26.557  25.264      26
  28.865      24  33.092  21.011  34.693      20      35    19.4   36.59   19.14
   45.47   19.14   47.28   19.41   49.64   20.06  80.203  21.496  90.826  21.817
 105.025      22 140.753  23.261 144.796      24 152.108  24.937 159.534      26
 168.622      28 170.209  28.767 173.052      30 183.477  29.848 187.963      28
#Mann= 3 , 0 , 0
       0     .08       0  34.693     .04       0   49.64     .08       0
Bank Sta=34.693,49.64
XS Rating Curve= 0 ,0
Exp/Cntr=0.3,0.1

Type RM Length L Ch R = 1 ,2189.458,205.74,214.433,169.067
BEGIN DESCRIPTION:
1:2500 Community Mapping Section
END DESCRIPTION:
Node Name=W17c
XS GIS Cut Line= 5
301110.5621804555379618.14852348301097.8412540975379641.72226813
 301065.276012115379702.07044384301058.1526354465379715.27110689
301000.991809398 5379821.1985118
#Sta/Elev= 13
       0   25.38  21.479      24  24.096  22.803  26.172      22   29.15  20.213
  29.661      20      30    19.2      33    19.2      38   20.32 115.294  20.753
 174.782      22 207.388  22.521 230.727  23.776
#Mann= 3 , 0 , 0
       0     .08       0   29.15    .032       0      38     .08       0
Bank Sta=29.15,38
XS Rating Curve= 0 ,0
Exp/Cntr=0.3,0.1

Type RM Length L Ch R = 1 ,1975.025,192.041,193.482,126.262
BEGIN DESCRIPTION:
1:2500 Community Mapping Section
END DESCRIPTION:
Node Name=W17b
XS GIS Cut Line= 4
300903.6810602775379507.81192605300900.2054420385379571.91777357
300895.6535312825379655.87523864  300889.88898565379762.19908123
#Sta/Elev= 13
       0  23.107   31.56  22.204  35.677      22  50.261  20.826    64.2  20.138
  66.628      20      67    19.1      73    19.1      74      20 189.606  20.189
 199.988      22 202.569      24 254.761   25.98
#Mann= 3 , 0 , 0
       0     .08       0    64.2    .032       0 189.606     .08       0
Bank Sta=64.2,189.606
XS Rating Curve= 0 ,0
Exp/Cntr=0.3,0.1

Type RM Length L Ch R = 1 ,1781.543,78.667,89.117,103.438
BEGIN DESCRIPTION:
1:2500 Community Mapping Section
END DESCRIPTION:
Node Name=W17a
XS GIS Cut Line= 4
300724.3840894575379641.13531461300754.6662697755379681.05273412
300805.7607267865379748.40451836300825.5259704355379774.45870317
#Sta/Elev= 27
       0  22.768  19.172  22.566   27.74  22.329  28.677  22.302  39.485      22
  48.226  20.672  50.104  20.413  53.089      20      54      19      56      19
      57      20  92.195  20.082  92.433  20.107  97.114  20.616  99.501  20.872
  104.32  21.381 105.422    21.5 110.658      22 113.998  22.328 116.841  22.598
 118.488  22.754 121.125  22.992 128.626      24 151.571  25.858 153.349      26
 166.061  26.448 167.346  26.492
#Mann= 3 , 0 , 0
       0     .08       0  53.089    .032       0  92.433     .08       0
Bank Sta=53.089,92.433
XS Rating Curve= 0 ,0
Exp/Cntr=0.3,0.1

Type RM Length L Ch R = 1 ,1692.426,55.271,56.986,58.395
BEGIN DESCRIPTION:
2008 Survey Section
END DESCRIPTION:
Node Name=W17
XS GIS Cut Line= 2
300698.6916769585379734.14148137300700.3620475935379818.87482816
#Sta/Elev= 16
  31.486   22.57  34.656   22.48  41.026   22.32   43.79   20.55  44.706   19.93
    47.9   19.82  48.546   19.45   50.16   19.58  51.956   19.47   52.34   19.68
  54.966   19.73   57.59   19.81  60.366   19.77  63.616   20.57 111.606   21.17
 116.236   21.65
#Mann= 3 , 0 , 0
  31.486     .08       0   43.79     .04       0  63.616     .08       0
Bank Sta=43.79,63.616
XS Rating Curve= 0 ,0
Exp/Cntr=0.3,0.1

Type RM Length L Ch R = 1 ,1635.440,99.483,101.822,103.873
BEGIN DESCRIPTION:
2008 Survey Section
END DESCRIPTION:
Node Name=W16
XS GIS Cut Line= 3
300644.5963847925379723.98834471300643.7766037925379737.19592749
300637.9019106085379831.84376211
#Sta/Elev= 11
    17.5      24    22.8      22  30.733   20.15  36.943   19.85  40.513   19.12
  42.143   18.88  46.033   18.84   49.57   18.92  51.393   19.16  54.803   19.72
 125.563   21.33
#Mann= 3 , 0 , 0
    17.5     .08       0  36.943    .032       0  54.803     .08       0
Bank Sta=36.943,54.803
XS Rating Curve= 0 ,0
Exp/Cntr=0.3,0.1

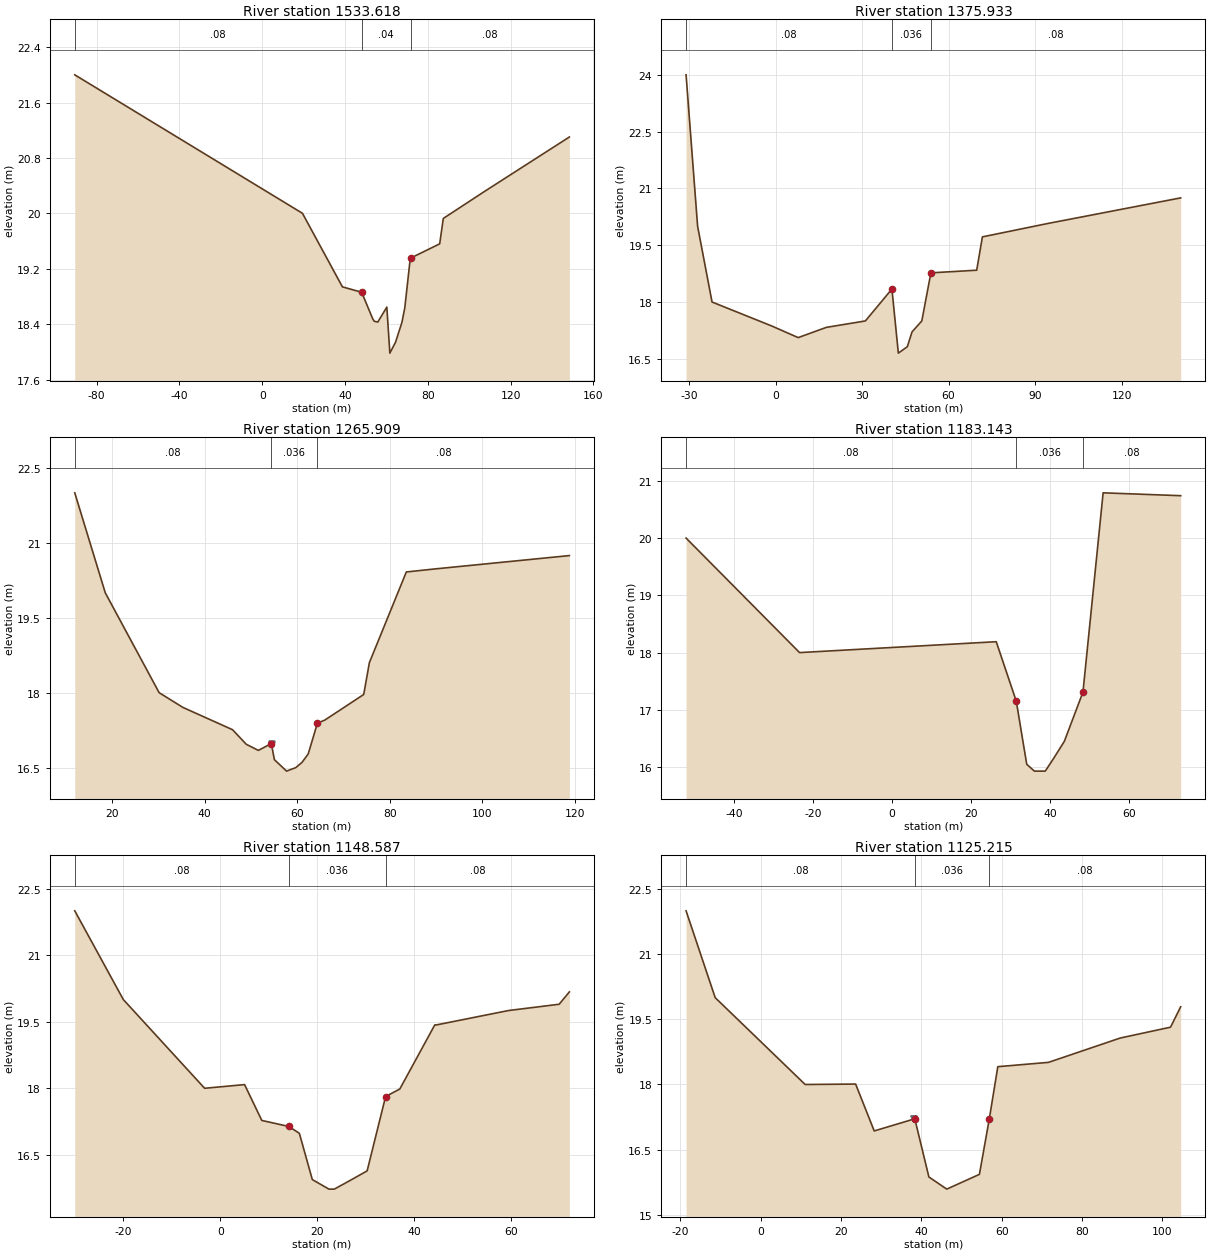
Type RM Length L Ch R = 1 ,1533.618,162.203,157.685,116.864
BEGIN DESCRIPTION:
Interpolated Section
END DESCRIPTION:
Node Name=W15a
XS GIS Cut Line= 3
300574.4828022915379578.24269088300550.0222001485379705.20486391
300529.2801185155379812.86614477
#Sta/Elev= 18
  -90.58      22   19.42      20  38.717  18.938  48.019   18.86  53.367  18.476
  54.091  18.441  55.809   18.43  60.177  18.646  61.636  17.981  64.392  18.139
  67.481  18.427  68.841  18.633  71.199   19.27  71.632  19.353  85.705  19.559
  87.451  19.926 107.319  20.315 148.358  21.102
#Mann= 3 , 0 , 0
  -90.58     .08       0  48.019     .04       0  71.632     .08       0
Bank Sta=48.019,71.632
XS Rating Curve= 0 ,0
Exp/Cntr=0.3,0.1

Type RM Length L Ch R = 1 ,1375.933,115.399,110.024,80.619
BEGIN DESCRIPTION:
2008 Survey Section
END DESCRIPTION:
Node Name=W15
XS GIS Cut Line= 4
300438.6961542185379587.56423744300439.2666163955379626.41905013
300439.5602225855379646.41689395300441.2129295155379758.98459923
#Sta/Elev= 19
     -31      24     -29      22     -27      20     -22      18   -1.41   17.37
   7.859   17.06   17.61   17.33  31.149    17.5   40.32   18.34  40.369   18.33
  42.579   16.65  45.689   16.82   47.32   17.21  50.709    17.5  53.859   18.77
  69.739   18.84  71.709   19.72  94.129   20.07 140.439   20.75
#Mann= 3 , 0 , 0
     -31     .08       0   40.32    .036       0  53.859     .08       0
Bank Sta=40.32,53.859
XS Rating Curve= 0 ,0
Exp/Cntr=0.3,0.1

Type RM Length L Ch R = 1 ,1265.909,88.883,82.766,73.503
BEGIN DESCRIPTION:
Interpolated Section
END DESCRIPTION:
Node Name=W14a
XS GIS Cut Line= 3
300370.6541418085379721.89731956300384.7266877325379740.56782603
300435.0195849435379807.29305599
#Sta/Elev= 21
    11.9      22   18.49      20   30.14      18   35.28  17.705  46.005  17.259
  48.973  16.967  51.589  16.845  54.394  16.982   55.05   16.66   57.68   16.43
   59.67    16.5  61.031  16.606  62.371  16.776  64.352  17.391  65.938  17.451
  74.342  17.963  74.403  17.986  75.581    18.6   83.57  20.416  89.684  20.476
 118.816  20.744
#Mann= 3 , 0 , 0
    11.9     .08       0  54.394    .036       0  64.352     .08       0
Levee=-1,54.46,16.97,0,,,,
Bank Sta=54.394,64.352
XS Rating Curve= 0 ,0
Exp/Cntr=0.3,0.1

Type RM Length L Ch R = 1 ,1183.143,20.173,34.556,39.04
BEGIN DESCRIPTION:
2008 Survey Section
END DESCRIPTION:
Node Name=W14
XS GIS Cut Line= 3
300298.9502244315379806.31093566300374.6881692135379826.69472821
300419.7251011965379838.81577904
#Sta/Elev= 12
   -52.1      20   -23.4      18  26.333   18.19  31.403   17.15  34.043   16.05
  35.983   15.93  38.723   15.93  40.823   16.15  43.553   16.45  48.263   17.31
  53.363   20.79  72.973   20.74
#Mann= 3 , 0 , 0
   -52.1     .08       0  31.403    .036       0  48.263     .08       0
Bank Sta=31.403,48.263
XS Rating Curve= 0 ,0
Exp/Cntr=0.3,0.1

Type RM Length L Ch R = 1 ,1148.587,12.279,23.372,25.348
BEGIN DESCRIPTION:
Interpolated Section
END DESCRIPTION:
Node Name=W13a
XS GIS Cut Line= 3
300335.5427684825379796.83576298300352.6128293185379827.48588301
300385.2597630775379886.10503194
#Sta/Elev= 21
  -30.06      22  -20.03      20   -3.23      18   5.023  18.083   8.579  17.275
   14.18  17.139  16.338  16.985  18.948  15.968  19.034  15.941  22.452  15.727
  23.558  15.727  26.535  15.905  30.337  16.138  30.406  16.167  34.156  17.814
  37.084  17.983  44.315  19.428  44.687  19.429  59.571  19.753   70.01  19.894
   72.12  20.173
#Mann= 3 , 0 , 0
  -30.06     .08       0   14.18    .036       0  34.156     .08       0
Bank Sta=14.18,34.156
XS Rating Curve= 0 ,0
Exp/Cntr=0.3,0.1

Type RM Length L Ch R = 1 ,1125.215,33.473,35.913,35.28
BEGIN DESCRIPTION:
2008 Survey Section
END DESCRIPTION:
Node Name=W13
XS GIS Cut Line= 4
300347.5260179465379785.28417287 300347.485885715379786.86366303
300346.4538013975379827.48355279300344.3981726435379908.38722733
#Sta/Elev= 15
  -18.58      22  -11.33      20   11.07      18  23.633   18.01  28.263   16.93
  38.363   17.21  41.873   15.87  46.323   15.59  54.453   15.93   56.92   17.21
  59.033   18.41  71.663   18.51  89.513   19.07 102.033   19.32 104.563   19.79
#Mann= 3 , 0 , 0
  -18.58     .08       0  38.363    .036       0   56.92     .08       0
Levee=-1,38.24,17.21,0,,,,
Bank Sta=38.363,56.92
XS Rating Curve= 0 ,0
Exp/Cntr=0.3,0.1

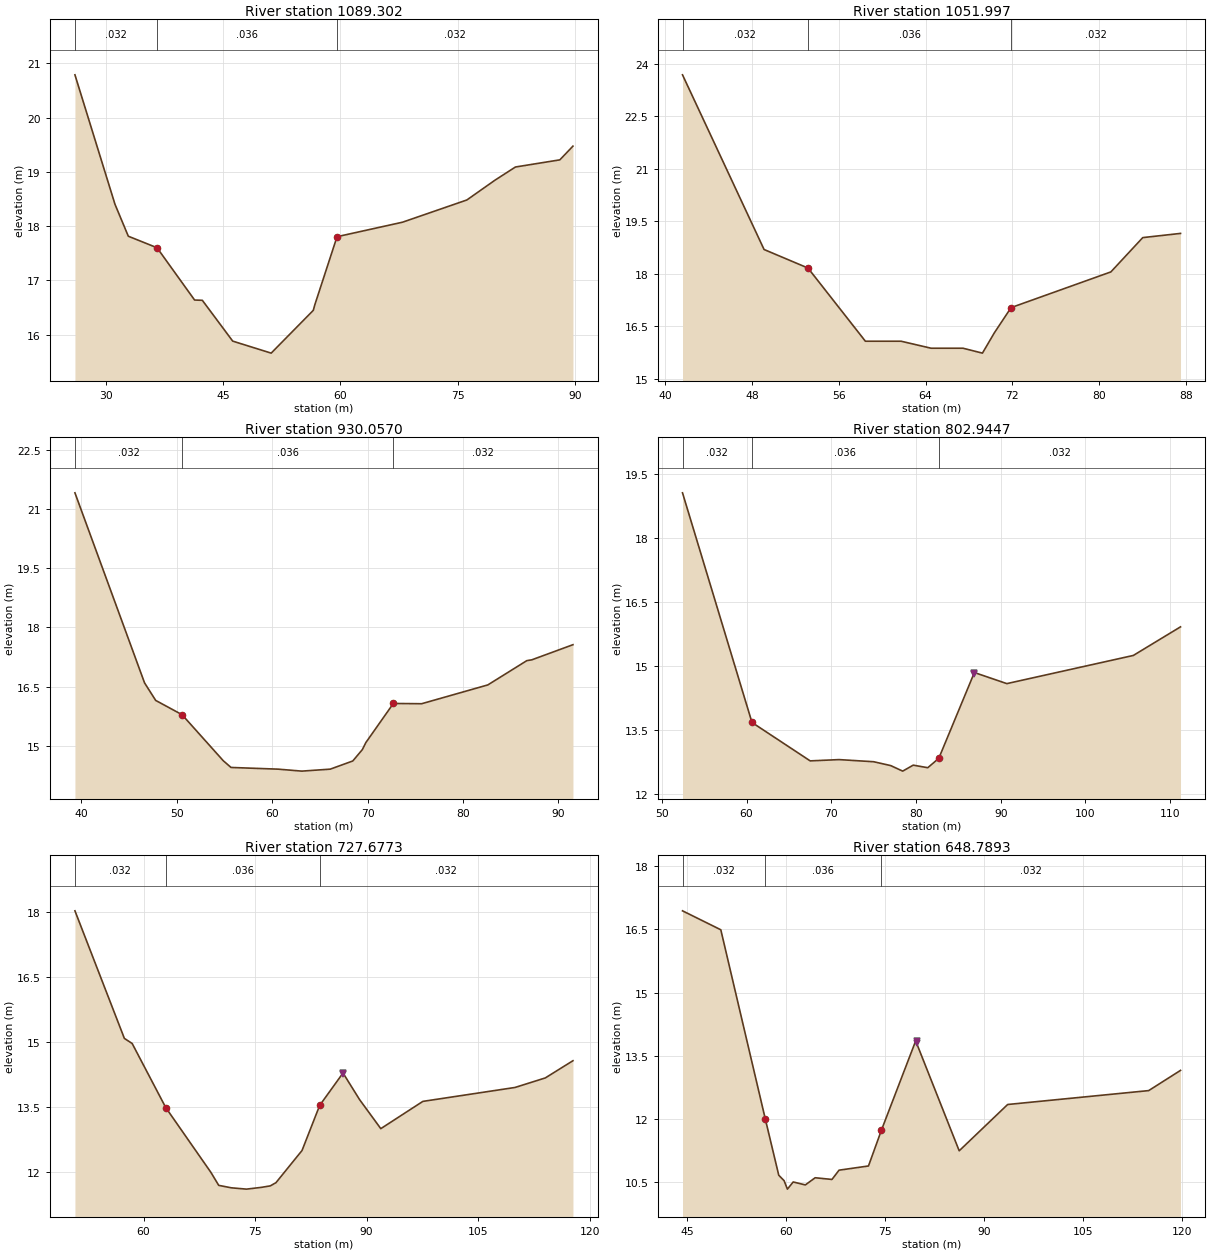
Type RM Length L Ch R = 1 ,1089.302,36.577,37.305,37.535
BEGIN DESCRIPTION:
Interpolated Section
END DESCRIPTION:
Node Name=W12a
XS GIS Cut Line= 2
300314.0330639555379822.61789455300309.247893518 5379886.1923018
#Sta/Elev= 18
  26.012  20.791  31.138  18.404  32.844  17.815  36.524  17.602   41.33  16.638
  42.321  16.633  46.207  15.881  46.837  15.852  51.134  15.659  56.527  16.448
   56.72   16.55  59.565  17.806  67.943  18.073  76.183  18.483  79.783  18.848
  82.403  19.091  88.088  19.223  89.766  19.476
#Mann= 3 , 0 , 0
  26.012    .032       0  36.524    .036       0  59.565    .032       0
Bank Sta=36.524,59.565
XS Rating Curve= 0 ,0
Exp/Cntr=0.3,0.1

Type RM Length L Ch R = 1 ,1051.997,119.597,121.94,125.44
BEGIN DESCRIPTION:
2008 Survey Section
END DESCRIPTION:
Node Name=W12
XS GIS Cut Line= 2
300278.1797119045379817.14976326300273.9853621615379862.86817545
#Sta/Elev= 13
  41.591   23.68  49.111   18.69  53.161   18.16  58.451   16.07   61.74   16.07
  64.511   15.87   67.45   15.87  69.241   15.73   70.34   16.31  71.881   17.03
  81.081   18.05  84.021   19.03  87.501   19.15
#Mann= 3 , 0 , 0
  41.591    .032       0  53.161    .036       0  71.881    .032       0
Bank Sta=53.161,71.881
XS Rating Curve= 0 ,0
Exp/Cntr=0.3,0.1

Type RM Length L Ch R = 1 ,930.0570,121.399,127.112,129.974
BEGIN DESCRIPTION:
Interpolated Section
END DESCRIPTION:
Node Name=W11a
XS GIS Cut Line= 2
300189.3136271425379758.25458379300156.4270450765379798.80645942
#Sta/Elev= 18
  39.315  21.413  46.614  16.596  47.782  16.152  50.545   15.79  54.876  14.621
  55.679  14.453   60.62   14.41    63.1   14.36   66.08   14.41  68.443  14.617
  69.449  14.906  69.821  15.086  72.699  16.075  75.663  16.068  82.605  16.545
  86.691   17.16  87.216  17.181  91.526  17.564
#Mann= 3 , 0 , 0
  39.315    .032       0  50.545    .036       0  72.699    .032       0
Bank Sta=50.545,72.699
XS Rating Curve= 0 ,0
Exp/Cntr=0.3,0.1

Type RM Length L Ch R = 1 ,802.9447,71.609,75.267,71.522
BEGIN DESCRIPTION:
2008 Survey Section
END DESCRIPTION:
Node Name=W11
XS GIS Cut Line= 2
 300109.024391465379677.44797171300053.624571032 5379697.0932981
#Sta/Elev= 14
  52.439   19.05  60.639   13.67  67.509   12.77   70.92    12.8  74.999   12.75
   77.01   12.66  78.429   12.53   79.67   12.67  81.389   12.61  82.689   12.83
  86.889   14.84  90.719   14.58 105.649   15.24 111.219   15.91
#Mann= 3 , 0 , 0
  52.439    .032       0  60.639    .036       0  82.689    .032       0
Levee=0,,,-1,86.82,14.83,,
Bank Sta=60.639,82.689
XS Rating Curve= 0 ,0
Exp/Cntr=0.3,0.1

Type RM Length L Ch R = 1 ,727.6773,79.11,78.888,80.462
BEGIN DESCRIPTION:
Interpolated Section
END DESCRIPTION:
Node Name=W10a
XS GIS Cut Line= 2
300099.889136565 5379608.0488858300038.2185467355379634.14028919
#Sta/Elev= 20
  50.773   18.02   57.42  15.077  58.467   14.96  62.989   13.48  69.061  11.985
  70.106  11.687   71.81   11.63   73.84    11.6   75.81   11.64  77.044  11.675
  77.804  11.749  81.308  12.491  83.682  13.531  86.819  14.279  89.043  13.666
  91.899  12.995  97.556  13.624  109.94  13.945 114.019  14.165 117.736  14.562
#Mann= 3 , 0 , 0
  50.773    .032       0  62.989    .036       0  83.682    .032       0
Levee=0,,,-1,86.88,14.29,,
Bank Sta=62.989,83.682
XS Rating Curve= 0 ,0
Exp/Cntr=0.3,0.1

Type RM Length L Ch R = 1 ,648.7893,69.05,68.73,68.507
BEGIN DESCRIPTION:
2008 Survey Section
END DESCRIPTION:
Node Name=W10
XS GIS Cut Line= 2
300092.3868587025379526.86943979300002.014689702   5379565.73747
#Sta/Elev= 18
  44.297   16.94  50.107   16.49   56.85      12  58.897   10.66   59.71   10.53
  60.207   10.33   61.09    10.5  62.927   10.43   64.42    10.6  66.967   10.56
   68.04   10.78  72.507   10.88   74.47   11.73  79.667   13.85  86.267   11.24
  93.617   12.34 115.007   12.67 119.837   13.15
#Mann= 3 , 0 , 0
  44.297    .032       0   56.85    .036       0   74.47    .032       0
Levee=0,,,-1,79.82,13.84,,
Bank Sta=56.85,74.47
XS Rating Curve= 0 ,0
Exp/Cntr=0.3,0.1

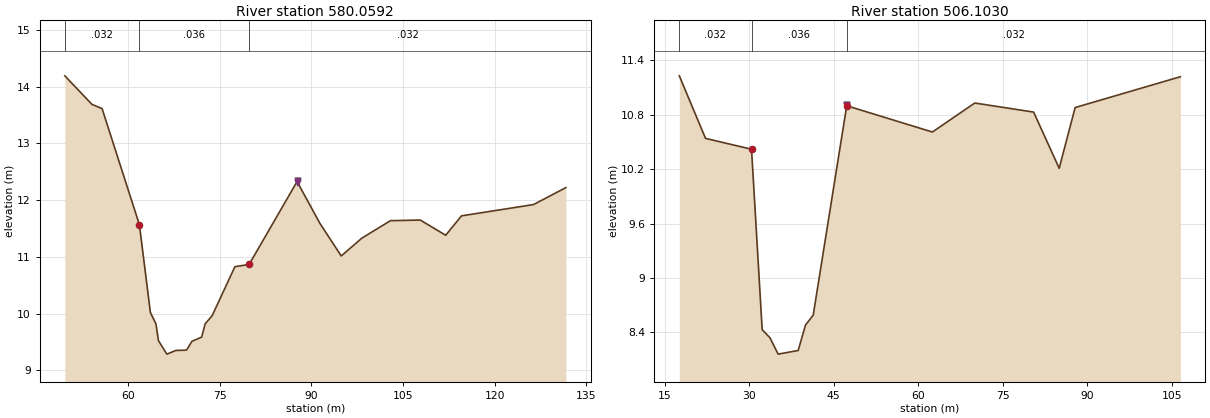
Type RM Length L Ch R = 1 ,580.0592,74.519,73.956,72.988
BEGIN DESCRIPTION:
Interpolated Section
END DESCRIPTION:
Node Name=W9a
XS GIS Cut Line= 2
300073.6423346195379462.06826613299999.8798686985379497.88561736
#Sta/Elev= 27
  49.643   14.19  54.069  13.688  55.739  13.612  61.845  11.566  63.644  10.018
   64.55    9.82  64.963   9.522  66.338   9.285   67.81    9.35  69.317   9.354
  69.594    9.36   70.43    9.51  72.035   9.585   72.61    9.82  73.741    9.96
  77.476  10.826  79.808  10.866   87.65  12.327  91.386   11.59  94.878  11.015
  98.263   11.33 102.927  11.637 107.819  11.648 111.971   11.38 114.559  11.722
 126.353  11.921 131.642   12.22
#Mann= 3 , 0 , 0
  49.643    .032       0  61.845    .036       0  79.808    .032       0
Levee=0,,,-1,87.75,12.34,,
Bank Sta=61.845,79.808
XS Rating Curve= 0 ,0
Exp/Cntr=0.3,0.1

Type RM Length L Ch R = 1 ,506.1030,11.553,11.974,12.929
BEGIN DESCRIPTION:
2008 Survey Section
END DESCRIPTION:
Node Name=W9
XS GIS Cut Line= 2
300056.1398469045379388.59785433299980.8645969775379435.98704577
#Sta/Elev= 16
  17.605   11.23  22.255   10.54  30.425   10.42  32.315    8.43    33.7    8.34
  35.145    8.16  38.705     8.2      40    8.48  41.375    8.59  47.325    10.9
  62.535   10.61  70.055   10.93  80.505   10.83  85.045   10.21  87.875   10.88
 106.555   11.22
#Mann= 3 , 0 , 0
  17.605    .032       0  30.425    .036       0  47.325    .032       0
Levee=0,,,-1,47.37,10.91,,
Bank Sta=30.425,47.325
XS Rating Curve= 0 ,0
Exp/Cntr=0.3,0.1