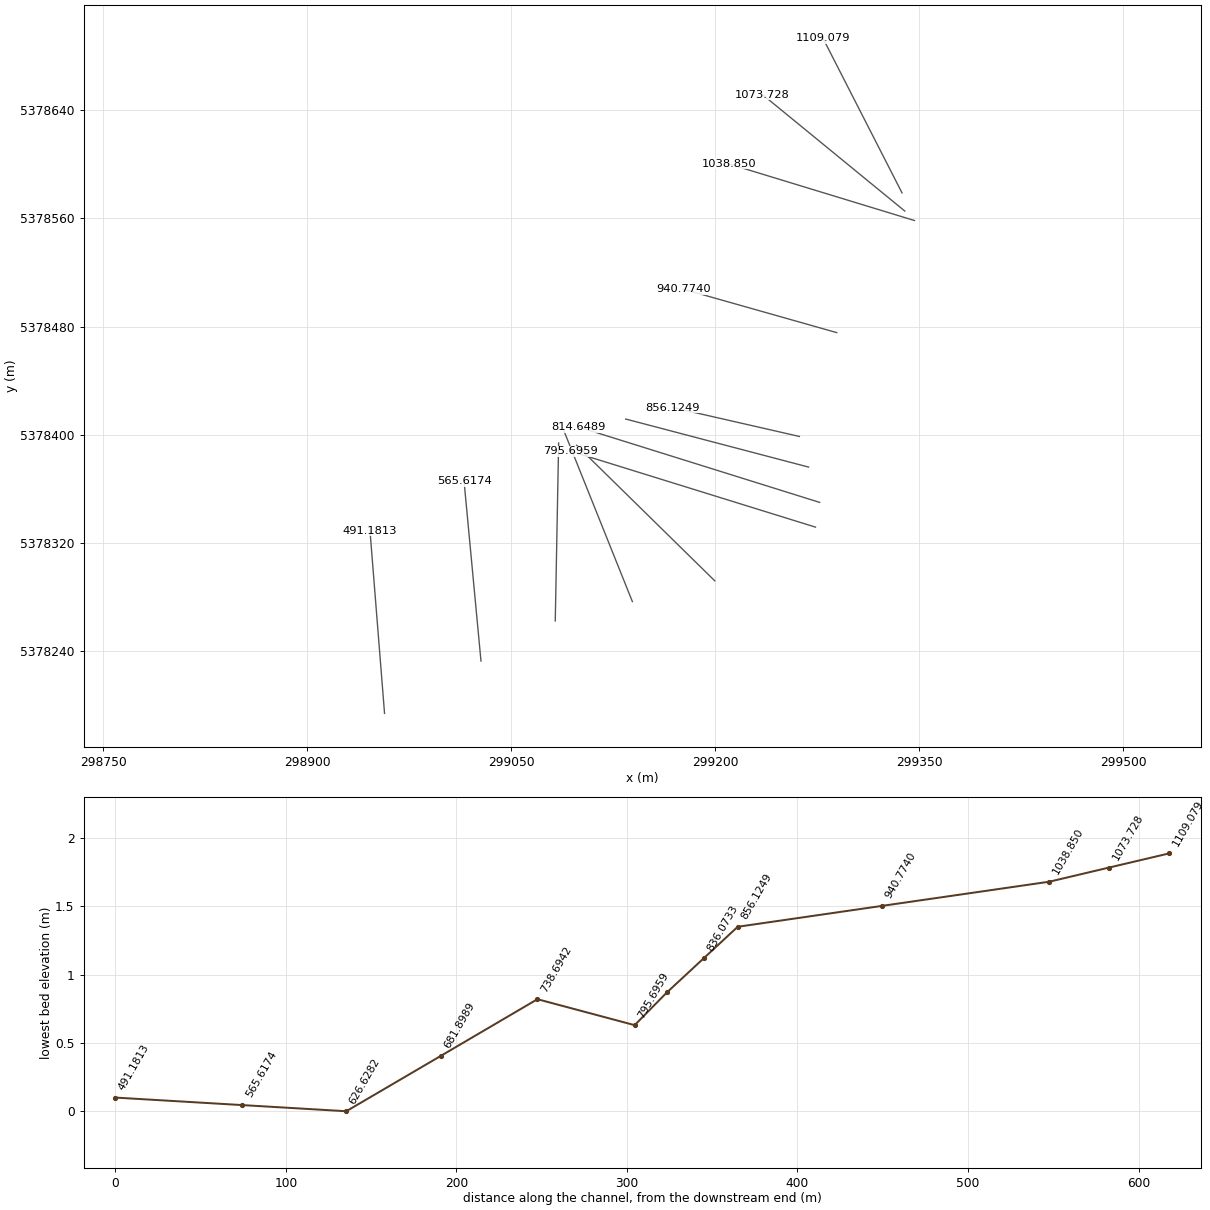
HEC-RAS study Blanche_Brook.prj: Stephenville Model

--- Blanche_Brook.g07 (geometry) --- (continued)

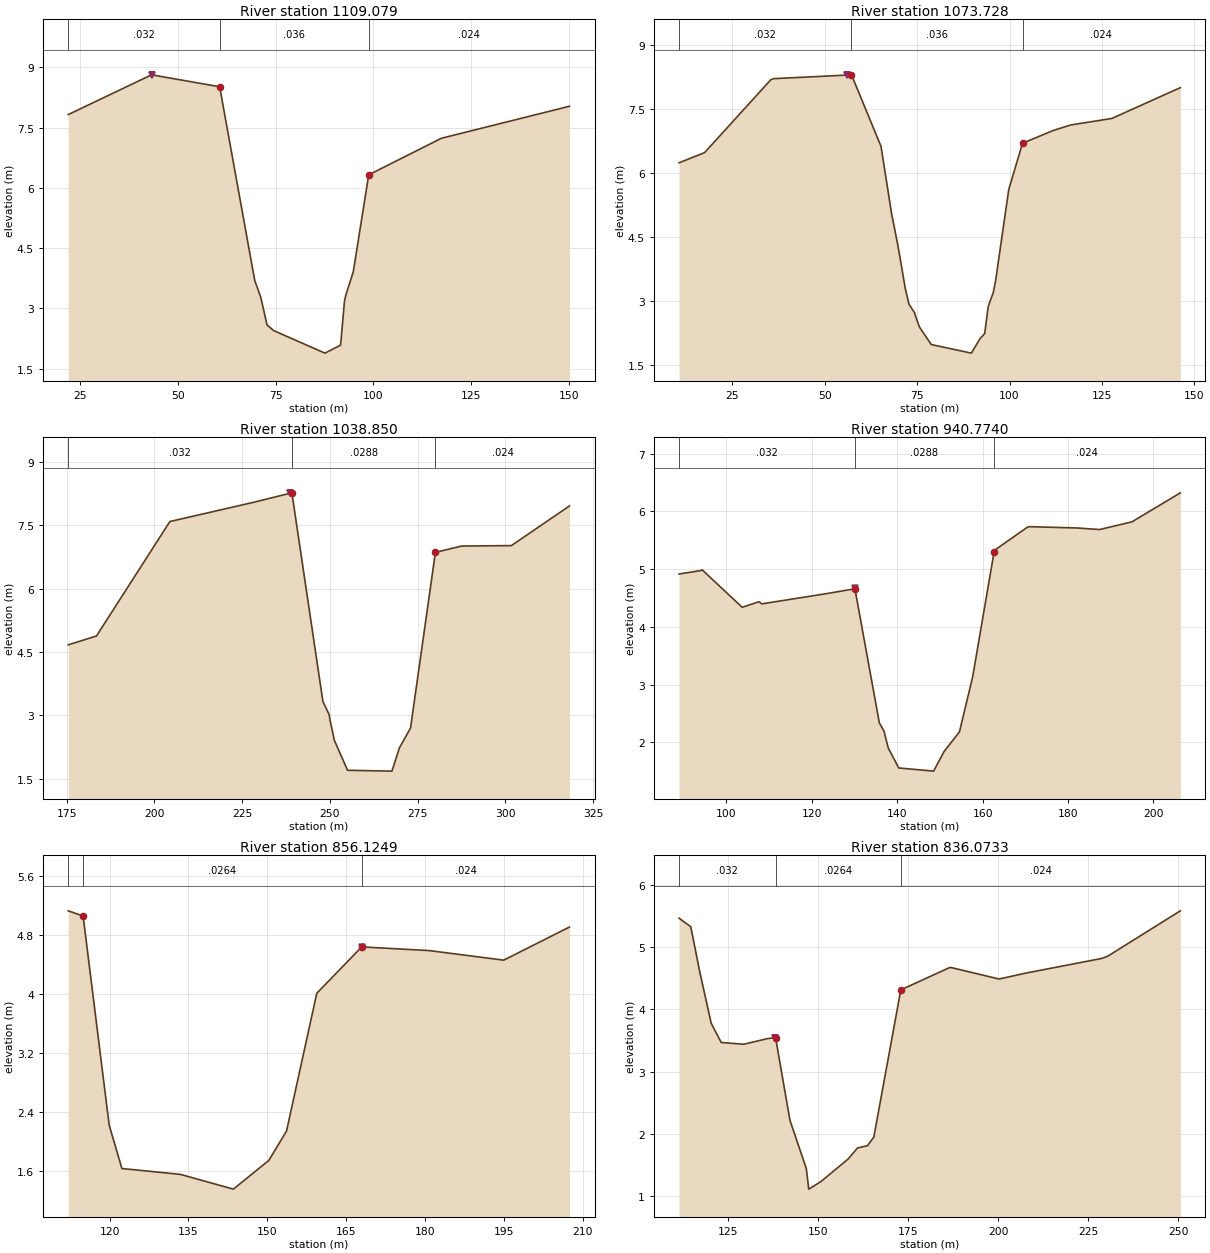
Type RM Length L Ch R = 1 ,1109.079,14.535,35.351,37.238
BEGIN DESCRIPTION:
2008 Survey Section
END DESCRIPTION:
Node Name=BB8
XS GIS Cut Line= 2
299337.5536422835378578.67410541299279.4347148645378692.83831755
#Sta/Elev= 16
      22  7.8266  43.288  8.8167  60.701  8.5196  69.681  3.6886  71.157  3.2922
  71.513  3.1466   72.81  2.5897  74.521   2.447  87.603   1.887  91.603   2.086
  92.603  3.1863  92.952  3.3331  94.847  3.9095  98.793  6.3259 117.365  7.2368
 150.107  8.0342
#Mann= 3 , 0 , 0
      22    .032       0  60.701    .036       0  98.793    .024       0
Levee=-1,43.46,8.8,0,,,,
Bank Sta=60.701,98.793
XS Rating Curve= 0 ,0
Exp/Cntr=0.3,0.1

Type RM Length L Ch R = 1 ,1073.728,15.434,34.878,36.514
BEGIN DESCRIPTION:
Interpolated Section
END DESCRIPTION:
Node Name=BB7a
XS GIS Cut Line= 2
299339.5825045725378565.28433151299234.883828444 5378651.3353084
#Sta/Elev= 30
  10.653   6.238  17.548   6.476  35.468   8.183  36.292   8.208  56.095   8.291
  57.264   8.297  65.243   6.624  68.079   5.063  69.857   4.283  70.285    4.07
  71.847    3.28  72.815   2.929  73.908   2.779  74.331   2.728  74.537   2.664
  75.607   2.398  78.837   1.984  89.664   1.783  92.043   2.125   93.28   2.241
  94.184   2.848    94.5   2.942  95.583   3.195  96.213   3.467  99.781   5.611
 103.502   6.695 111.867   6.996 116.573   7.124  127.67   7.276 146.176   7.997
#Mann= 3 , 0 , 0
  10.653    .032       0  57.264    .036       0 103.502    .024       0
Levee=-1,56.09,8.29,0,,,,
Bank Sta=57.264,103.502
XS Rating Curve= 0 ,0
Exp/Cntr=0.3,0.1

Type RM Length L Ch R = 1 ,1038.850,97.122,98.076,97.578
BEGIN DESCRIPTION:
2008 Survey Section
END DESCRIPTION:
Node Name=BB7
XS GIS Cut Line= 2
299346.6748915995378558.28651821299210.1001466295378600.12819631
#Sta/Elev= 17
 175.444    4.67 183.494    4.88 204.414    7.59 228.494    8.05 239.174    8.27
 248.014    3.33 249.784    3.02 250.024     2.9 251.274    2.41 255.044     1.7
 267.684    1.68 269.814    2.23 272.984     2.7 280.074    6.86 287.564    7.01
 301.714    7.02 318.284    7.96
#Mann= 3 , 0 , 0
 175.444    .032       0 239.174   .0288       0 280.074    .024       0
Levee=-1,238.7,8.26,0,,,,
Bank Sta=239.174,280.074
XS Rating Curve= 0 ,0
Exp/Cntr=0.3,0.1

Type RM Length L Ch R = 1 ,940.7740,81.937,84.649,84.827
BEGIN DESCRIPTION:
Interpolated Section
END DESCRIPTION:
Node Name=BB6a
XS GIS Cut Line= 2
299289.5190004735378475.50399297  299176.63230175378507.59647093
#Sta/Elev= 27
   88.93   4.917  94.131   4.978  94.298   4.992 103.705   4.341 107.647   4.436
 108.295     4.4 123.204   4.574 129.424   4.653 130.104   4.659 135.816   2.339
 136.959   2.189 137.114   2.132 137.922   1.901 140.358   1.558 148.524   1.503
 150.956   1.841 154.575   2.183 154.621   2.196 157.665   3.135 162.669   5.293
 162.859   5.332 170.583   5.733 171.219   5.736 182.172   5.714 187.373   5.687
  194.98   5.821  206.29   6.323
#Mann= 3 , 0 , 0
   88.93    .032       0 130.104   .0288       0 162.669    .024       0
Levee=-1,130.08,4.68,0,,,,
Bank Sta=130.104,162.669
XS Rating Curve= 0 ,0
Exp/Cntr=0.3,0.1

Type RM Length L Ch R = 1 ,856.1249,20.593,20.052,19.351
BEGIN DESCRIPTION:
2008 Survey Section
END DESCRIPTION:
Node Name=BB6
XS GIS Cut Line= 2
299262.0412684325378398.81673008 299169.088876585378420.15556043
#Sta/Elev= 13
 112.121    5.13 114.951    5.06 119.911    2.22 122.331    1.63 133.471    1.55
 143.541    1.35 150.291    1.74 153.661    2.14 159.411    4.01 167.961    4.64
 180.791    4.59 194.971    4.46 207.491    4.91
#Mann= 3 , 0 , 0
 112.121    .032       0 114.951   .0264       0 167.961    .024       0
Levee=0,,,-1,167.98,4.63,,
Bank Sta=114.951,167.961
XS Rating Curve= 0 ,0
Exp/Cntr=0.3,0.1

Type RM Length L Ch R = 1 ,836.0733,22.384,21.424,19.965
BEGIN DESCRIPTION:
Interpolated Section
END DESCRIPTION:
Node Name=BB5a
XS GIS Cut Line= 2
299268.8219511995378376.18757931299134.3559988055378411.67550076
#Sta/Elev= 25
  111.46   5.464   114.7   5.327 117.229   4.595  120.38   3.778 123.151    3.47
 129.445   3.442 135.907   3.531 138.226    3.55 142.215   2.223  146.76   1.448
 147.438   1.118 150.789   1.238  158.32   1.599 160.976   1.778 163.752   1.815
 165.493   1.954 172.955   4.308 173.022   4.315   186.4   4.669 186.805   4.674
  200.25   4.488 207.488   4.581 228.713   4.818 230.347   4.853  250.53   5.582
#Mann= 3 , 0 , 0
  111.46    .032       0 138.226   .0264       0 173.022    .024       0
Levee=-1,138.2,3.55,0,,,,
Bank Sta=138.226,173.022
XS Rating Curve= 0 ,0
Exp/Cntr=0.3,0.1

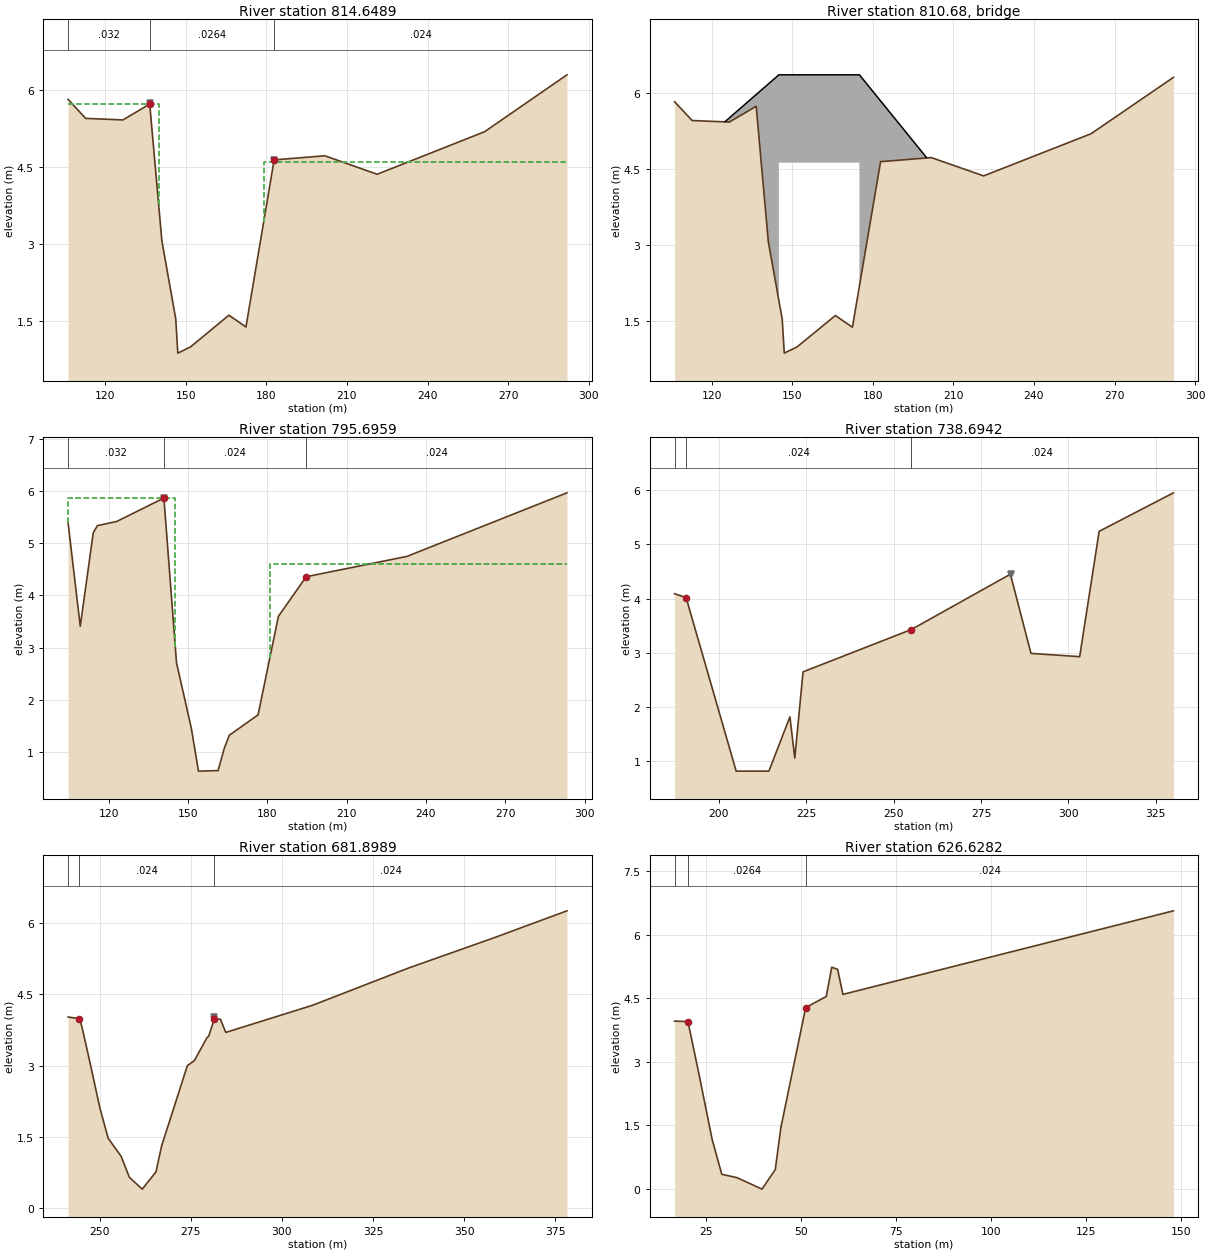
Type RM Length L Ch R = 1 ,814.6489,18.459,18.953,19.95
BEGIN DESCRIPTION:
2008 Survey Section
END DESCRIPTION:
Node Name=BB5
XS GIS Cut Line= 2
299276.9551404685378350.11388619  299099.7180702 5378405.7680387
#Sta/Elev= 15
 106.164    5.82 112.714    5.45 126.584    5.42 136.554    5.73 141.084    3.06
 146.244    1.54 147.014     .87 151.724     .99 166.044    1.61 172.394    1.38
 182.884    4.64 201.784    4.72 221.254    4.36 261.264    5.19 291.934     6.3
#Mann= 3 , 0 , 0
 106.164    .032       0 136.554   .0264       0 182.884    .024       0
Levee=-1,136.59,5.75,-1,182.82,4.63,,
#XS Ineff= 2 , 0
       0     140    5.73     179       0     4.6
Permanent Ineff=
       F       F
Bank Sta=136.554,182.884
XS Rating Curve= 0 ,0
Exp/Cntr=0.5,0.3

Type RM Length L Ch R = 3 ,810.68  ,,,
BEGIN DESCRIPTION:
West Street Bridge
END DESCRIPTION:
Bridge Culvert--1,0,-1,-1, 0
Deck Dist Width WeirC Skew NumUp NumDn MinLoCord MaxHiCord MaxSubmerge Is_Ogee
3.97,11.06,1.6,0, 6, 6, , , 0.98, 0, 1,1,,
     125     145     145     175     175     200
    5.43    6.35    6.35    6.35    6.35    4.72
       0       0    4.62    4.62       0       0
  123.09     148     148     178     178   210.5
    5.42    6.35    6.35    6.35    6.35    4.52
       0       0    4.62    4.62       0       0
BR Coef=-1 , 0 , 0 ,, 0 ,,,0.8,-1,,0,
WSPro=,,,, 1 ,,,, 0 ,,,, 0 ,,,,-1 ,-1 ,-1 , 0 , 0 , 0 , 0 , 0
BC Design=,, 0 ,, 0 ,,,,,,
BC Use User HTab Curves=0
BC User HTab FreeFlow(D)= 0

Type RM Length L Ch R = 1 ,795.6959,71.29,57.002,36.886
BEGIN DESCRIPTION:
2008 Survey Section
END DESCRIPTION:
Node Name=BB4
XS GIS Cut Line= 3
299273.9015670265378331.84785611299103.7365074265378384.85630912
299093.8644150325378387.93158407
#Sta/Elev= 17
  104.72    5.39  109.31    3.41  114.22     5.2  115.77    5.34  123.09    5.42
  140.93    5.87   145.7    2.71  151.31    1.45     154     .63  161.41     .64
  163.77    1.07  165.69    1.32  176.53    1.71  184.21     3.6  194.72    4.36
  232.79    4.75  293.29    5.97
#Mann= 3 , 0 , 0
  104.72    .032       0  140.93    .024       0  194.72    .024       0
Levee=-1,140.88,5.86,0,,,,
#XS Ineff= 2 , 0
       0   145.3    5.87     181       0     4.6
Permanent Ineff=
       F       F
Bank Sta=140.93,194.72
XS Rating Curve= 0 ,0
Exp/Cntr=0.5,0.3

Type RM Length L Ch R = 1 ,738.6942,67.074,56.795,41.781
BEGIN DESCRIPTION:
2008 Survey Section
END DESCRIPTION:
Node Name=BB3
XS GIS Cut Line= 3
299199.8787955965378292.15458574299107.6693190495378383.02553655
299098.282487735 5378392.2761073
#Sta/Elev= 13
  187.38    4.09  190.67    4.02  204.99     .82  214.35     .82  220.36    1.82
  221.75    1.06  224.12    2.65  255.08    3.43   283.4    4.45  289.29    2.99
  303.21    2.93  308.78    5.24  330.02    5.95
#Mann= 3 , 0 , 0
  187.38    .032       0  190.67    .024       0  255.08    .024       0
Levee=0,,,-1,283.48,4.45,,
Bank Sta=190.67,255.08
XS Rating Curve= 0 ,0
Exp/Cntr=0.3,0.1

Type RM Length L Ch R = 1 ,681.8989,63.606,55.271,49.993
BEGIN DESCRIPTION:
Interpolated Section
END DESCRIPTION:
Node Name=BB2a
XS GIS Cut Line= 3
299139.2552421285378276.84543925299090.8326266115378398.15095988
299088.4799503045378404.04474776
#Sta/Elev= 23
 241.292   4.024 244.413   3.991 245.096   3.817 247.056   3.149 250.043   2.104
 252.289   1.474 255.851   1.094  258.13     .65 261.649    .404 265.414    .767
 267.017   1.329 267.028   1.329  274.03       3 275.983   3.111  279.49     3.6
  279.86   3.613  281.42   3.983 283.087    3.98 284.582   3.701 308.363   4.271
 334.773   5.056 358.443   5.698 378.251   6.259
#Mann= 3 , 0 , 0
 241.292    .032       0 244.413    .024       0  281.42    .024       0
Levee=0,,,-1,281.4,4.03,,
Bank Sta=244.413,281.42
XS Rating Curve= 0 ,0
Exp/Cntr=0.3,0.1

Type RM Length L Ch R = 1 ,626.6282,58.72,61.011,61.078
BEGIN DESCRIPTION:
2008 Survey Section
END DESCRIPTION:
Node Name=BB2
XS GIS Cut Line= 2
299082.5492337485378262.56919484299085.0328686995378393.97606229
#Sta/Elev= 16
  16.645    3.96  20.175    3.95  23.165    2.67  26.545    1.17  29.085     .35
  33.115     .27  39.675       0  43.175     .46  44.665    1.46  44.675    1.46
  51.185    4.28  56.605    4.54  58.055    5.23  59.605    5.18  60.995    4.59
 148.075    6.56
#Mann= 3 , 0 , 0
  16.645    .032       0  20.175   .0264       0  51.185    .024       0
Bank Sta=20.175,51.185
XS Rating Curve= 0 ,0
Exp/Cntr=0.3,0.1

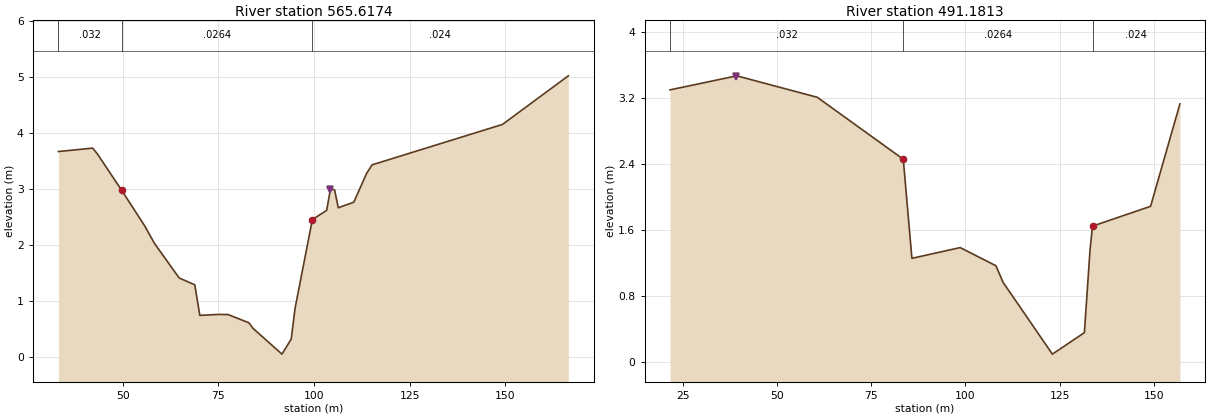
Type RM Length L Ch R = 1 ,565.6174,73.909,74.436,75.815
BEGIN DESCRIPTION:
Interpolated Section
END DESCRIPTION:
Node Name=BB1a
XS GIS Cut Line= 2
299027.9215376945378232.95440991 299015.484348895378365.61775714
#Sta/Elev= 26
  33.236   3.663  42.189   3.724  43.443   3.618  49.773    2.97  55.737    2.34
  58.345   2.022  64.788   1.405   68.87   1.283  70.187    .737  75.009    .754
  77.565    .752  83.028    .604  84.109    .504  91.647    .045  94.064    .313
  95.092    .869  99.593   2.447 103.335   2.613 104.336   2.998 105.406   2.978
 106.366   2.659 110.422   2.758 113.735   3.268 115.193   3.425 149.275   4.147
 166.481   5.015
#Mann= 3 , 0 , 0
  33.236    .032       0  49.773   .0264       0  99.593    .024       0
Levee=0,,,-1,104.3,3,,
Bank Sta=49.773,99.593
XS Rating Curve= 0 ,0
Exp/Cntr=0.3,0.1

Type RM Length L Ch R = 1 ,491.1813,180,200,230
BEGIN DESCRIPTION:
2008 Survey Section
END DESCRIPTION:
Node Name=BB1
XS GIS Cut Line= 2
298957.0029866265378194.29174627298946.2925461565378329.32729963
#Sta/Elev= 14
  21.503     3.3  39.253    3.47  60.633    3.21  83.473    2.46  85.763    1.26
  98.593    1.39 108.093    1.17 109.973     .97 123.083      .1 131.583     .36
 133.083    1.36 133.743    1.65 149.173    1.89 156.963    3.13
#Mann= 3 , 0 , 0
  21.503    .032       0  83.473   .0264       0 133.743    .024       0
Levee=-1,39.15,3.46,0,,,,
Bank Sta=83.473,133.743
XS Rating Curve= 0 ,0
Exp/Cntr=0.3,0.1

--- Blanche_Brook.g11 (geometry) ---

Geom Title=Base Case + 20% n
Program Version=4.00

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
River Reach=Blanche Brook   ,US of Confluence

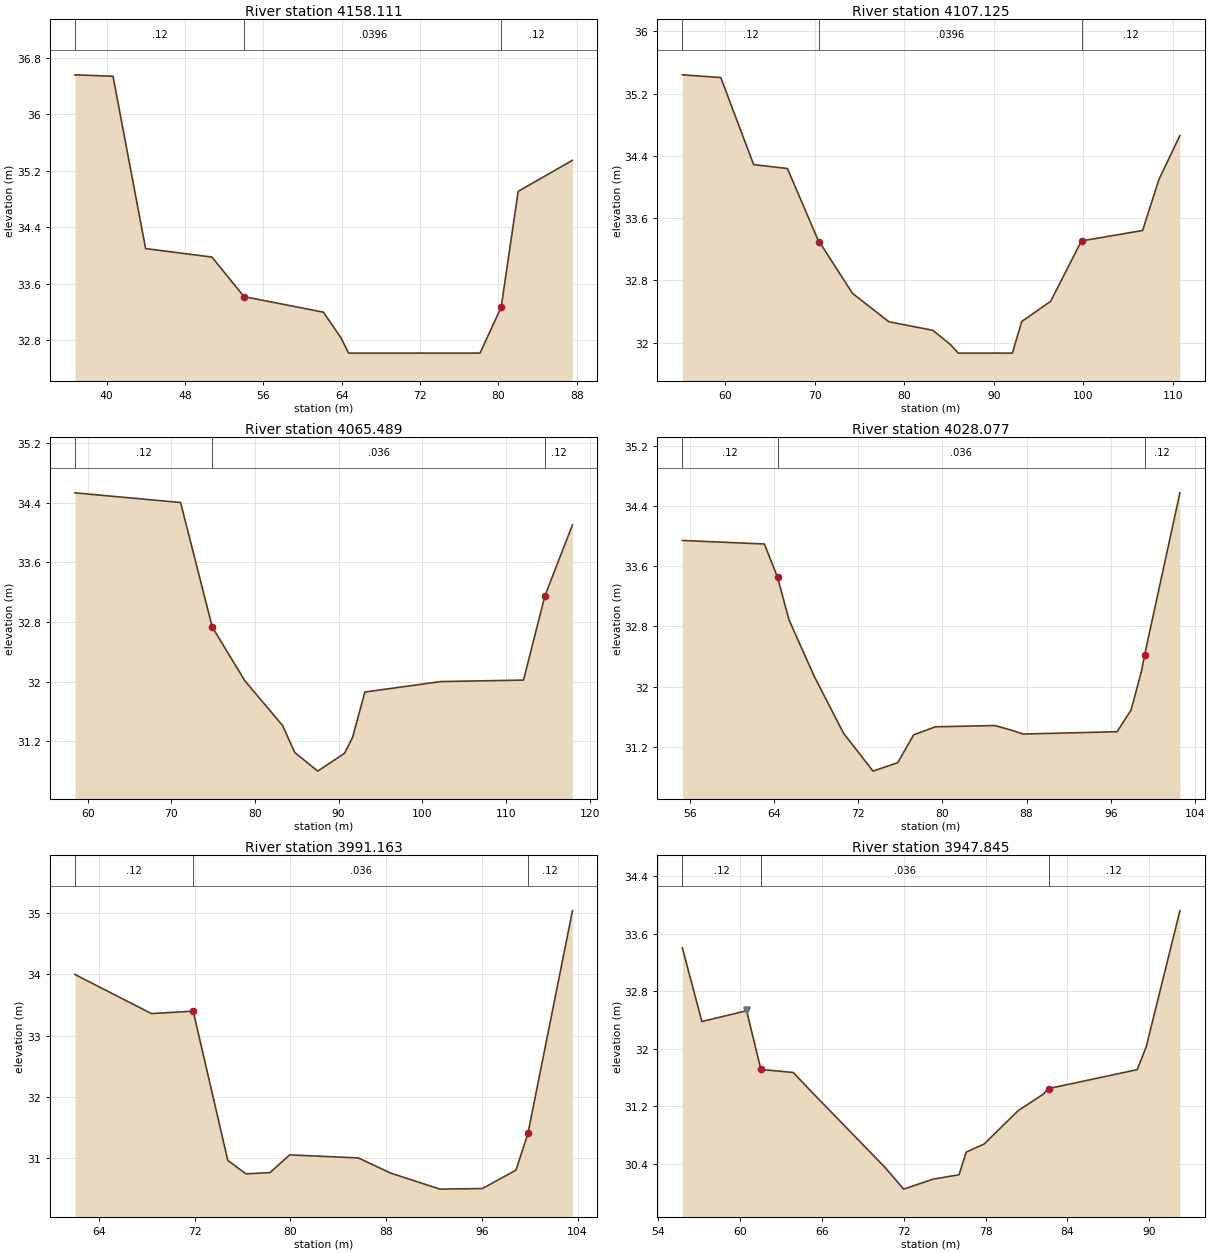
Type RM Length L Ch R = 1 ,4158.111,56.608,50.986,38.986
BEGIN DESCRIPTION:
2008 Survey Section
END DESCRIPTION:
Node Name=BB39
XS GIS Cut Line= 2
298673.7152083715380853.34084345 298671.076662985380802.59958592
#Sta/Elev= 12
  36.751   36.56  40.641   36.54  43.971    34.1  50.741   33.98  54.021   33.42
  62.121    33.2  63.911   32.84  64.701   32.62  78.121   32.62  80.281   33.27
  82.021   34.91  87.561   35.35
#Mann= 3 , 0 , 0
  36.751     .12       0  54.021   .0396       0  80.281     .12       0
Bank Sta=54.021,80.281
XS Rating Curve= 0 ,0
Exp/Cntr=0.3,0.1

Type RM Length L Ch R = 1 ,4107.125,48.237,41.636,33.727
BEGIN DESCRIPTION:
Interpolated Section
END DESCRIPTION:
Node Name=BB38a
XS GIS Cut Line= 2
298722.5515181345380829.68306117298690.4697829215380784.29914307
#Sta/Elev= 20
  55.202  35.442  59.493  35.407  63.166  34.288  66.938  34.238  70.459  33.293
  70.634  33.273  74.083  32.656  74.251   32.63  78.273  32.269  83.186  32.159
   85.16  31.975  86.032  31.866  92.064  31.866  93.117  32.273  96.346  32.532
   99.56  33.258  99.796  33.308 106.615  33.442 108.438  34.097  110.78  34.662
#Mann= 3 , 0 , 0
  55.202     .12       0  70.459   .0396       0  99.796     .12       0
Bank Sta=70.459,99.796
XS Rating Curve= 0 ,0
Exp/Cntr=0.3,0.1

Type RM Length L Ch R = 1 ,4065.489,38.598,37.412,37.41
BEGIN DESCRIPTION:
2008 Survey Section
END DESCRIPTION:
Node Name=BB38
XS GIS Cut Line= 2
298755.4837313625380786.51361197 298700.593541525380763.62888025
#Sta/Elev= 14
  58.474   34.53  71.104    34.4  74.894   32.73  78.794   32.01  83.304   31.41
   84.75   31.05    87.5    30.8   90.71   31.04  91.654   31.25  93.134   31.86
 102.184      32 112.094   32.02 114.654   33.15 117.944    34.1
#Mann= 3 , 0 , 0
  58.474     .12       0  74.894    .036       0 114.654     .12       0
Bank Sta=74.894,114.654
XS Rating Curve= 0 ,0
Exp/Cntr=0.3,0.1

Type RM Length L Ch R = 1 ,4028.077,36.768,36.914,37.219
BEGIN DESCRIPTION:
Interpolated Section
END DESCRIPTION:
Node Name=BB37a
XS GIS Cut Line= 2
298751.6701636045380744.77469999298708.0944586265380726.52001277
#Sta/Elev= 19
  55.314  33.941  63.101  33.894  64.351  33.453  65.438  32.889  67.842  32.137
  70.622  31.382  71.835  31.165   73.42   30.88   75.77  30.993  77.278  31.362
  79.355  31.468  84.991  31.485    86.5  31.426  87.672  31.372  96.598  31.403
  97.924  31.691  98.906  32.204  99.206   32.42 102.559  34.573
#Mann= 3 , 0 , 0
  55.314     .12       0  64.351    .036       0  99.206     .12       0
Bank Sta=64.351,99.206
XS Rating Curve= 0 ,0
Exp/Cntr=0.3,0.1

Type RM Length L Ch R = 1 ,3991.163,44.678,43.318,41.969
BEGIN DESCRIPTION:
2008 Survey Section
END DESCRIPTION:
Node Name=BB37
XS GIS Cut Line= 3
298764.9254170855380712.09629316298759.2073460725380709.23725765
298727.7416325775380693.50440091
#Sta/Elev= 14
      62      34  68.393   33.36  71.883    33.4  74.773   30.96  76.293   30.74
    78.3   30.76  79.943   31.05  85.683      31  88.413   30.75    92.5   30.49
   96.05    30.5  98.853    30.8  99.853    31.4 103.573   35.04
#Mann= 3 , 0 , 0
      62     .12       0  71.883    .036       0  99.853     .12       0
Bank Sta=71.883,99.853
XS Rating Curve= 0 ,0
Exp/Cntr=0.3,0.1

Type RM Length L Ch R = 1 ,3947.845,45.414,42.347,39.914
BEGIN DESCRIPTION:
Interpolated Section
END DESCRIPTION:
Node Name=BB36a
XS GIS Cut Line= 2
298783.5906972145380667.79544014298748.1588359315380659.09287772
#Sta/Elev= 18
  55.762  33.406  57.194  32.382  60.474  32.532  61.521  31.715  63.888  31.673
  65.264  31.399  70.616  30.354   71.99   30.05  74.155  30.189   76.05   30.25
  76.576  30.565  77.889  30.677  80.383  31.141  82.193  31.367  82.615  31.449
  89.117  31.712   89.78  32.032  92.247  33.922
#Mann= 3 , 0 , 0
  55.762     .12       0  61.521    .036       0  82.615     .12       0
Levee=-1,60.47,32.54,0,,,,
Bank Sta=61.521,82.615
XS Rating Curve= 0 ,0
Exp/Cntr=0.3,0.1

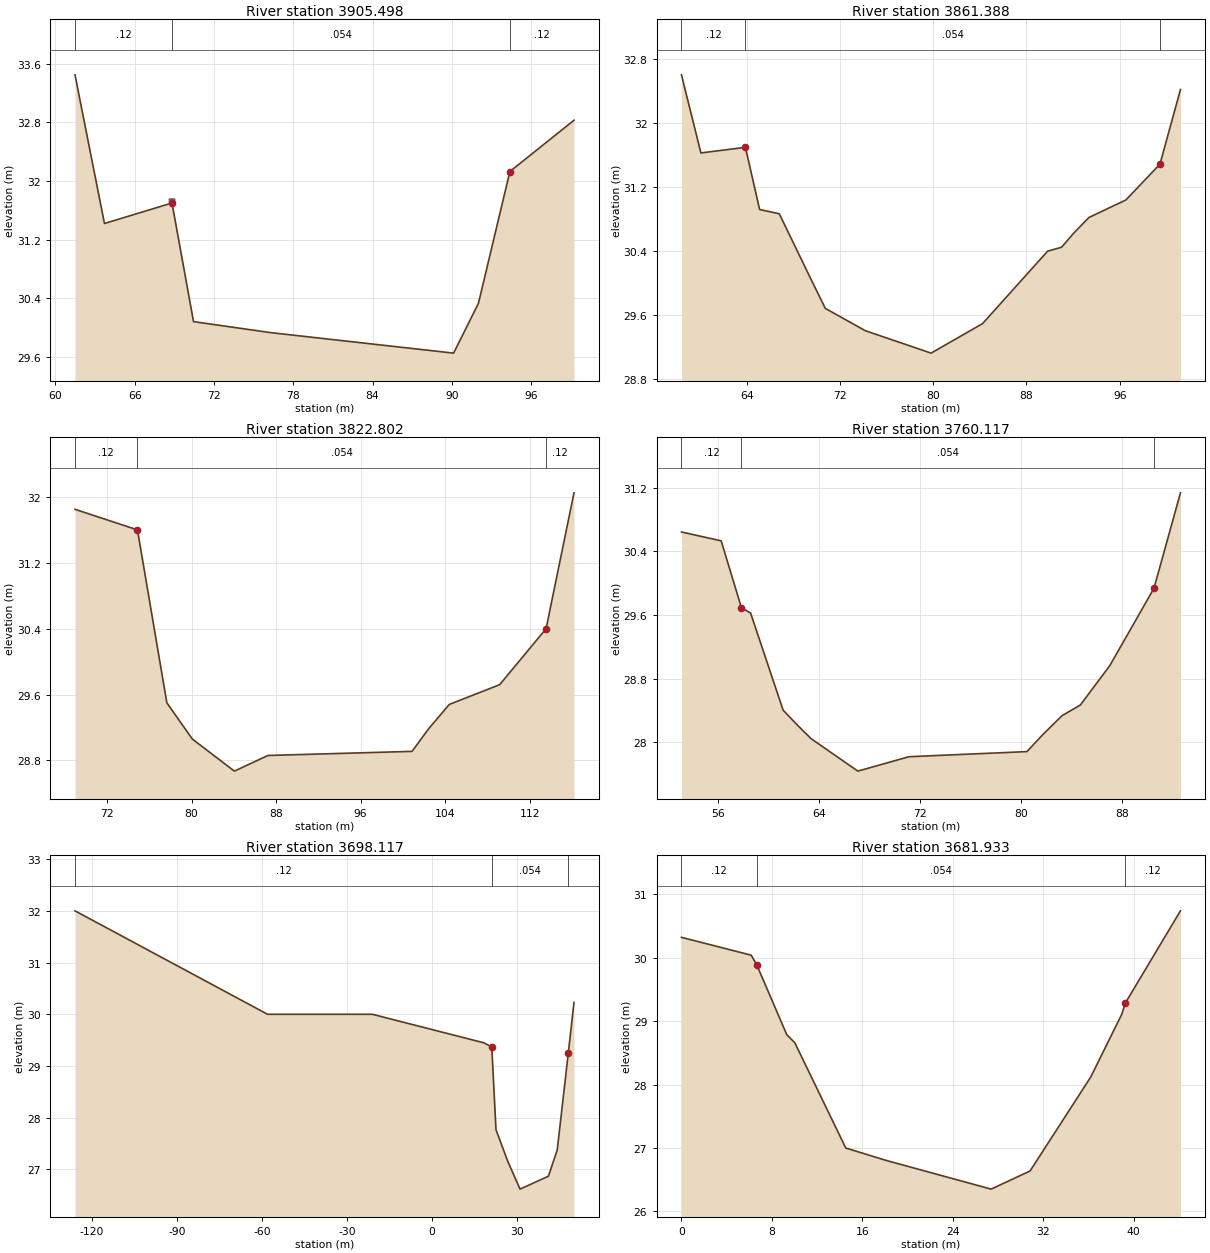
Type RM Length L Ch R = 1 ,3905.498,44.577,44.11,42.837
BEGIN DESCRIPTION:
2008 Survey Section
END DESCRIPTION:
Node Name=BB36
XS GIS Cut Line= 2
298793.5339148415380621.95262812298755.8004084925380623.36763461
#Sta/Elev= 9
  61.485   33.45  63.715   31.42  68.825    31.7  70.455   30.08  76.285   29.93
  90.135   29.65  92.015   30.33  94.395   32.13  99.245   32.83
#Mann= 3 , 0 , 0
  61.485     .12       0  68.825    .054       0  94.395     .12       0
Levee=-1,68.84,31.71,0,,,,
Bank Sta=68.825,94.395
XS Rating Curve= 0 ,0
Exp/Cntr=0.3,0.1

Type RM Length L Ch R = 1 ,3861.388,38.751,38.586,37.773
BEGIN DESCRIPTION:
Interpolated Section
END DESCRIPTION:
Node Name=BB35a
XS GIS Cut Line= 2
 298785.138542525380576.82051854298743.221058966 5380585.4732101
#Sta/Elev= 17
  58.408  32.597  60.075  31.623  63.894  31.693  65.112  30.918    66.8  30.864
  69.469  30.063  70.747  29.685  74.169  29.407   79.82  29.127  84.234  29.495
  89.822  30.399   91.01  30.447  92.035   30.62  93.354  30.818  96.529  31.037
  99.451  31.483 101.209  32.414
#Mann= 3 , 0 , 0
  58.408     .12       0  63.894    .054       0  99.451     .12       0
Bank Sta=63.894,99.451
XS Rating Curve= 0 ,0
Exp/Cntr=0.3,0.1

Type RM Length L Ch R = 1 ,3822.802,61.91,62.684,63.038
BEGIN DESCRIPTION:
2008 Survey Section
END DESCRIPTION:
Node Name=BB35
XS GIS Cut Line= 2
298777.8696352115380538.01749845298731.3351375525380551.67608821
#Sta/Elev= 12
  68.973   31.85  74.883    31.6  77.663    29.5  80.073   29.06  84.053   28.67
   87.23   28.86 100.863   28.91 102.403   29.18 104.383   29.48 109.153   29.72
 113.543    30.4 116.183   32.05
#Mann= 3 , 0 , 0
  68.973     .12       0  74.883    .054       0 113.543     .12       0
Bank Sta=74.883,113.543
XS Rating Curve= 0 ,0
Exp/Cntr=0.3,0.1

Type RM Length L Ch R = 1 ,3760.117,58.614,62,62.497
BEGIN DESCRIPTION:
Interpolated Section
END DESCRIPTION:
Node Name=BB34a
XS GIS Cut Line= 2
298769.9586677435380478.33507839298731.0398285855380485.25398313
#Sta/Elev= 17
  53.088  30.643  56.235  30.532   57.84  29.691  58.565  29.625  61.141  28.405
  62.332  28.207  63.374  28.045  67.062  27.639   71.11   27.82  80.432  27.884
  80.517  27.894  81.657  28.089  83.232  28.335  84.689   28.47  87.026  28.966
  90.517  29.935  92.617  31.135
#Mann= 3 , 0 , 0
  53.088     .12       0   57.84    .054       0  90.517     .12       0
Bank Sta=57.84,90.517
XS Rating Curve= 0 ,0
Exp/Cntr=0.3,0.1

Type RM Length L Ch R = 1 ,3698.117,12.698,16.184,17.773
BEGIN DESCRIPTION:
2008 Survey Section
END DESCRIPTION:
Node Name=BB34
XS GIS Cut Line= 3
298910.5745372965380453.29789571298768.7181217225380426.94205896
298737.3256638325380421.10958045
#Sta/Elev= 12
    -126      32     -58      30     -21      30  18.284   29.45  21.184   29.37
  22.664   27.77  26.804   27.16  31.164   26.62  41.194   26.87  44.304   27.38
    48.2   29.25  50.214   30.23
#Mann= 3 , 0 , 0
    -126     .12       0  21.184    .054       0    48.2     .12       0
Bank Sta=21.184,48.2
XS Rating Curve= 0 ,0
Exp/Cntr=0.3,0.1

Type RM Length L Ch R = 1 ,3681.933,13.96,18.62,26.435
BEGIN DESCRIPTION:
Interpolated Section
END DESCRIPTION:
Node Name=BB33a
XS GIS Cut Line= 2
298775.5585656015380424.65428451298738.1059505735380401.29156003
#Sta/Elev= 13
       0  30.321   6.168   30.04   6.665  29.886   9.315  28.787  10.025   28.66
  14.535      27   18.12  26.804  27.393  26.352  30.838  26.638  36.212  28.121
  38.946  29.107  39.272  29.287  44.142  30.739
#Mann= 3 , 0 , 0
       0     .12       0   6.665    .054       0  39.272     .12       0
Bank Sta=6.665,39.272
XS Rating Curve= 0 ,0
Exp/Cntr=0.3,0.1

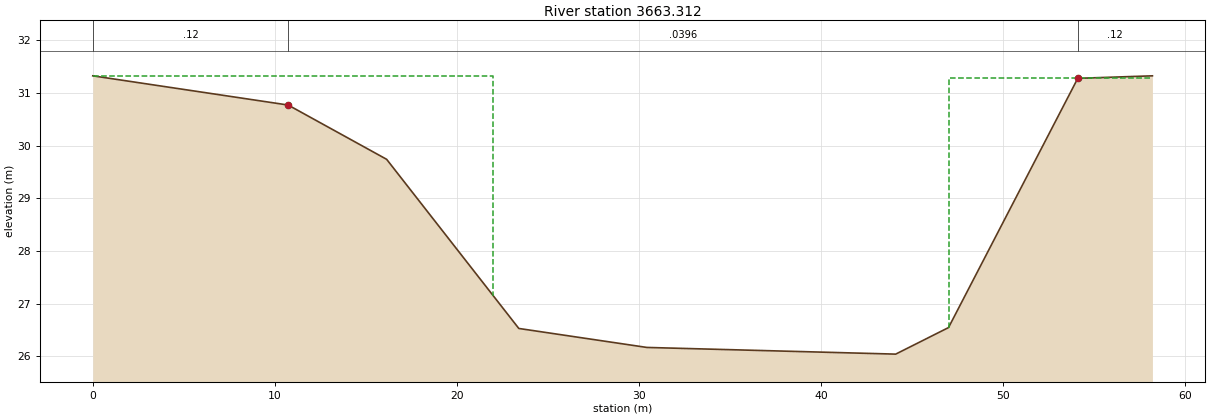
Type RM Length L Ch R = 1 ,3663.312,28.407,28.345,23.772
BEGIN DESCRIPTION:
2008 Survey Section
END DESCRIPTION:
Node Name=BB33
XS GIS Cut Line= 3
298773.493453953 5380419.3569334298765.3284293535380414.64798742
298747.8633755695380369.10757782
#Sta/Elev= 9
       0 31.3243   10.73   30.77   16.14   29.74    23.4   26.53   30.43   26.17
    44.1  26.043      47 26.5466    54.131.27667    58.2 31.3243
#Mann= 3 , 0 , 0
       0     .12       0   10.73   .0396       0    54.1     .12       0
#XS Ineff= 2 , 0
       0      22   31.32      47       0   31.29
Permanent Ineff=
       F       F
Bank Sta=10.73,54.1
XS Rating Curve= 0 ,0
Exp/Cntr=0.5,0.3