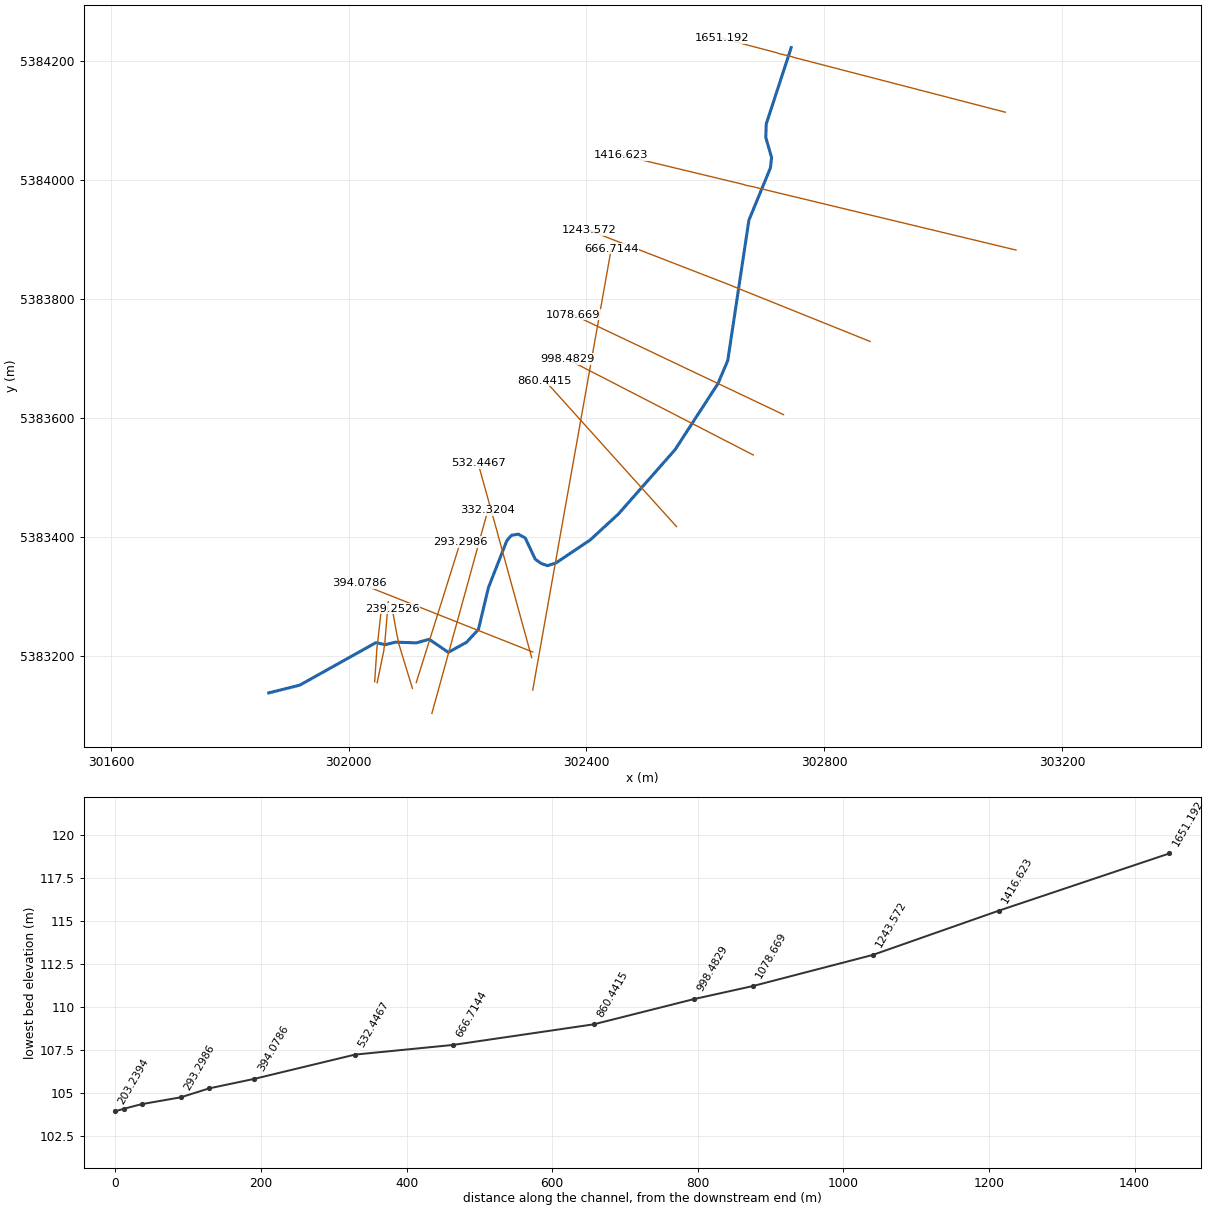
--- Cold_Brook.prj (project) ---

Proj Title=Cold Brook Model
Current Plan=p02
Default Exp/Contr=0.3,0.1
SI Units
Geom File=g04
Geom File=g01
Geom File=g02
Geom File=g05
Geom File=g06
Flow File=f01
Flow File=f02
Flow File=f03
Flow File=f04
Flow File=f05
Flow File=f06
Flow File=f07
Plan File=p01
Plan File=p02
Plan File=p03
Plan File=p04
Plan File=p05
Plan File=p06
Plan File=p07
Plan File=p10
Plan File=p08
Plan File=p09
Plan File=p12
Y Axis Title=Elevation
X Axis Title(PF)=Main Channel Distance
X Axis Title(XS)=Station
BEGIN DESCRIPTION:
END DESCRIPTION:
DSS Export Rating Curves= 0
DSS Export Rating Curve Sorted= 0
DSS Export Volume Flow Curves= 0
DXF Filename=..\..\..\Hydr\Hydraulic Model\ColdBrookModel.
DXF OffsetX= 0
DXF OffsetY= 0
DXF ScaleX= 1
DXF ScaleY= 10

--- Cold_Brook.p02 (plan) ---

Plan Title=20 Year Flood
Program Version=4.00
Short Identifier=120 Flood
Geom File=g04
Flow File=f02
Mixed Flow
K Sum by GR= 0
Std Step Tol= 0.01
Critical Tol= 0.01
Num of Std Step Trials= 20
Max Error Tol= 0.3
Flow Tol Ratio= 0.001
Split Flow NTrial= 30
Split Flow Tol= 0.02
Split Flow Ratio= 0.02
Log Output Level= 0
Friction Slope Method= 1
Unsteady Friction Slope Method= 2
Unsteady Bridges Friction Slope Method= 1
Parabolic Critical Depth
Global Vel Dist= 0 , 0 , 0
Global Log Level= 0
CheckData=True
Encroach Param=-1 ,0,0, 0
Computation Interval=1HOUR
Output Interval=1HOUR
Run HTab= 0
Run UNet= 0
Run PostProcess= 0
Run WQNet= 0
UNET Theta= 1
UNET Theta Warmup= 1
UNET ZTol= 0.02
UNET ZSATol= 0.05
UNET MxIter= 20
UNET MaxInSteps= 0
UNET DtIC= 0
UNET DtMin= 0
UNET MaxCRTS= 20
UNET WFStab= 2
UNET SFStab= 1
UNET WFX= 1
UNET SFX= 1
UNET DSS MLevel= 4
UNET DZMax Abort= 100
UNET Convert EG Bridges= 0
UNET Use Existing IB Tables=-1
UNET Froude Reduction=False
UNET Froude Limit= 1
UNET Froude Power= 10
UNET Time Slicing=0,0, 5
Instantaneous Interval=1HOUR
Write IC File= 0
Echo Input=False
Echo Output=False
Write Detailed= 0
Detailed Automatic Start=False, 10
WQ ULTIMATE=-1
WQ Max Comp Step=1HOUR
WQ Output Interval=15MIN
WQ Output Selected Increments= 0
WQ Output face flow=0
WQ Output face velocity=0
WQ Output face area=0
WQ Output face dispersion=0
WQ Output cell volume=0
WQ Output cell surface area=0
WQ Output cell continuity=0
WQ Output face conc=0
WQ Output face dconc_dx=0
WQ Output face courant=0
WQ Output face peclet=0
WQ Output face adv mass=0
WQ Output face disp mass=0
WQ Output cell mass=0
WQ Output cell source sink temp=0
WQ Output cell source sink nsm=0
WQ Output MaxMinRange=-1
WQ Daily Max Min Mean=-1
WQ Daily Range=0
WQ Daily Time=0
WQ Create Restart=0
WQ Fixed Restart=0
WQ System Summary=False
Sorting and Armoring Iterations= 10
XS Update Threshold= 0.02
Hydraulics Update Threshold= 0.02
Energy Slope Method= 1
Volume Change Method= 0
XS Weighting Method= 0
Number of US Weighted Cross Sections= 1
Number of DS Weighted Cross Sections= 1
Upstream XS Weight=0.25
Main XS Weight=0.5
Downstream XS Weight=0.25
Number of DS XS's Weighted with US Boundary= 1
Upstream Boundary Weight= 1
Weight of XSs Associated with US Boundary= 0
Number of US XS's Weighted with DS Boundary= 1
Downstream Boundary Weight= 0.5
Weight of XSs Associated with DS Boundary= 0.5
Sediment Output Level= 4
Mass or Volume Output= 0
Output Increment Type= 1
Profile and TS Output Increment= 10
XS Output Flag= 0
XS Output Increment= 10
Disregard all LS=0
Disregard all Conn=0
Disregard all Breaches=0
Disregard all Pumps=0

--- Cold_Brook.p01 (plan) ---

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Plan Title=WS Profile #1 Calibration
Short Identifier=WS1 Calib
Geom File=g04
Flow File=f01
DSS File=dss

--- Cold_Brook.p03 (plan) ---

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Plan Title=100 Year Flood
Short Identifier=100 Yr Flood
Geom File=g04
Flow File=f03

--- Cold_Brook.p04 (plan) ---

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Plan Title=Sensitivity 1_ + 20% n
Short Identifier=Sens1
Geom File=g01
Flow File=f03
Std Step Tol= 0.003
Critical Tol= 0.003
Max Error Tol= 0.1
Split Flow Tol= 0.006
UNET ZTol= 0.006
UNET ZSATol= 0.015
UNET DZMax Abort= 30

--- Cold_Brook.p05 (plan) ---

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Plan Title=Sensitivity 2_ - 20% n
Short Identifier=Sens2
Geom File=g02
Flow File=f03
Std Step Tol= 0.003
Critical Tol= 0.003
Max Error Tol= 0.1
Split Flow Tol= 0.006
UNET ZTol= 0.006
UNET ZSATol= 0.015
UNET DZMax Abort= 30

--- Cold_Brook.p06 (plan) ---

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Plan Title=Sensitivity 3_ +10% Q
Short Identifier=Sens3
Geom File=g04
Flow File=f05
Std Step Tol= 0.003
Critical Tol= 0.003
Max Error Tol= 0.1
Split Flow Tol= 0.006
UNET ZTol= 0.006
UNET ZSATol= 0.015
UNET DZMax Abort= 30

--- Cold_Brook.p07 (plan) ---

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Plan Title=Sensitivity 4_ -10% Q
Short Identifier=Sens4
Geom File=g04
Flow File=f06
Std Step Tol= 0.003
Critical Tol= 0.003
Max Error Tol= 0.1
Split Flow Tol= 0.006
UNET ZTol= 0.006
UNET ZSATol= 0.015
UNET DZMax Abort= 30

--- Cold_Brook.p08 (plan) ---

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Plan Title=Bridge_Block_100yr
Short Identifier=Block_100yr
Geom File=g06
Flow File=f03
DSS File=dss

--- Cold_Brook.p09 (plan) ---

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Plan Title=2005 Event
Short Identifier=2005 Flood
Geom File=g04
Flow File=f04

--- Cold_Brook.p10 (plan) ---

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Plan Title=Bridge_Block_Ice_20yr
Short Identifier=Block_Ice_20yr
Geom File=g05
Flow File=f02
DSS File=dss

--- Cold_Brook.p12 (plan) ---

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Plan Title=Climate Change
Short Identifier=CC
Geom File=g04
Flow File=f07

--- Cold_Brook.f02 (steady flow) ---

Flow Title=1/20 Year Flood
Program Version=4.00
Number of Profiles= 1
Profile Names=PF 1
River Rch & RM=Cold Brook,Cold Brook      ,1651.192
    78.8
Boundary for River Rch & Prof#=Cold Brook,Cold Brook      , 1
Up Type= 3
Up Slope=0.014
Dn Type= 3
Dn Slope=0.012
DSS Import GetInterval= 0
DSS Import GetPeak= 0
DSS Import FillOption= 0

--- Cold_Brook.f01 (steady flow) ---

Flow Title=WS Profile #1 Calibration
Program Version=4.00
Number of Profiles= 1
Profile Names=PF 1
River Rch & RM=Cold Brook,Cold Brook      ,1651.192
    1.05
Boundary for River Rch & Prof#=Cold Brook,Cold Brook      , 1
Up Type= 3
Up Slope=0.014
Dn Type= 3
Dn Slope=0.012
DSS Import GetInterval= 0
DSS Import GetPeak= 0
DSS Import FillOption= 0

--- Cold_Brook.f03 (steady flow) ---

Flow Title=1/100 Year Flood
Program Version=4.00
Number of Profiles= 1
Profile Names=PF 1
River Rch & RM=Cold Brook,Cold Brook      ,1651.192
   115.7
Boundary for River Rch & Prof#=Cold Brook,Cold Brook      , 1
Up Type= 3
Up Slope=0.014
Dn Type= 3
Dn Slope=0.012
DSS Import GetInterval= 0
DSS Import GetPeak= 0
DSS Import FillOption= 0

--- Cold_Brook.f04 (steady flow) ---

Flow Title=2005 Flood
Program Version=4.00
Number of Profiles= 1
Profile Names=PF 1
River Rch & RM=Cold Brook,Cold Brook      ,1651.192
    56.1
Boundary for River Rch & Prof#=Cold Brook,Cold Brook      , 1
Up Type= 3
Up Slope=0.014
Dn Type= 3
Dn Slope=0.012
DSS Import GetInterval= 0
DSS Import GetPeak= 0
DSS Import FillOption= 0

--- Cold_Brook.f05 (steady flow) ---

Flow Title=1/100 Year Flood Q+10%
Program Version=4.00
Number of Profiles= 1
Profile Names=PF 1
River Rch & RM=Cold Brook,Cold Brook      ,1651.192
  127.27
Boundary for River Rch & Prof#=Cold Brook,Cold Brook      , 1
Up Type= 3
Up Slope=0.014
Dn Type= 3
Dn Slope=0.012
DSS Import GetInterval= 0
DSS Import GetPeak= 0
DSS Import FillOption= 0

--- Cold_Brook.f06 (steady flow) ---

Flow Title=1/100 Year Flood Q-10%
Program Version=4.00
Number of Profiles= 1
Profile Names=PF 1
River Rch & RM=Cold Brook,Cold Brook      ,1651.192
  104.13
Boundary for River Rch & Prof#=Cold Brook,Cold Brook      , 1
Up Type= 3
Up Slope=0.014
Dn Type= 3
Dn Slope=0.012
DSS Import GetInterval= 0
DSS Import GetPeak= 0
DSS Import FillOption= 0

--- Cold_Brook.f07 (steady flow) ---

Flow Title=Climate Change
Program Version=4.00
Number of Profiles= 1
Profile Names=PF 1
River Rch & RM=Cold Brook,Cold Brook      ,1651.192
   180.3
Boundary for River Rch & Prof#=Cold Brook,Cold Brook      , 1
Up Type= 3
Up Slope=0.014
Dn Type= 3
Dn Slope=0.012
DSS Import GetInterval= 0
DSS Import GetPeak= 0
DSS Import FillOption= 0

--- Cold_Brook.g04 (geometry) ---

Geom Title=Base Case Geometry
Program Version=4.00

River Reach=Cold Brook      ,Cold Brook
Reach XY= 30
302744.3828980975384222.63051458302702.3633834235384093.98615427
302701.7169293495384071.36026175302711.4137404285384037.74465001
302709.4743782145384020.29039007302673.2729501855383932.37263629
302637.7179762315383696.41690004302621.2363902395383657.52490622
302549.1537683785383546.43955535302453.6401792515383437.99688479
302406.1258049645383394.36123494302348.4806573755383355.65479738
302334.5310165015383351.21042564302323.5412972775383355.08915007
302313.8444861975383362.20014486302297.0366803285383397.75511881
302285.4005070345383404.21965953 302273.764333745383402.28029732
302266.0068848765383393.22994031302235.0878246145383314.28173677
302218.2321332575383243.79430019302198.311770742 5383222.3416021
302167.6650591855383205.48591075302135.390744299 5383227.3435961
302113.6350539685383221.35579142302079.0055835815383222.55335236
302061.4041711135383218.36411385302045.8892733865383221.75799773
301917.7635715725383150.24846252301865.6148011445383137.21126992

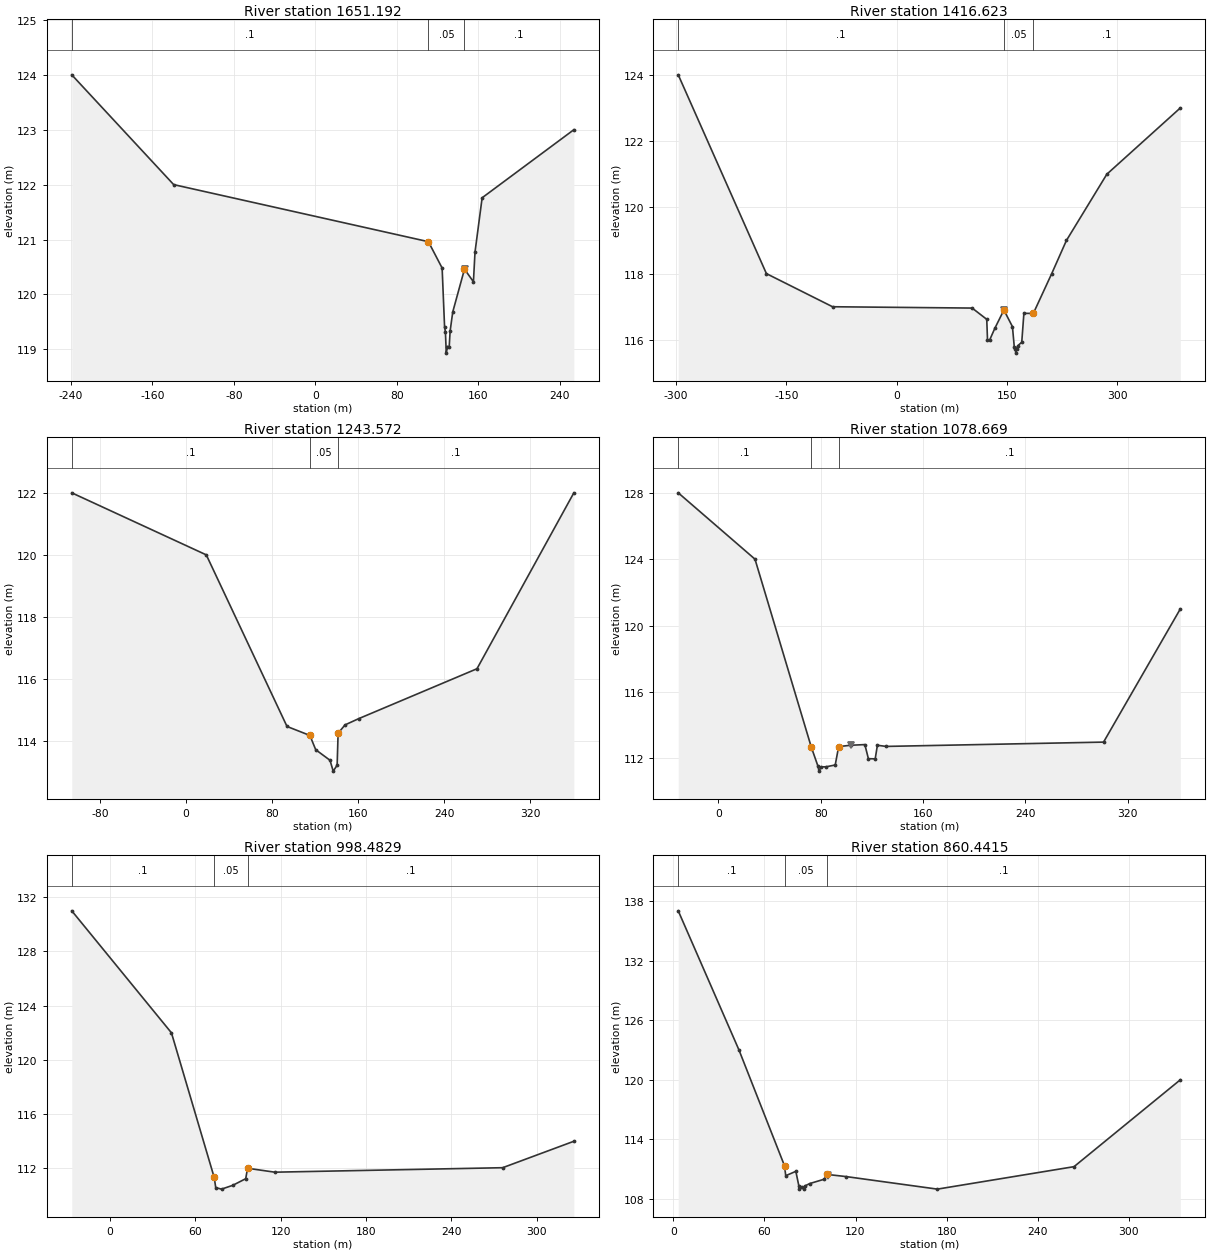
Type RM Length L Ch R = 1 ,1651.192,238.2219,234.5689,230.9031
BEGIN DESCRIPTION:
2008 Surveyed Section
END DESCRIPTION:
Node Name=CB14
XS GIS Cut Line= 6
303104.5560025195384114.02925196       302750.42      5384205.82
       302742.81      5384208.23       302723.04      5384212.79
       302721.74      5384213.62302627.9015597515384238.28981605
#Sta/Elev= 16
-238.997     124-138.997     122 111.003  120.96 124.463  120.48 126.883   119.4
  127.68  119.32 128.523  118.93  129.71  119.05 131.393  119.04   132.3  119.33
 134.883  119.68 146.403  120.46 155.173  120.23 156.723  120.77 163.723  121.76
 253.723     123
#Mann= 3 , 0 , 0
-238.997      .1       0 111.003     .05       0 146.403      .1       0
Levee=0,,,-1,146.48,120.46,,
Bank Sta=111.003,146.403
XS Rating Curve= 0 ,0
Exp/Cntr=0.3,0.1

Type RM Length L Ch R = 1 ,1416.623,177.3689,173.0512,170.1619
BEGIN DESCRIPTION:
2008 Surveyed Section
END DESCRIPTION:
Node Name=CB13
XS GIS Cut Line= 6
303122.542610977 5383882.1600704       302703.61       5383982.9
       302677.98      5383989.21       302667.92       5383991.1
       302665.26      5383992.27302458.2830527135384042.02493422
#Sta/Elev= 22
-297.205     124-177.205     118 -87.205     117 102.795  116.96 122.665  116.62
 123.675  116.01 126.485  115.99 133.685  116.35 145.985   116.9 157.625   116.4
 160.075   115.8  161.54  115.72 162.205   115.6  163.17  115.73  164.75  115.82
 170.305  115.93 173.215   116.8 186.085   116.8 211.085     118 231.085     119
 286.085     121 386.085     123
#Mann= 3 , 0 , 0
-297.205      .1       0 145.985     .05       0 186.085      .1       0
Levee=-1,145.9,116.9,0,,,,
Bank Sta=145.985,186.085
XS Rating Curve= 0 ,0
Exp/Cntr=0.3,0.1

Type RM Length L Ch R = 1 ,1243.572,166.9371,164.9032,162.5209
BEGIN DESCRIPTION:
2008 Surveyed Section
END DESCRIPTION:
Node Name=CB12
XS GIS Cut Line= 6
 302877.230889015383728.36984509       302671.96      5383810.92
       302666.91       5383812.9       302647.63      5383820.72
       302641.73      5383823.24302404.5235813415383915.17935716
#Sta/Elev= 13
-106.059     122 18.9409     120 93.9409  114.47115.1909  114.18120.6109  113.72
133.8909  113.38136.8509  113.03140.5209  113.22141.4109  114.25147.8309  114.52
160.4609  114.72270.4609  116.33360.4609     122
#Mann= 3 , 0 , 0
-106.059      .1       0115.1909     .05       0141.4109      .1       0
Bank Sta=115.1909,141.4109
XS Rating Curve= 0 ,0
Exp/Cntr=0.3,0.1

Type RM Length L Ch R = 1 ,1078.669,82.007,80.1871,79.0151
BEGIN DESCRIPTION:
2008 Surveyed Section
END DESCRIPTION:
Node Name=CB11
XS GIS Cut Line= 5
302731.5332010695383605.28296082302632.1686120595383652.47065912
       302584.77      5383674.98302584.7620994935383674.98375256
302377.0064247215383773.66292767
#Sta/Elev= 17
 -31.407     128  28.593     124   72.52  112.69   77.86  111.51  78.593  111.22
   80.36  111.48  84.073  111.48  91.313  111.59  93.993   112.7 103.443  112.78
 114.473  112.82 117.243  111.97 122.563  111.96 124.283  112.78 131.073  112.71
 301.073  112.97 361.073     121
#Mann= 3 , 0 , 0
 -31.407      .1       0   72.52     .05       0  93.993      .1       0
Levee=0,,,-1,103.7,112.77,,
Bank Sta=72.52,93.993
XS Rating Curve= 0 ,0
Exp/Cntr=0.3,0.1

Type RM Length L Ch R = 1 ,998.4829,145.8871,138.0412,131.6089
BEGIN DESCRIPTION:
2008 Surveyed Section
END DESCRIPTION:
Node Name=CB10
XS GIS Cut Line= 5
302680.7180018525383537.35080486302591.8219915895383583.14927778
       302553.99      5383602.64302553.9693251545383602.65064872
302367.2774698185383698.80755773
#Sta/Elev= 11
 -26.645     131  43.355     122  73.355  111.34  74.465  110.58  78.515  110.47
  86.405  110.75  95.515  111.24  96.795  112.01 115.935  111.72 275.935  112.05
 325.935     114
#Mann= 3 , 0 , 0
 -26.645      .1       0  73.355     .05       0  96.795      .1       0
Bank Sta=73.355,96.795
XS Rating Curve= 0 ,0
Exp/Cntr=0.3,0.1

Type RM Length L Ch R = 1 ,860.4415,218.036,193.7269,170.175
BEGIN DESCRIPTION:
2008 Surveyed Section
END DESCRIPTION:
Node Name=CB9
XS GIS Cut Line= 5
302551.5308580875383416.88666674302504.6824090895383468.89842753
       302477.47      5383499.11 302477.454689675383499.12699193
302330.1889804835383662.56753432
#Sta/Elev= 18
  3.2459     137 43.2459     123 73.2459  111.35 74.0459  110.35 80.7059  110.79
   82.67  109.34 82.8659  109.05   83.62  109.19      85  109.17 85.7559  109.06
   86.56  109.31 89.8359  109.56 99.4559     110101.3059  110.48113.9259  110.26
173.9259     109263.9259  111.26333.9259     120
#Mann= 3 , 0 , 0
  3.2459      .1       0 73.2459     .05       0101.3059      .1       0
Levee=0,,,-1,102.07,110.37,,
Bank Sta=73.2459,101.3059
XS Rating Curve= 0 ,0
Exp/Cntr=0.3,0.1

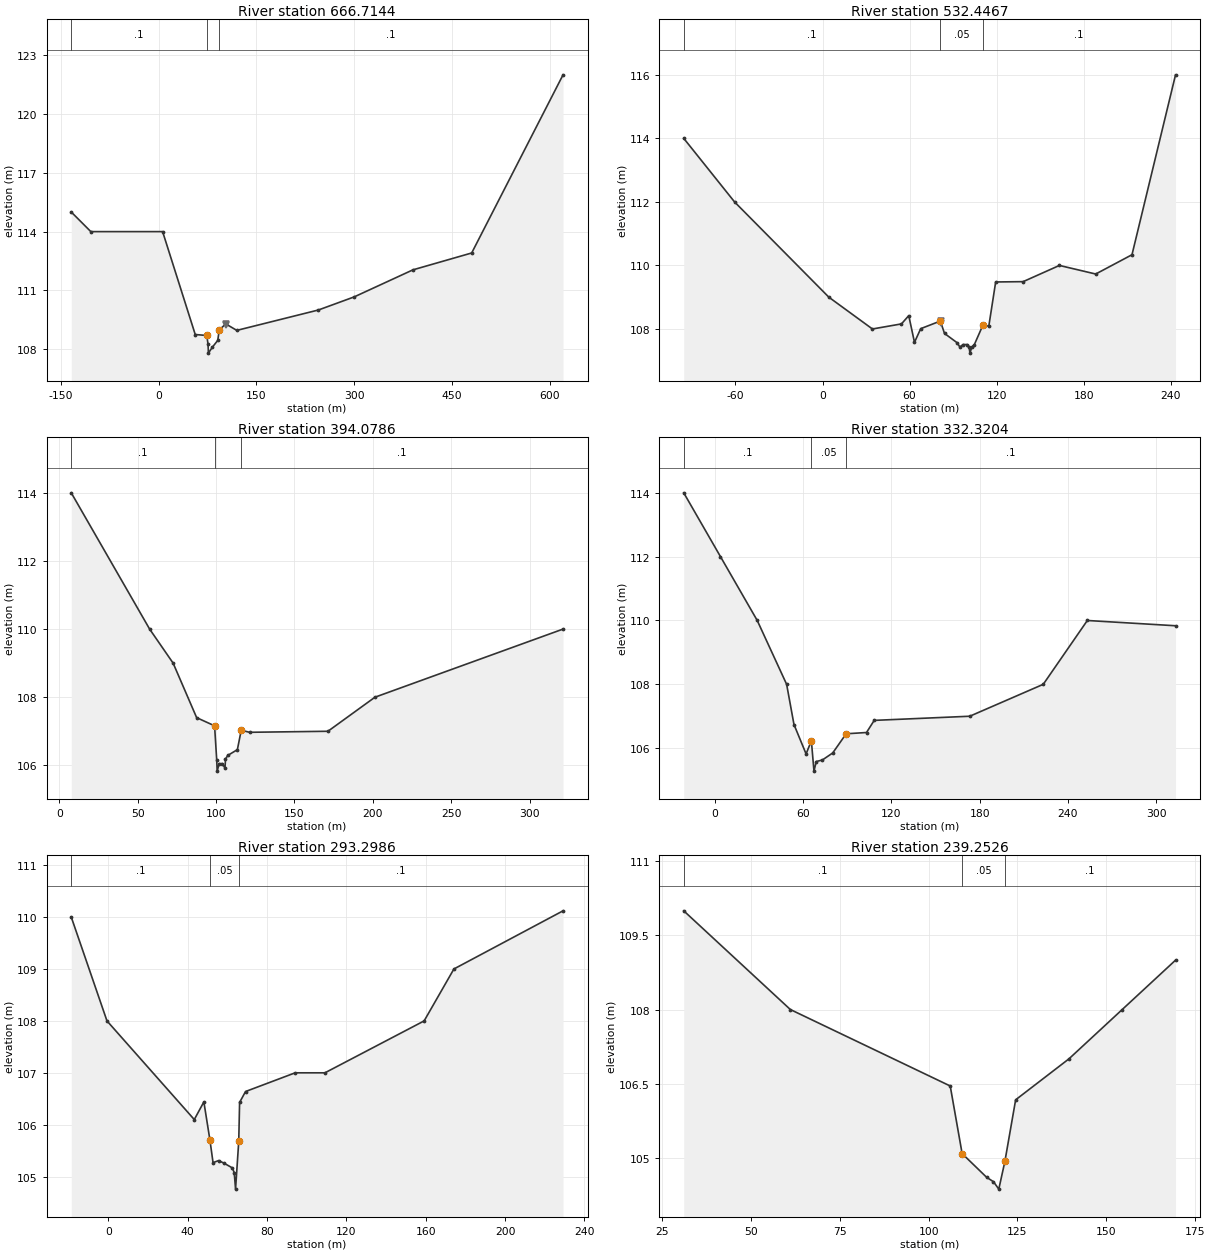
Type RM Length L Ch R = 1 ,666.7144,95.222,134.2681,147.5351
BEGIN DESCRIPTION:
2008 Surveyed Section
END DESCRIPTION:
Node Name=CB8
XS GIS Cut Line= 5
302309.660876732 5383142.0369652302342.9319936375383329.10120906
       302354.08      5383391.78302354.0822810495383391.79281784
302441.6853851675383884.05869737
#Sta/Elev= 17
-133.769     115-103.769     114   6.231     114  56.231  108.75  73.961   108.7
   75.84  108.25  76.441   107.8  82.421   108.1  90.761  108.45  93.041  108.99
 103.141  109.29 119.901  108.96 244.901     110 299.901  110.67 389.901  112.05
 479.901  112.91 619.901     122
#Mann= 3 , 0 , 0
-133.769      .1       0  73.961     .05       0  93.041      .1       0
Levee=0,,,-1,103.96,109.26,,
Bank Sta=73.961,93.041
XS Rating Curve= 0 ,0
Exp/Cntr=0.3,0.1

Type RM Length L Ch R = 1 ,532.4467,110.786,138.368,163.0351
BEGIN DESCRIPTION:
2008 Surveyed Section
END DESCRIPTION:
Node Name=CB7
XS GIS Cut Line= 6
302307.898546136 5383196.5195647       302255.66      5383386.69
       302254.96      5383389.55       302252.13      5383399.19
       302251.04      5383403.78302217.8405261075383523.15404519
#Sta/Elev= 26
-95.6039     114-60.6039     112  4.3961     109 34.3961     108 54.3961  108.16
 59.4261  108.42 63.3661  107.58 67.6661  108.01 81.1961  108.25 84.0561  107.86
   92.66  107.57 94.6861  107.43   96.81  107.51   99.79  107.51  100.98  107.43
101.5961  107.24  102.91  107.44104.5361   107.5110.4961  108.12114.5861  108.09
119.3061  109.48138.2261  109.49163.2261     110188.2261  109.73213.2261 110.337
243.2261     116
#Mann= 3 , 0 , 0
-95.6039      .1       0 81.1961     .05       0110.4961      .1       0
Levee=-1,81.63,108.25,0,,,,
Bank Sta=81.1961,110.4961
XS Rating Curve= 0 ,0
Exp/Cntr=0.3,0.1

Type RM Length L Ch R = 1 ,394.0786,89.1241,61.758,42.088
BEGIN DESCRIPTION:
2008 Surveyed Section
END DESCRIPTION:
Node Name=CB6
XS GIS Cut Line= 5
302309.684634197  5383205.989302 302235.307203745383235.45110763
       302203.93      5383247.88302203.9215379985383247.88335398
302017.9936180995383321.57733269
#Sta/Elev= 18
   7.609     114  57.609     110  72.609     109  87.609   107.4  99.049  107.16
  100.41  106.16 100.699  105.83  101.98  106.05  104.02  106.05 105.689  105.92
  106.01  106.18  107.42  106.29 113.589  106.46 116.049  107.03 121.369  106.97
 171.369     107 201.369     108 321.369     110
#Mann= 3 , 0 , 0
   7.609      .1       0  99.049     .05       0 116.049      .1       0
Bank Sta=99.049,116.049
XS Rating Curve= 0 ,0
Exp/Cntr=0.3,0.1

Type RM Length L Ch R = 1 ,332.3204,42.245,39.022,37.252
BEGIN DESCRIPTION:
2008 Surveyed Section
END DESCRIPTION:
Node Name=CB5
XS GIS Cut Line= 6
 302140.009747315383102.75086354       302159.96      5383175.05
       302174.47      5383227.66       302179.77       5383246.9
302179.7723645545383246.90858378302234.2153769155383444.54704545
#Sta/Elev= 18
-21.3171     114  3.6829     112 28.6829     110 48.6829     108 53.6829  106.74
 61.9129  105.82 65.5129  106.23 67.2829  105.28   68.82  105.58 73.0229  105.63
 80.0529  105.85 89.1729  106.45103.0229  106.49108.2629  106.87173.2629     107
223.2629     108253.2629     110313.2629 109.835
#Mann= 3 , 0 , 0
-21.3171      .1       0 65.5129     .05       0 89.1729      .1       0
Bank Sta=65.5129,89.1729
XS Rating Curve= 0 ,0
Exp/Cntr=0.3,0.1

Type RM Length L Ch R = 1 ,293.2986,47.012,54.0459,56.434
BEGIN DESCRIPTION:
2008 Surveyed Section
END DESCRIPTION:
Node Name=CB4
XS GIS Cut Line= 6
302113.6629236345383154.51017114302132.2495602445383213.65860056
       302132.25      5383213.66        302139.9      5383238.01
302139.9949404555383238.31228012302187.9387607895383390.96020867
#Sta/Elev= 19
 -18.637     110   -.637     108  43.363   106.1  48.193  106.44   51.23  105.71
  52.823  105.27   55.61  105.31  58.343  105.26   62.49  105.17   63.49  105.08
  64.163  104.76   65.77  105.68  66.203  106.43  69.203  106.64  94.203     107
 109.203     107 159.203     108 174.203     109 229.203  110.12
#Mann= 3 , 0 , 0
 -18.637      .1       0   51.23     .05       0   65.77      .1       0
Bank Sta=51.23,65.77
XS Rating Curve= 0 ,0
Exp/Cntr=0.3,0.1

Type RM Length L Ch R = 1 ,239.2526,30.306,23.6769,21.575
BEGIN DESCRIPTION:
2008 Surveyed Section
END DESCRIPTION:
Node Name=CB3
XS GIS Cut Line= 6
302107.228518281   5383144.78118       302084.35      5383219.72
       302083.05      5383226.48       302082.49      5383229.87
       302081.83      5383231.45302073.2665160465383278.70774483
#Sta/Elev= 12
 31.0841     110 61.0841     108106.0841  106.45109.4341  105.08116.3241   104.6
  118.26  104.51119.7541  104.36121.4641  104.92124.4941  106.17139.4941     107
154.4941     108169.4941     109
#Mann= 3 , 0 , 0
 31.0841      .1       0109.4341     .05       0121.4641      .1       0
Bank Sta=109.4341,121.4641
XS Rating Curve= 0 ,0
Exp/Cntr=0.3,0.1

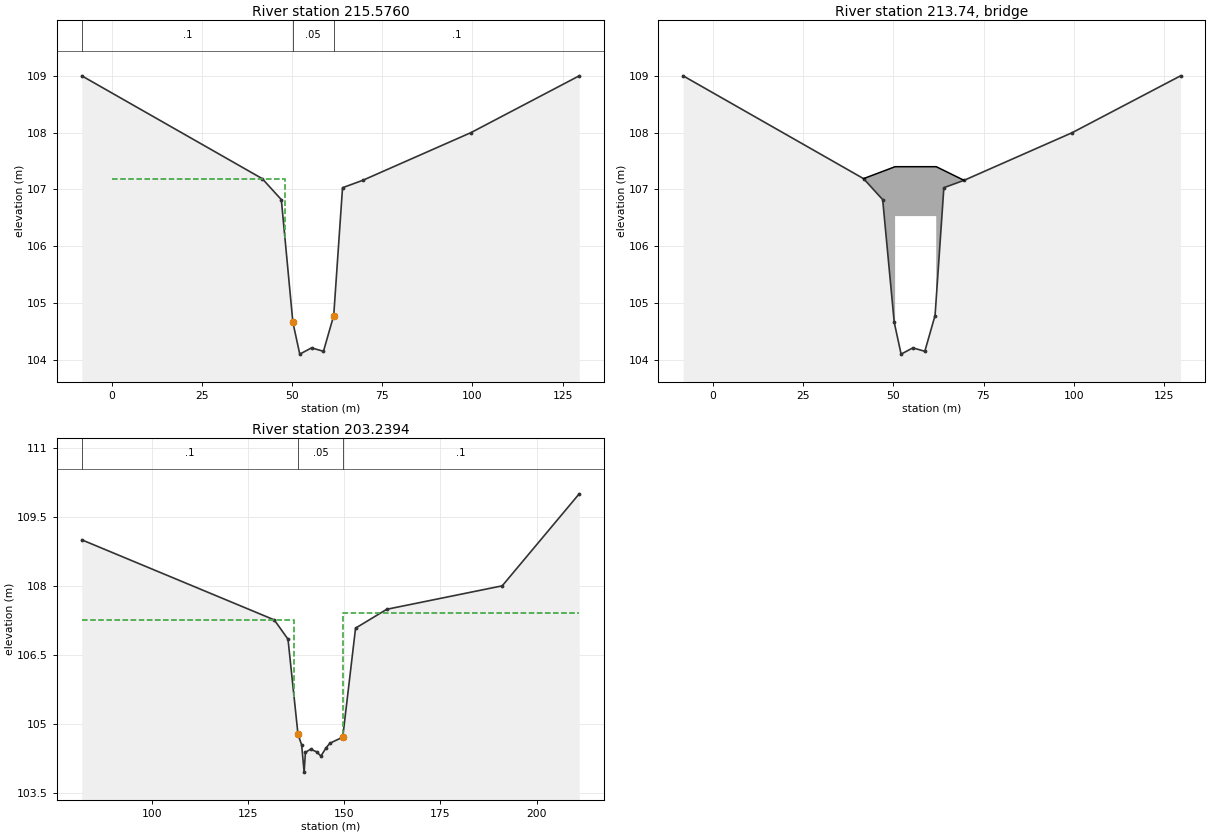
Type RM Length L Ch R = 1 ,215.5760,12.384,12.3371,12.0631
BEGIN DESCRIPTION:
2008 Surveyed Section
END DESCRIPTION:
Node Name=CB2
XS GIS Cut Line= 6
302047.9611401925383154.28453846       302059.16      5383208.44
       302059.37      5383211.63       302060.84      5383219.98
       302061.15      5383225.26302066.5475137735383290.61685156
#Sta/Elev= 12
 -8.2461     109 41.7539  107.19 47.0539  106.82 50.2539  104.66 52.1639   104.1
   55.42  104.21 58.7339  104.15 61.5739  104.78 64.0139  107.03 69.6039  107.16
 99.6039     108129.6039     109
#Mann= 3 , 0 , 0
 -8.2461      .1       0 50.2539     .05       0 61.5739      .1       0
#XS Ineff= 2 , 0
       0    48.1  107.19               0
Permanent Ineff=
       F       F
Bank Sta=50.2539,61.5739
XS Rating Curve= 0 ,0
Exp/Cntr=0.3,0.1

Type RM Length L Ch R = 3 ,213.74  ,,,
BEGIN DESCRIPTION:
Downey Bridge
END DESCRIPTION:
Bridge Culvert--1,0,-1,-1, 0
Deck Dist Width WeirC Skew NumUp NumDn MinLoCord MaxHiCord MaxSubmerge Is_Ogee
1.84,8.94,1.4,0, 6, 6, , , 0.98, 0, 1,1,,
   41.75    50.5    50.5    61.9    61.9    69.6
  107.19   107.4   107.4   107.4   107.4  107.16
       0       0  106.53  106.53       0       0
  131.84     138     138   149.4   149.4  161.08
  107.26   107.4   107.4   107.4   107.4  107.49
       0       0  106.53  106.53       0       0
BR Coef=-1 , 0 , 0 ,, 0 ,,,0.8,-1,,0,
WSPro=,,,, 1 ,,,, 0 ,,,, 0 ,,,,-1 ,-1 ,-1 , 0 , 0 , 0 , 0 , 0
BC Design=,, 0 ,, 0 ,,,,,,
BC Use User HTab Curves=0
BC User HTab FreeFlow(D)= 0

Type RM Length L Ch R = 1 ,203.2394,14.82,18.333,21.635
BEGIN DESCRIPTION:
2008 Surveyed Section
END DESCRIPTION:
Node Name=CB1
XS GIS Cut Line= 6
302043.7594587715383156.05834963302047.324775004  5383209.524511
     302047.6632   5383212.09917302047.5726280015383213.69434401
302048.286598008  5383217.998802302055.7078834235383284.68031414
#Sta/Elev= 17
 81.8379     109131.8379  107.26135.4179  106.84138.0179  104.77  138.97  104.54
139.6079  103.95  139.94  104.38  141.32  104.45  142.84  104.39143.9779   104.3
  145.32  104.48  146.33  104.58149.6379  104.71152.9679  107.08161.0779  107.49
191.0779     108211.0779     110
#Mann= 3 , 0 , 0
 81.8379      .1       0138.0179     .05       0149.6379      .1       0
#XS Ineff= 2 , 0
       0     137  107.26   149.7       0   107.4
Permanent Ineff=
       F       F
Bank Sta=138.0179,149.6379
XS Rating Curve= 0 ,0
Exp/Cntr=0.3,0.1

Chan Stop Cuts=-1
Use User Specified Reach Order=0

--- Cold_Brook.g01 (geometry) ---

Geom Title=Base Case + 20% n
Program Version=4.00

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
River Reach=Cold Brook      ,Cold Brook

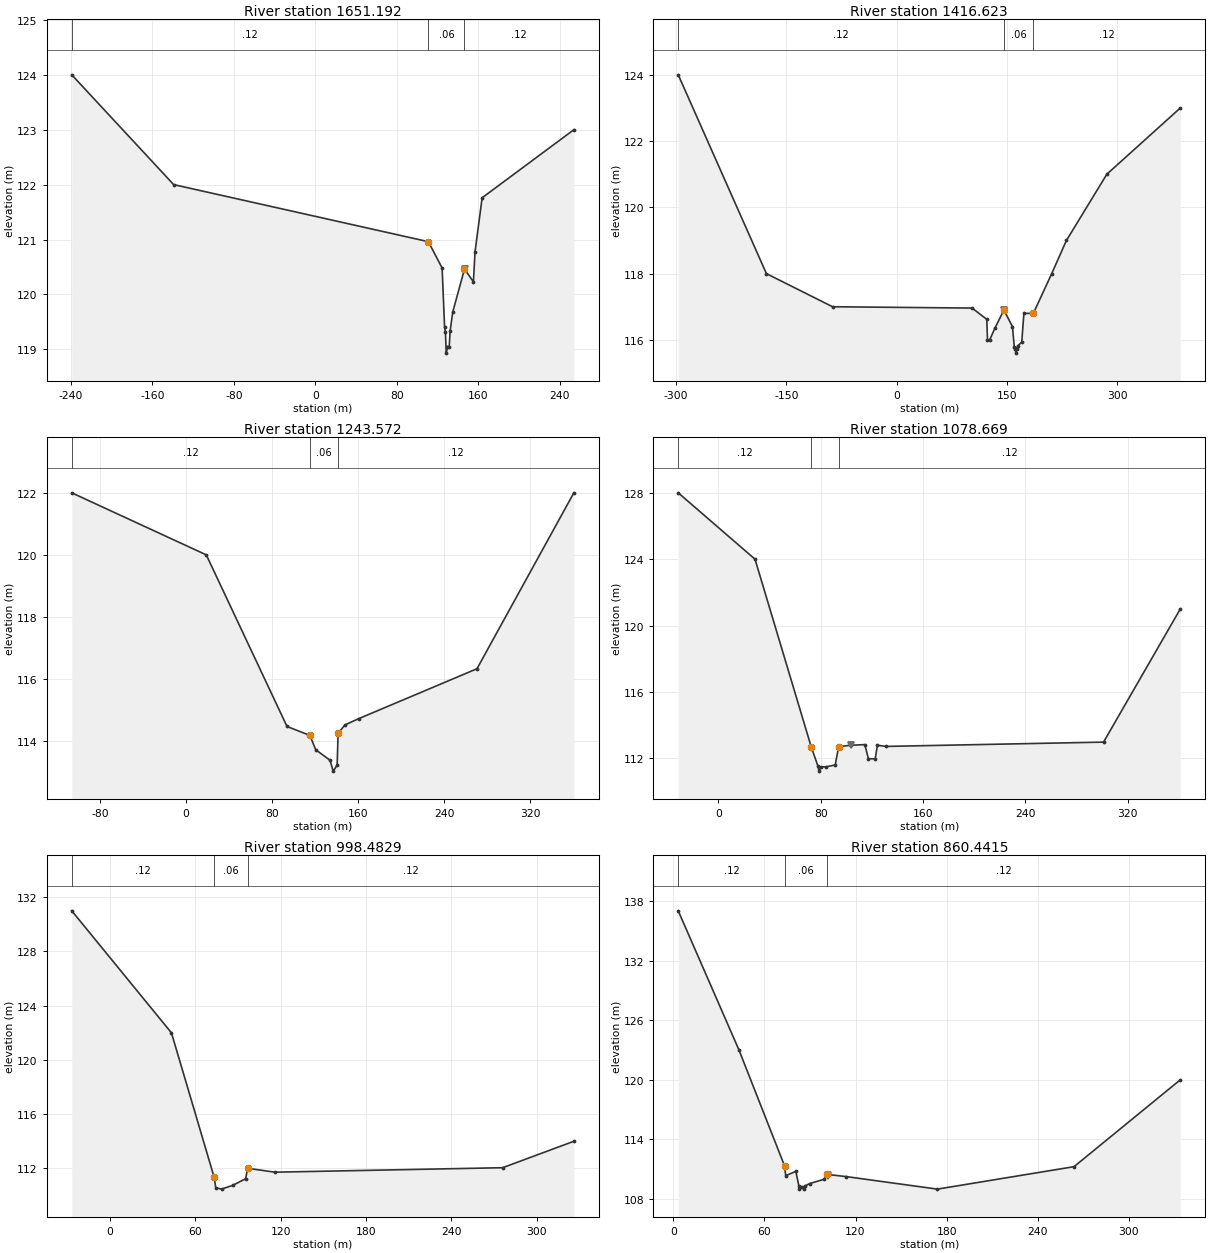
Type RM Length L Ch R = 1 ,1651.192,238.2219,234.5689,230.9031
Node Name=CB14
XS GIS Cut Line= 6
303104.5560025195384114.02925196       302750.42      5384205.82
       302742.81      5384208.23       302723.04      5384212.79
       302721.74      5384213.62302627.9015597515384238.28981605
#Sta/Elev= 16
-238.997     124-138.997     122 111.003  120.96 124.463  120.48 126.883   119.4
  127.68  119.32 128.523  118.93  129.71  119.05 131.393  119.04   132.3  119.33
 134.883  119.68 146.403  120.46 155.173  120.23 156.723  120.77 163.723  121.76
 253.723     123
#Mann= 3 , 0 , 0
-238.997     .12       0 111.003     .06       0 146.403     .12       0
Levee=0,,,-1,146.48,120.46,,
Bank Sta=111.003,146.403
XS Rating Curve= 0 ,0
Exp/Cntr=0.3,0.1

Type RM Length L Ch R = 1 ,1416.623,177.3689,173.0512,170.1619
Node Name=CB13
XS GIS Cut Line= 6
303122.542610977 5383882.1600704       302703.61       5383982.9
       302677.98      5383989.21       302667.92       5383991.1
       302665.26      5383992.27302458.2830527135384042.02493422
#Sta/Elev= 22
-297.205     124-177.205     118 -87.205     117 102.795  116.96 122.665  116.62
 123.675  116.01 126.485  115.99 133.685  116.35 145.985   116.9 157.625   116.4
 160.075   115.8  161.54  115.72 162.205   115.6  163.17  115.73  164.75  115.82
 170.305  115.93 173.215   116.8 186.085   116.8 211.085     118 231.085     119
 286.085     121 386.085     123
#Mann= 3 , 0 , 0
-297.205     .12       0 145.985     .06       0 186.085     .12       0
Levee=-1,145.9,116.9,0,,,,
Bank Sta=145.985,186.085
XS Rating Curve= 0 ,0
Exp/Cntr=0.3,0.1

Type RM Length L Ch R = 1 ,1243.572,166.9371,164.9032,162.5209
Node Name=CB12
XS GIS Cut Line= 6
 302877.230889015383728.36984509       302671.96      5383810.92
       302666.91       5383812.9       302647.63      5383820.72
       302641.73      5383823.24302404.5235813415383915.17935716
#Sta/Elev= 13
-106.059     122 18.9409     120 93.9409  114.47115.1909  114.18120.6109  113.72
133.8909  113.38136.8509  113.03140.5209  113.22141.4109  114.25147.8309  114.52
160.4609  114.72270.4609  116.33360.4609     122
#Mann= 3 , 0 , 0
-106.059     .12       0115.1909     .06       0141.4109     .12       0
Bank Sta=115.1909,141.4109
XS Rating Curve= 0 ,0
Exp/Cntr=0.3,0.1

Type RM Length L Ch R = 1 ,1078.669,82.007,80.1871,79.0151
Node Name=CB11
XS GIS Cut Line= 5
302731.5332010695383605.28296082302632.1686120595383652.47065912
       302584.77      5383674.98302584.7620994935383674.98375256
302377.0064247215383773.66292767
#Sta/Elev= 17
 -31.407     128  28.593     124   72.52  112.69   77.86  111.51  78.593  111.22
   80.36  111.48  84.073  111.48  91.313  111.59  93.993   112.7 103.443  112.78
 114.473  112.82 117.243  111.97 122.563  111.96 124.283  112.78 131.073  112.71
 301.073  112.97 361.073     121
#Mann= 3 , 0 , 0
 -31.407     .12       0   72.52     .06       0  93.993     .12       0
Levee=0,,,-1,103.7,112.77,,
Bank Sta=72.52,93.993
XS Rating Curve= 0 ,0
Exp/Cntr=0.3,0.1

Type RM Length L Ch R = 1 ,998.4829,145.8871,138.0412,131.6089
Node Name=CB10
XS GIS Cut Line= 5
302680.7180018525383537.35080486302591.8219915895383583.14927778
       302553.99      5383602.64302553.9693251545383602.65064872
302367.2774698185383698.80755773
#Sta/Elev= 11
 -26.645     131  43.355     122  73.355  111.34  74.465  110.58  78.515  110.47
  86.405  110.75  95.515  111.24  96.795  112.01 115.935  111.72 275.935  112.05
 325.935     114
#Mann= 3 , 0 , 0
 -26.645     .12       0  73.355     .06       0  96.795     .12       0
Bank Sta=73.355,96.795
XS Rating Curve= 0 ,0
Exp/Cntr=0.3,0.1

Type RM Length L Ch R = 1 ,860.4415,218.036,193.7269,170.175
Node Name=CB9
XS GIS Cut Line= 5
302551.5308580875383416.88666674302504.6824090895383468.89842753
       302477.47      5383499.11 302477.454689675383499.12699193
302330.1889804835383662.56753432
#Sta/Elev= 18
  3.2459     137 43.2459     123 73.2459  111.35 74.0459  110.35 80.7059  110.79
   82.67  109.34 82.8659  109.05   83.62  109.19      85  109.17 85.7559  109.06
   86.56  109.31 89.8359  109.56 99.4559     110101.3059  110.48113.9259  110.26
173.9259     109263.9259  111.26333.9259     120
#Mann= 3 , 0 , 0
  3.2459     .12       0 73.2459     .06       0101.3059     .12       0
Levee=0,,,-1,102.07,110.37,,
Bank Sta=73.2459,101.3059
XS Rating Curve= 0 ,0
Exp/Cntr=0.3,0.1

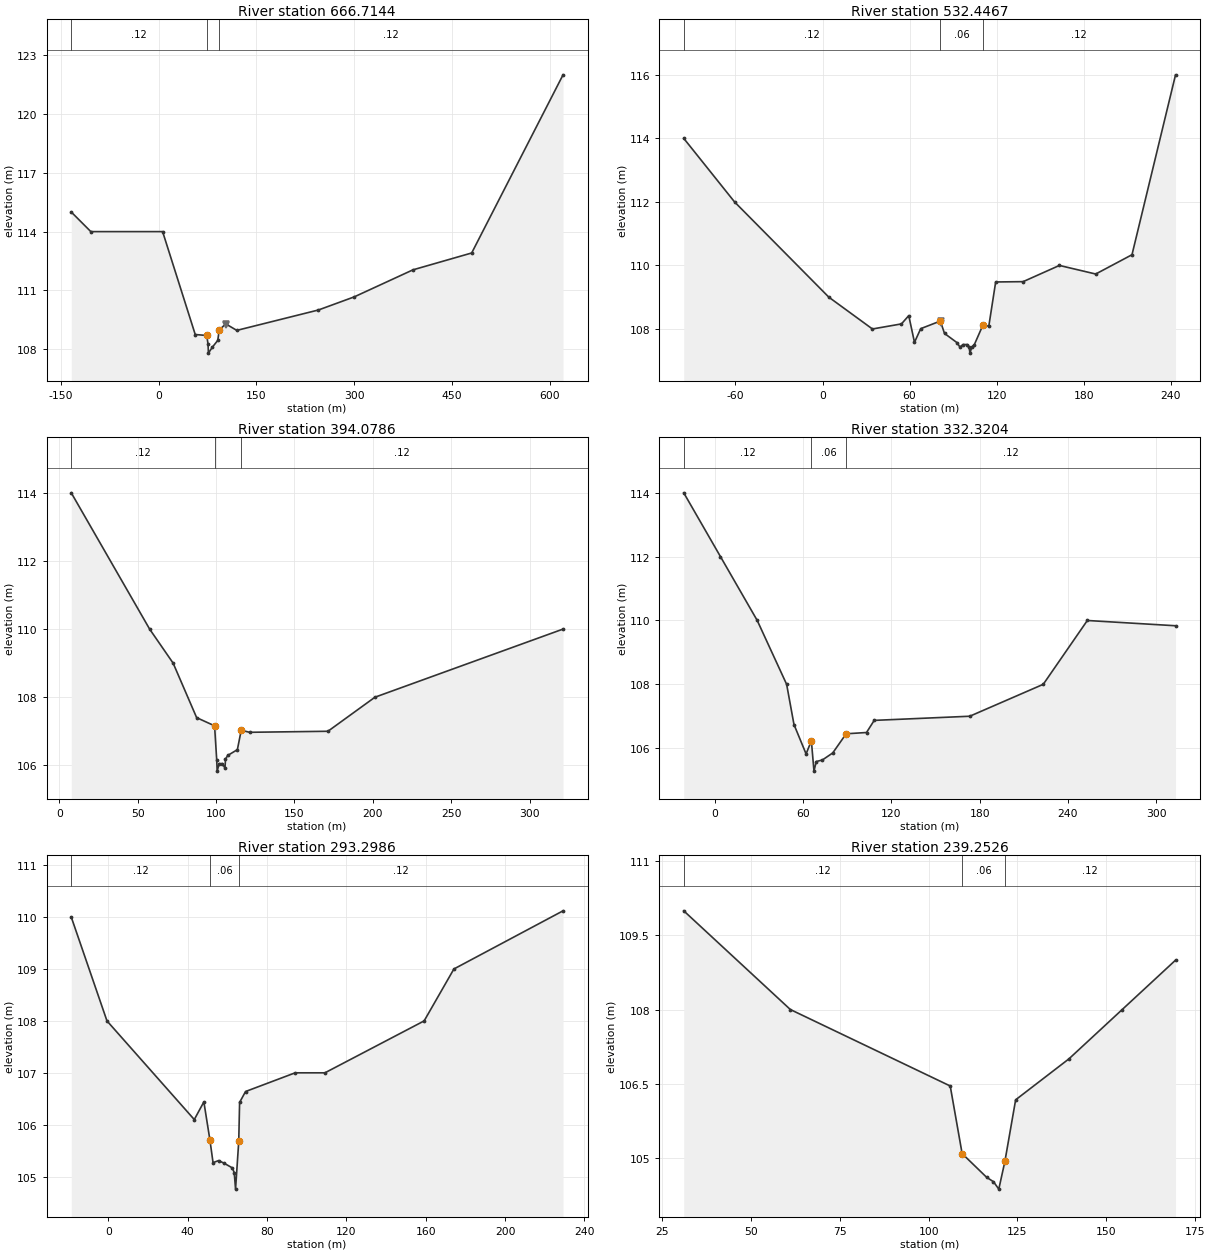
Type RM Length L Ch R = 1 ,666.7144,95.222,134.2681,147.5351
Node Name=CB8
XS GIS Cut Line= 5
302309.660876732 5383142.0369652302342.9319936375383329.10120906
       302354.08      5383391.78302354.0822810495383391.79281784
302441.6853851675383884.05869737
#Sta/Elev= 17
-133.769     115-103.769     114   6.231     114  56.231  108.75  73.961   108.7
   75.84  108.25  76.441   107.8  82.421   108.1  90.761  108.45  93.041  108.99
 103.141  109.29 119.901  108.96 244.901     110 299.901  110.67 389.901  112.05
 479.901  112.91 619.901     122
#Mann= 3 , 0 , 0
-133.769     .12       0  73.961     .06       0  93.041     .12       0
Levee=0,,,-1,103.96,109.26,,
Bank Sta=73.961,93.041
XS Rating Curve= 0 ,0
Exp/Cntr=0.3,0.1

Type RM Length L Ch R = 1 ,532.4467,110.786,138.368,163.0351
Node Name=CB7
XS GIS Cut Line= 6
302307.898546136 5383196.5195647       302255.66      5383386.69
       302254.96      5383389.55       302252.13      5383399.19
       302251.04      5383403.78302217.8405261075383523.15404519
#Sta/Elev= 26
-95.6039     114-60.6039     112  4.3961     109 34.3961     108 54.3961  108.16
 59.4261  108.42 63.3661  107.58 67.6661  108.01 81.1961  108.25 84.0561  107.86
   92.66  107.57 94.6861  107.43   96.81  107.51   99.79  107.51  100.98  107.43
101.5961  107.24  102.91  107.44104.5361   107.5110.4961  108.12114.5861  108.09
119.3061  109.48138.2261  109.49163.2261     110188.2261  109.73213.2261 110.337
243.2261     116
#Mann= 3 , 0 , 0
-95.6039     .12       0 81.1961     .06       0110.4961     .12       0
Levee=-1,81.63,108.25,0,,,,
Bank Sta=81.1961,110.4961
XS Rating Curve= 0 ,0
Exp/Cntr=0.3,0.1

Type RM Length L Ch R = 1 ,394.0786,89.1241,61.758,42.088
Node Name=CB6
XS GIS Cut Line= 5
302309.684634197  5383205.989302 302235.307203745383235.45110763
       302203.93      5383247.88302203.9215379985383247.88335398
302017.9936180995383321.57733269
#Sta/Elev= 18
   7.609     114  57.609     110  72.609     109  87.609   107.4  99.049  107.16
  100.41  106.16 100.699  105.83  101.98  106.05  104.02  106.05 105.689  105.92
  106.01  106.18  107.42  106.29 113.589  106.46 116.049  107.03 121.369  106.97
 171.369     107 201.369     108 321.369     110
#Mann= 3 , 0 , 0
   7.609     .12       0  99.049     .06       0 116.049     .12       0
Bank Sta=99.049,116.049
XS Rating Curve= 0 ,0
Exp/Cntr=0.3,0.1

Type RM Length L Ch R = 1 ,332.3204,42.245,39.022,37.252
Node Name=CB5
XS GIS Cut Line= 6
 302140.009747315383102.75086354       302159.96      5383175.05
       302174.47      5383227.66       302179.77       5383246.9
302179.7723645545383246.90858378302234.2153769155383444.54704545
#Sta/Elev= 18
-21.3171     114  3.6829     112 28.6829     110 48.6829     108 53.6829  106.74
 61.9129  105.82 65.5129  106.23 67.2829  105.28   68.82  105.58 73.0229  105.63
 80.0529  105.85 89.1729  106.45103.0229  106.49108.2629  106.87173.2629     107
223.2629     108253.2629     110313.2629 109.835
#Mann= 3 , 0 , 0
-21.3171     .12       0 65.5129     .06       0 89.1729     .12       0
Bank Sta=65.5129,89.1729
XS Rating Curve= 0 ,0
Exp/Cntr=0.3,0.1

Type RM Length L Ch R = 1 ,293.2986,47.012,54.0459,56.434
Node Name=CB4
XS GIS Cut Line= 6
302113.6629236345383154.51017114302132.2495602445383213.65860056
       302132.25      5383213.66        302139.9      5383238.01
302139.9949404555383238.31228012302187.9387607895383390.96020867
#Sta/Elev= 19
 -18.637     110   -.637     108  43.363   106.1  48.193  106.44   51.23  105.71
  52.823  105.27   55.61  105.31  58.343  105.26   62.49  105.17   63.49  105.08
  64.163  104.76   65.77  105.68  66.203  106.43  69.203  106.64  94.203     107
 109.203     107 159.203     108 174.203     109 229.203  110.12
#Mann= 3 , 0 , 0
 -18.637     .12       0   51.23     .06       0   65.77     .12       0
Bank Sta=51.23,65.77
XS Rating Curve= 0 ,0
Exp/Cntr=0.3,0.1

Type RM Length L Ch R = 1 ,239.2526,30.306,23.6769,21.575
Node Name=CB3
XS GIS Cut Line= 6
302107.228518281   5383144.78118       302084.35      5383219.72
       302083.05      5383226.48       302082.49      5383229.87
       302081.83      5383231.45302073.2665160465383278.70774483
#Sta/Elev= 12
 31.0841     110 61.0841     108106.0841  106.45109.4341  105.08116.3241   104.6
  118.26  104.51119.7541  104.36121.4641  104.92124.4941  106.17139.4941     107
154.4941     108169.4941     109
#Mann= 3 , 0 , 0
 31.0841     .12       0109.4341     .06       0121.4641     .12       0
Bank Sta=109.4341,121.4641
XS Rating Curve= 0 ,0
Exp/Cntr=0.3,0.1

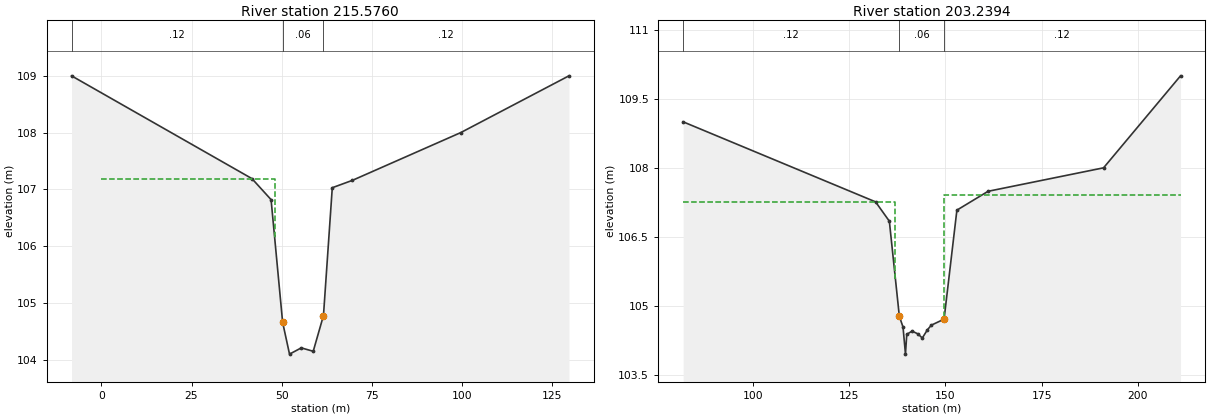
Type RM Length L Ch R = 1 ,215.5760,12.384,12.3371,12.0631
Node Name=CB2
XS GIS Cut Line= 6
302047.9611401925383154.28453846       302059.16      5383208.44
       302059.37      5383211.63       302060.84      5383219.98
       302061.15      5383225.26302066.5475137735383290.61685156
#Sta/Elev= 12
 -8.2461     109 41.7539  107.19 47.0539  106.82 50.2539  104.66 52.1639   104.1
   55.42  104.21 58.7339  104.15 61.5739  104.78 64.0139  107.03 69.6039  107.16
 99.6039     108129.6039     109
#Mann= 3 , 0 , 0
 -8.2461     .12       0 50.2539     .06       0 61.5739     .12       0
#XS Ineff= 2 , 0
       0    48.1  107.19               0
Permanent Ineff=
       F       F
Bank Sta=50.2539,61.5739
XS Rating Curve= 0 ,0
Exp/Cntr=0.3,0.1

Type RM Length L Ch R = 1 ,203.2394,14.82,18.333,21.635
Node Name=CB1
XS GIS Cut Line= 6
302043.7594587715383156.05834963302047.324775004  5383209.524511
     302047.6632   5383212.09917302047.5726280015383213.69434401
302048.286598008  5383217.998802302055.7078834235383284.68031414
#Sta/Elev= 17
 81.8379     109131.8379  107.26135.4179  106.84138.0179  104.77  138.97  104.54
139.6079  103.95  139.94  104.38  141.32  104.45  142.84  104.39143.9779   104.3
  145.32  104.48  146.33  104.58149.6379  104.71152.9679  107.08161.0779  107.49
191.0779     108211.0779     110
#Mann= 3 , 0 , 0
 81.8379     .12       0138.0179     .06       0149.6379     .12       0
#XS Ineff= 2 , 0
       0     137  107.26   149.7       0   107.4
Permanent Ineff=
       F       F
Bank Sta=138.0179,149.6379
XS Rating Curve= 0 ,0
Exp/Cntr=0.3,0.1

--- Cold_Brook.g02 (geometry) ---

Geom Title=Base Case - 20% n
Program Version=4.00

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
River Reach=Cold Brook      ,Cold Brook